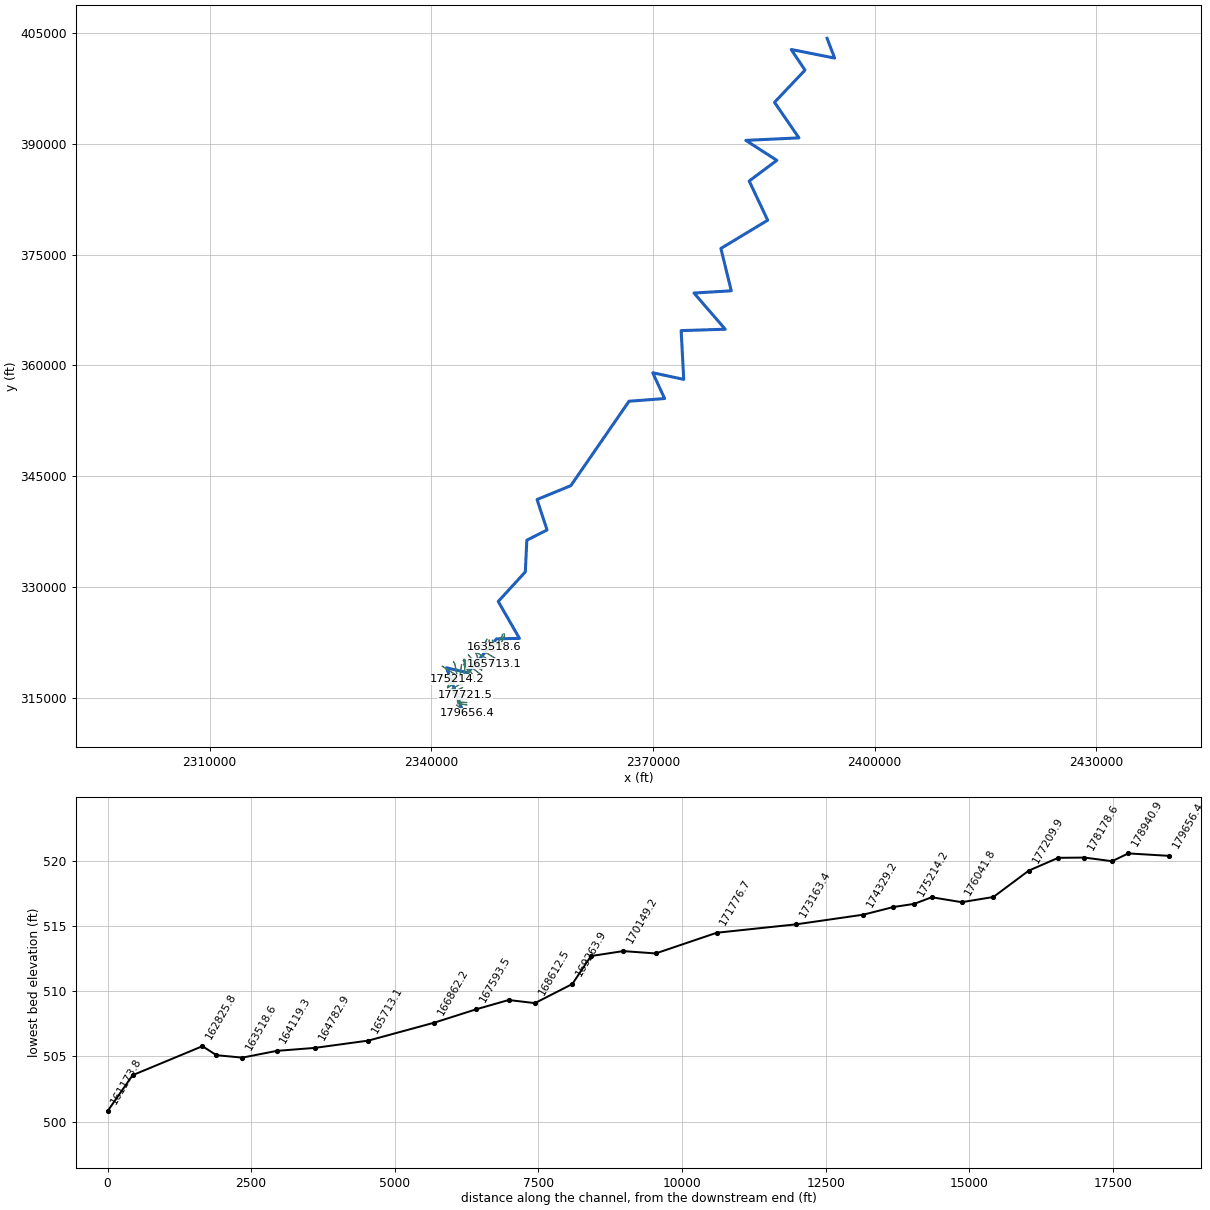
--- BACKCREEK.prj (project) ---

Proj Title=BACKCREEK
Current Plan=p01
Default Exp/Contr=0,0
English Units
Geom File=g01
Flow File=f01
Plan File=p01
BEGIN DESCRIPTION:
END DESCRIPTION:
DSS Export Rating Curves= 0
DSS Export Rating Curve Sorted= 0
DSS Export Volume Flow Curves= 0
DXF OffsetX= 0
DXF OffsetY= 0
DXF ScaleX= 0
DXF ScaleY= 0

--- BACKCREEK.p01 (plan) ---

Plan Title=Floodplain
Program Version=4.00
Geom File=g01
Flow File=f01
K Sum by GR=0
Std Step Tol=0.01
Critical Tol=0.01
Num of Std Step Trials=20
Max Error Tol=0.3
Flow Tol Ratio=0.001
Split Flow NTrial=30
Split Flow Tol=0.02
Split Flow Ratio=0.02
Log Output Level=0
Friction Slope Method=1
Unsteady Friction Slope Method=2
Unsteady Bridges Friction Slope Method=1
Global Log Level=0
CheckData=False
Run HTab=0
Run UNet=0
Run PostProcess=0
UNET Theta=0
UNET Theta Warmup=0
UNET ZTol=0
UNET ZSATol=0
UNET MxIter=0
UNET MaxInSteps=0
UNET DtIC=0
UNET DtMin=0
UNET MaxCRTS=0
UNET WFStab=0
UNET SFStab=0
UNET WFX=0
UNET SFX=0
UNET DSS MLevel=0
UNET DZMax Abort=0
UNET Convert EG Bridges=0
UNET Use Existing IB Tables=0
UNET Froude Limit=0
UNET Froude Power=0
Write IC File=0
Echo Input=False
Echo Output=False
Write Detailed=0

--- BACKCREEK.f01 (steady flow) ---

Flow Title=NFF Regression Equation
Program Version=4.00
Number of Profiles=1
Profile Names=P100yr
River Rch & RM=BACKCREEK,Main      ,179656.4
23364.74
River Rch & RM=BACKCREEK,Main      ,146022.5
25037.01
River Rch & RM=BACKCREEK,Main      ,122615.4
27790.95
River Rch & RM=BACKCREEK,Main      ,40588.2
30271.59
River Rch & RM=BACKCREEK,Main      ,144.5
33633.43
Boundary for River Rch & Prof#=BACKCREEK,Main      ,1
Up Type=0
Dn Type=3
Dn Slope=0.000693

--- BACKCREEK.g01 (geometry) ---

Geom Title=USGS 10m DEM
Program Version=4.10

River Reach=BACKCREEK       ,Main
Reach XY= 30
     2344170.161      313478.987     2342060.786      319095.307
      2344934.05      318431.244      2348844.64      323018.918
     2351934.918      323075.341     2349065.994      328071.001
     2352733.529      332077.078     2352933.182      336365.272
     2355671.897       337741.14     2354317.731      341864.404
     2358888.043      343739.404     2366761.307      355163.015
     2371579.015      355527.598     2369968.772      359017.182
     2374165.821      358123.085     2373814.258      364720.307
      2379782.14      364906.939     2375550.369      369802.772
     2380596.899      370106.952     2379191.863      375840.098
     2385524.328      379650.862     2383021.742      384964.795
     2386767.401      387755.594     2382566.012      390459.587
     2389753.512      390798.129     2386446.221      395607.157
     2390573.825      399964.796     2388707.506      402755.594
     2394584.242       401596.74     2393559.936      404266.011

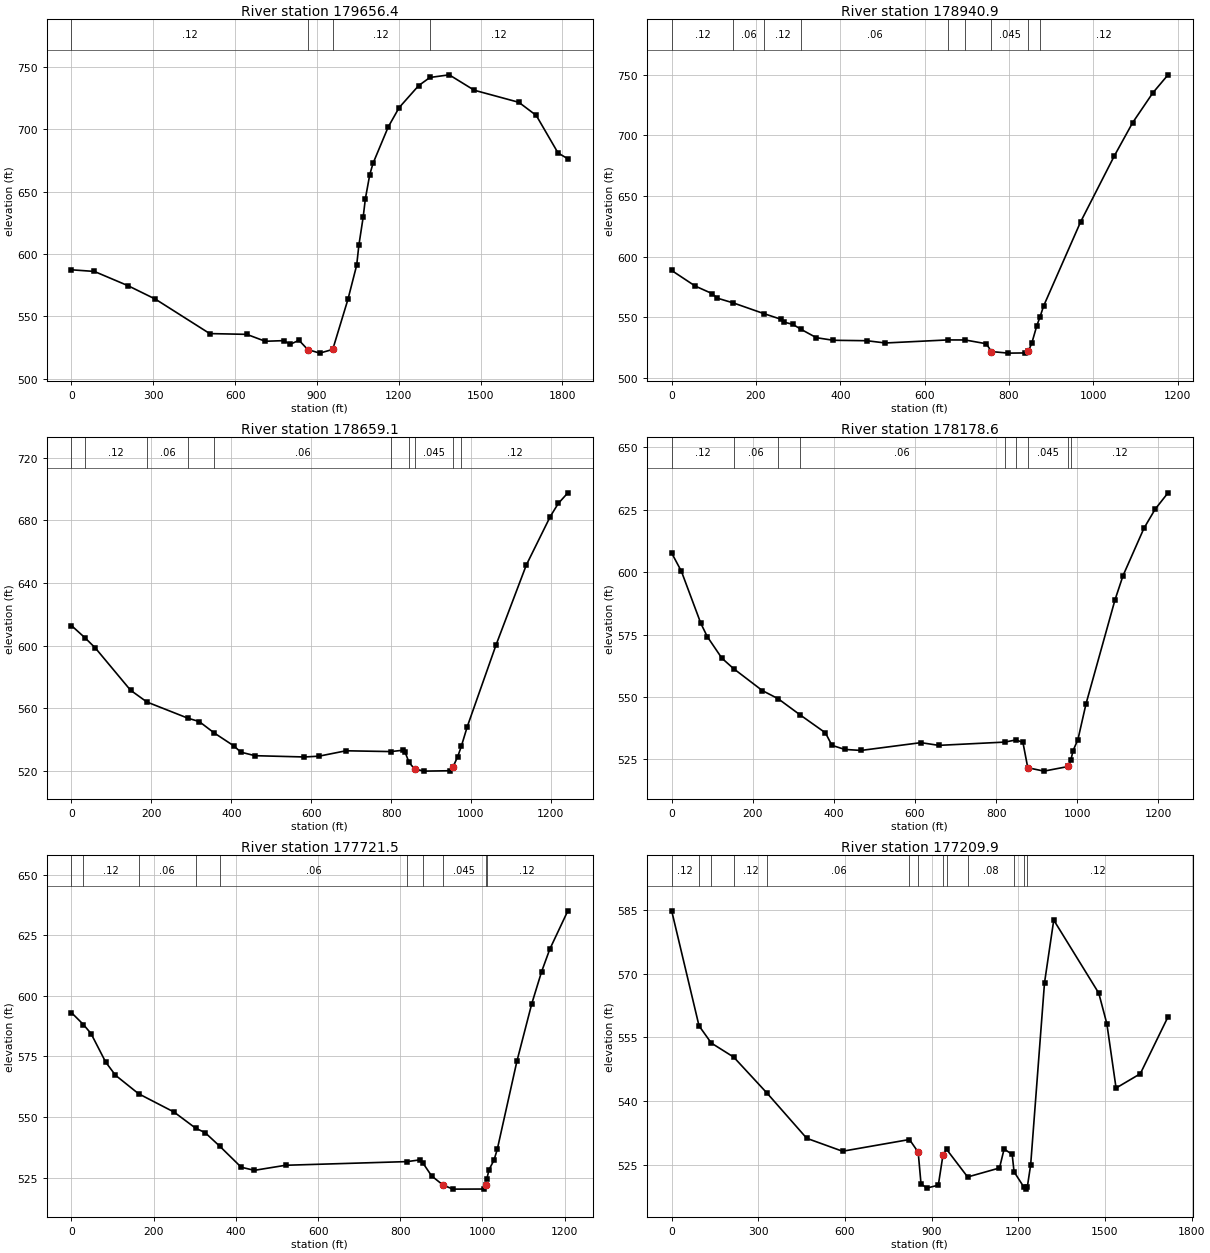
Type RM Length L Ch R = 1 ,179656.4,696.4,715.5,734.7
XS GIS Cut Line= 2
     2343457.009      314044.331     2344895.564      312929.451
#Sta/Elev= 30
       0  587.25    83.8  585.94   207.5  574.48   307.3  563.78   506.9  536.09
   642.6  535.48   710.4  529.93   778.3  530.44   802.2   527.5   834.2  530.73
   866.1  523.32     910  520.42   957.9  523.37  1013.8  563.64  1045.7  590.94
  1053.7  606.87  1069.6  629.62  1077.6  644.28  1093.6  663.48  1105.6  672.62
  1161.4  701.82  1201.4  717.34  1273.2  735.03 1314.21741.5027    1385  743.63
  1476.8  731.28  1640.4  721.58  1704.2  711.05  1784.1  680.94    1820  676.28
#Mann= 4 ,-1 , 0
       0     .12       0   866.1    .045       0   957.9     .12       0
 1314.21     .12       0
Bank Sta=866.1,957.9
XS Rating Curve= 0 ,0
Exp/Cntr=0.3,0.1

Type RM Length L Ch R = 1 ,178940.9,278.3,281.7,285.2
XS GIS Cut Line= 2
     2343632.094      314258.543     2344796.157       314081.46
#Sta/Elev= 30
       0  588.68    55.9  575.84    95.8  569.66   107.8  565.94  146.41561.9428
  219.49553.0615   259.4  548.49   267.4  546.06   287.4  544.31  307.17540.1538
   343.3  533.32   383.2  531.19     463  530.83   506.9  528.97  654.82531.4822
  696.06531.4437   746.4  528.33   758.4  521.89   798.3  520.61   838.2  520.77
   846.2  522.34   854.2  528.79   866.1  543.15  873.99550.6766   882.1   559.3
   969.9  628.63  1049.7  682.86  1093.6  710.52  1141.5  735.04  1177.4  749.83
#Mann= 9 ,-1 , 0
       0     .12       0  146.41     .06       0  219.49     .12       0
  307.17     .06       0  654.82    .016       0  696.06     .12       0
   758.4    .045       0   846.2     .04       0  873.99     .12       0
Bank Sta=758.4,846.2
XS Rating Curve= 0 ,0
Exp/Cntr=0.3,0.1

Type RM Length L Ch R = 1 ,178659.1,471.2,480.5,489.9
XS GIS Cut Line= 2
     2343553.312       314469.51     2344793.553      314396.564
#Sta/Elev= 30
       0  612.86   34.43604.9304    59.9  598.52   147.8  571.63     189 564.089
  292.11553.7201   319.6  551.66  357.01544.4106   407.5  535.92   423.4  532.15
   459.4  529.86   583.2  529.04   619.2  529.54   687.1  532.99   799.5 532.485
   830.9  533.37   834.9  532.16  844.94525.5472   858.9  521.36   882.8  520.01
   946.8  520.26   954.8  522.62   966.7  529.25  975.64535.7526   990.7  548.42
  1062.6  600.47  1138.5  651.55  1198.4  682.46  1218.4  690.78  1242.4  697.58
#Mann= 10 ,-1 , 0
       0     .06       0   34.43     .12       0     189     .06       0
  292.11     .12       0  357.01     .06       0   799.5    .016       0
  844.94     .04       0   858.9    .045       0   954.8     .04       0
  975.64     .12       0
Bank Sta=858.9,954.8
XS Rating Curve= 0 ,0
Exp/Cntr=0.3,0.1

Type RM Length L Ch R = 1 ,178178.6,451.1,457.1,463.1
XS GIS Cut Line= 3
     2343541.246      314722.465     2344556.573      314917.397
     2344736.261      314854.897
#Sta/Elev= 30
       0  607.66      24  600.34    71.8  579.53    87.8  574.17   123.8  565.54
  152.52561.3698   223.5  552.57  262.43549.3063  316.03542.9067   379.2  535.63
   395.2  530.62   427.1  528.98     467  528.58   614.7   531.7   658.6  530.61
  821.45531.9224   848.9  532.78   866.2  531.82   878.2  521.65   918.1  520.29
     978  522.15  984.67524.8787     990  528.53  1001.9  532.96  1021.9  547.29
  1093.3   588.9  1113.1   598.6  1164.7  617.58  1192.4  625.24  1224.1  631.78
#Mann= 9 ,-1 , 0
       0     .12       0  152.52     .06       0  262.43     .12       0
  316.03     .06       0  821.45    .016       0   848.9     .12       0
   878.2    .045       0     978     .04       0  984.67     .12       0
Bank Sta=878.2,978
XS Rating Curve= 0 ,0
Exp/Cntr=0.3,0.1

Type RM Length L Ch R = 1 ,177721.5,507.9,511.6,514.9
XS GIS Cut Line= 3
     2343481.053       314969.48     2343707.615      315107.501
     2344593.032      315430.418
#Sta/Elev= 30
       0  593.05   29.03588.1438    47.5  584.44    83.2  572.67   106.9  567.26
  163.19559.6155   249.4  552.07  302.18545.3975   325.2  543.56  361.26537.8944
     413   529.3     445  528.02   520.9  530.11   817.1531.6265   848.3  532.35
  855.11531.0475   876.3  525.72   904.2  521.94   928.2  520.27  1004.1  520.31
  1008.1  522.13 1010.36524.2657  1016.1  528.31    1028   532.2    1036  536.64
    1084  573.13  1119.9  596.69  1143.9  609.95  1163.8  619.21  1207.8  635.05
#Mann= 10 ,-1 , 0
       0     .06       0   29.03     .12       0  163.19     .06       0
  302.18     .12       0  361.26     .06       0   817.1    .016       0
  855.11     .12       0   904.2    .045       0  1008.1     .08       0
 1010.36     .12       0
Bank Sta=904.2,1008.1
XS Rating Curve= 0 ,0
Exp/Cntr=0.3,0.1

Type RM Length L Ch R = 1 ,177209.9,617.5,616.8,615.8
XS GIS Cut Line= 2
     2343220.207      315257.714     2344745.018      316049.531
#Sta/Elev= 30
       0  584.82   94.68 557.743  137.16553.6882  214.73550.3754  330.98541.8297
   467.5  531.26   591.4  528.21   823.1  530.97  853.32527.9926   863.1  520.56
     883  519.53     923  520.23     939  527.24  951.38528.6819 1024.52522.1494
  1134.8  524.27  1150.8  528.74  1178.7  527.46 1185.24523.3632 1218.79519.8108
  1226.7  519.29 1230.97519.7361  1242.7  525.03  1290.6  567.87  1322.6  582.64
  1478.4  565.44  1506.4  558.24  1538.3  543.09  1622.2  546.46  1718.2  559.87
#Mann= 13 ,-1 , 0
       0     .12       0   94.68    .016       0  137.16     .06       0
  214.73     .12       0  330.98     .06       0   823.1     .12       0
  853.32    .045       0     939     .04       0  951.38     .12       0
 1024.52     .08       0 1185.24     .12       0 1218.79     .04       0
 1230.97     .12       0
Bank Sta=853.32,939
XS Rating Curve= 0 ,0
Exp/Cntr=0.3,0.1

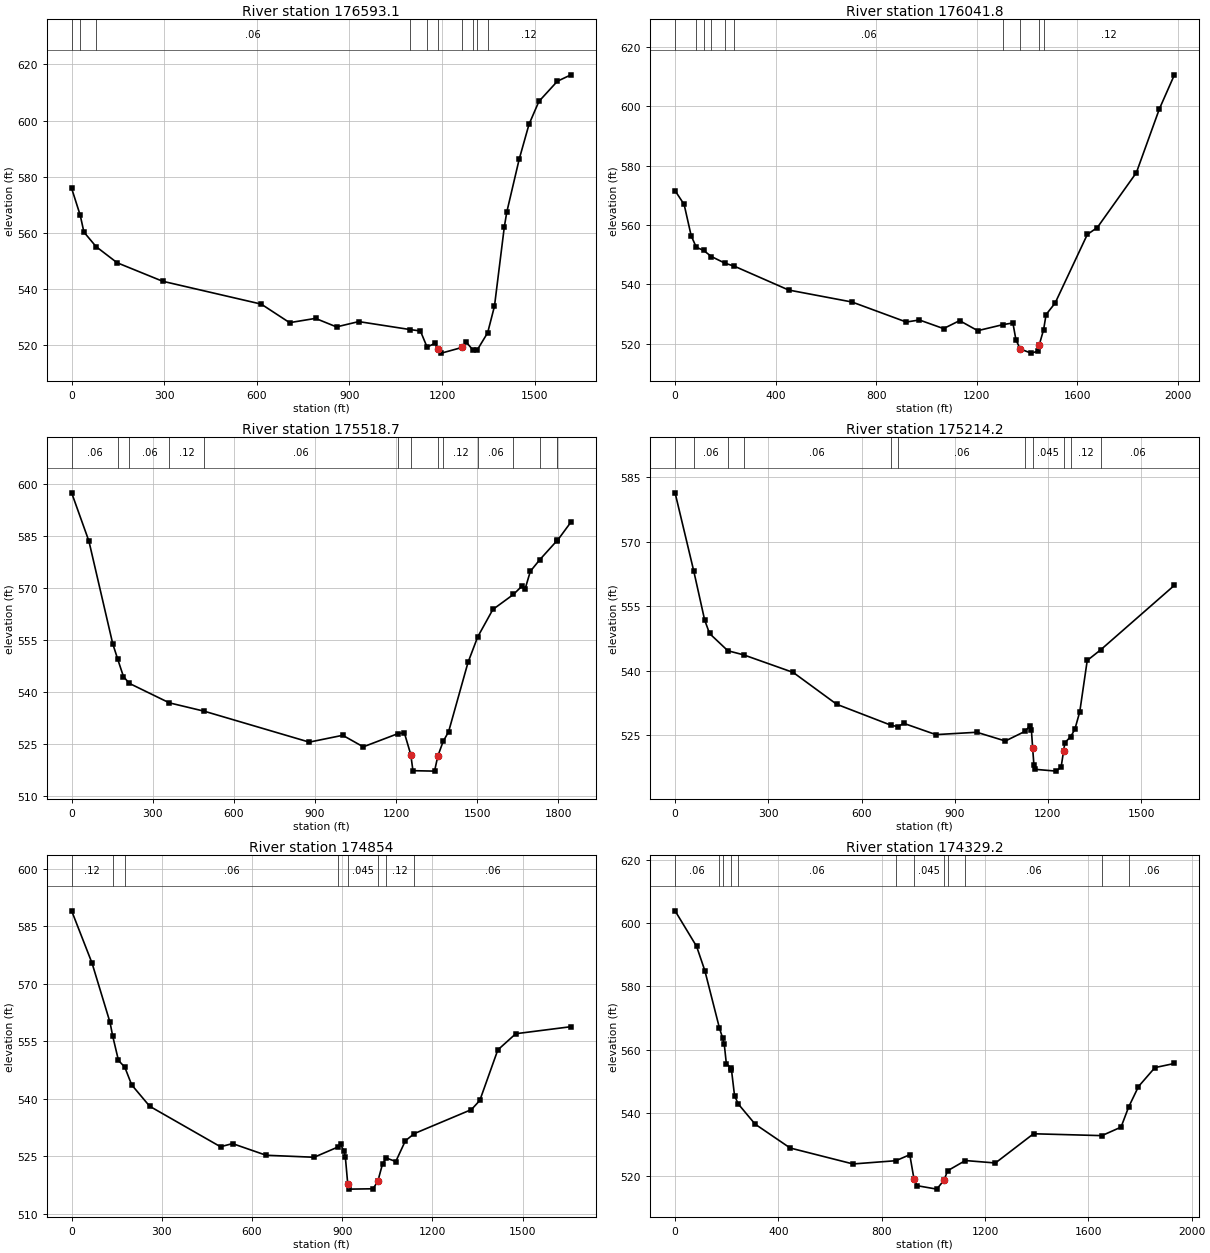
Type RM Length L Ch R = 1 ,176593.1,547.9,551.3,555
XS GIS Cut Line= 3
     2342885.643      315580.781     2343096.581       315880.26
     2344229.393       316411.51
#Sta/Elev= 30
       0  575.89   27.91566.2753    39.8  560.32   79.22555.1522   147.3  549.42
   294.6  542.84   614.2   534.7   706.1   528.1     790  529.62     858  526.59
     930  528.48  1097.3525.6312  1129.8  525.14 1151.38519.4111  1177.8   520.8
  1185.8  518.83  1197.8  517.26  1265.7  519.31  1277.7  521.25    1300 518.372
 1314.74518.5412  1347.6 524.489  1369.7  533.95  1401.6  562.15  1409.6  567.45
  1449.6  586.17  1481.6  598.67  1513.6  606.81  1573.5     614  1617.5  616.28
#Mann= 10 ,-1 , 0
       0     .12       0   27.91    .016       0   79.22     .06       0
  1097.3     .12       0 1151.38     .08       0  1185.8    .045       0
  1265.7     .08       0    1300     .12       0 1314.74     .04       0
  1347.6     .12       0
Bank Sta=1185.8,1265.7
XS Rating Curve= 0 ,0
Exp/Cntr=0.3,0.1

Type RM Length L Ch R = 1 ,176041.8,521.1,523.1,525.1
XS GIS Cut Line= 3
     2342435.046      315990.314     2343830.879      316849.689
     2344177.233      316849.689
#Sta/Elev= 30
       0  571.55      36  566.91      64  556.38   84.21 552.519  113.35551.4321
   144.8 549.364  198.61547.1279  235.91546.1196   451.8   538.1   703.6  534.07
   919.5  527.33   971.5  528.02  1067.5  525.12  1131.4   527.8  1203.4  524.42
 1304.83526.4762  1343.3  527.01  1355.3  521.36 1372.27518.2729  1415.3  516.86
  1443.3  517.52  1447.3  519.43  1465.4524.7657  1475.2  529.84  1511.2  533.72
  1639.2  556.81    1679  559.15  1834.2  577.61  1925.8   599.1  1985.5  610.56
#Mann= 10 ,-1 , 0
       0     .12       0   84.21     .06       0  113.35     .12       0
   144.8     .06       0  198.61    .016       0  235.91     .06       0
 1304.83     .12       0 1372.27    .045       0  1447.3     .04       0
  1465.4     .12       0
Bank Sta=1372.27,1447.3
XS Rating Curve= 0 ,0
Exp/Cntr=0.3,0.1

Type RM Length L Ch R = 1 ,175518.7,303.6,304.5,305.4
XS GIS Cut Line= 3
     2342235.219      316396.217     2343513.865      317279.029
     2343805.532      317252.987
#Sta/Elev= 30
       0  597.56    63.9  583.62   151.8  554.06  170.58549.5084   191.7  544.52
  213.46542.5662  361.26536.9468  491.22534.5163   878.8  525.61  1002.6  527.58
  1078.5  524.25    1206528.0383  1230.3  528.33  1254.2  522.01  1262.2  517.37
  1342.1  517.24  1354.1  521.54 1373.81525.7952    1394  528.59  1465.9  548.62
 1501.68555.9781  1557.8   563.9 1633.72568.2253  1664.6  570.59  1676.5  569.67
  1696.3   574.9 1731.23 578.253  1795.1583.7688 1796.49583.8064  1846.6  589.12
#Mann= 14 ,-1 , 0
       0     .06       0  170.58    .016       0  213.46     .06       0
  361.26     .12       0  491.22     .06       0    1206     .12       0
  1254.2    .045       0  1354.1     .04       0 1373.81     .12       0
 1501.68     .06       0 1633.72     .12       0 1731.23     .06       0
  1795.1     .12       0 1796.49     .06       0
Bank Sta=1254.2,1354.1
XS Rating Curve= 0 ,0
Exp/Cntr=0.3,0.1

Type RM Length L Ch R = 1 ,175214.2,363.5,360.2,356.9
XS GIS Cut Line= 4
     2342215.428      316534.585     2342415.331      316839.114
      2343277.31      317479.739     2343438.768      317529.219
#Sta/Elev= 30
       0  581.31   60.02563.1877      95  551.85   110.9  548.67  169.86544.6621
  220.33543.7203   380.2  539.63     520  532.25  693.65  527.42  717.19527.0377
   735.6  527.83   839.4   525.2   971.1  525.75    1063  523.72 1125.59525.9399
  1142.8  527.27  1146.8  526.32  1150.8  522.14  1154.8  518.25  1158.8  517.15
  1226.6  516.73  1242.6  517.73  1250.6  521.46  1254.6  523.34 1272.86524.6921
  1286.5  526.39  1302.5  530.51  1326.5  542.41 1370.15   544.9  1607.1  559.85
#Mann= 11 ,-1 , 0
       0     .12       0   60.02     .06       0  169.86    .016       0
  220.33     .06       0  693.65     .12       0  717.19     .06       0
 1125.59     .12       0  1150.8    .045       0  1250.6     .04       0
 1272.86     .12       0 1370.15     .06       0
Bank Sta=1150.8,1250.6
XS Rating Curve= 0 ,0
Exp/Cntr=0.3,0.1

Type RM Length L Ch R = 1 ,174854  ,538.7,524.8,517.7
XS GIS Cut Line= 3
     2341978.448      317042.397     2343132.094      317758.543
     2343426.365      317685.626
#Sta/Elev= 30
       0  589.05    67.9  575.41   127.8  559.94  136.51556.4238   155.8  550.04
  176.89548.2814   199.7  543.68   259.6   538.1   495.2  527.54   535.2  528.36
     647  525.32   806.7   524.8  885.69527.4649   894.6  528.14   906.6  526.31
   910.6  524.79   918.6  517.71   922.5  516.49  1002.4  516.58  1018.4   518.5
  1034.4  523.13 1046.88524.5911  1078.3  523.69  1110.2   529.1    1140 530.972
  1329.9  537.23  1357.8  539.62  1417.7  552.79  1477.5  557.01    1661  558.84
#Mann= 8 ,-1 , 0
       0     .12       0  136.51    .016       0  176.89     .06       0
  885.69     .12       0   918.6    .045       0  1018.4     .04       0
 1046.88     .12       0    1140     .06       0
Bank Sta=918.6,1018.4
XS Rating Curve= 0 ,0
Exp/Cntr=0.3,0.1

Type RM Length L Ch R = 1 ,174329.2,1194,1165.8,1129.6
XS GIS Cut Line= 6
     2341495.192      317977.135      2341780.96      317979.316
     2342430.448      317937.985     2342494.642      317961.618
     2343212.303       317888.23     2343384.178      317773.647
#Sta/Elev= 30
       0  603.82    83.4  592.57   115.1  584.95  171.83566.7606  184.07563.6296
   190.5  561.62   198.5  555.49  215.07554.2864   218.3   553.6   230.2  545.43
  244.59542.7997   309.7  536.44   445.5  528.89     689  523.85  854.91524.8787
   908.6  526.77   924.6  519.21   936.6  516.99    1013   515.9  1040.8  518.69
 1055.18521.7097 1123.64524.9308  1240.1  524.16  1387.6  533.39 1652.22532.8008
  1726.4  535.49 1755.58541.7794  1793.9  548.31  1857.5  554.29    1933   555.6
#Mann= 12 ,-1 , 0
       0     .06       0  171.83     .12       0  184.07    .016       0
  215.07     .12       0  244.59     .06       0  854.91     .12       0
   924.6    .045       0  1040.8     .04       0 1055.18     .12       0
 1123.64     .06       0 1652.22     .12       0 1755.58     .06       0
Bank Sta=924.6,1040.8
XS Rating Curve= 0 ,0
Exp/Cntr=0.3,0.1

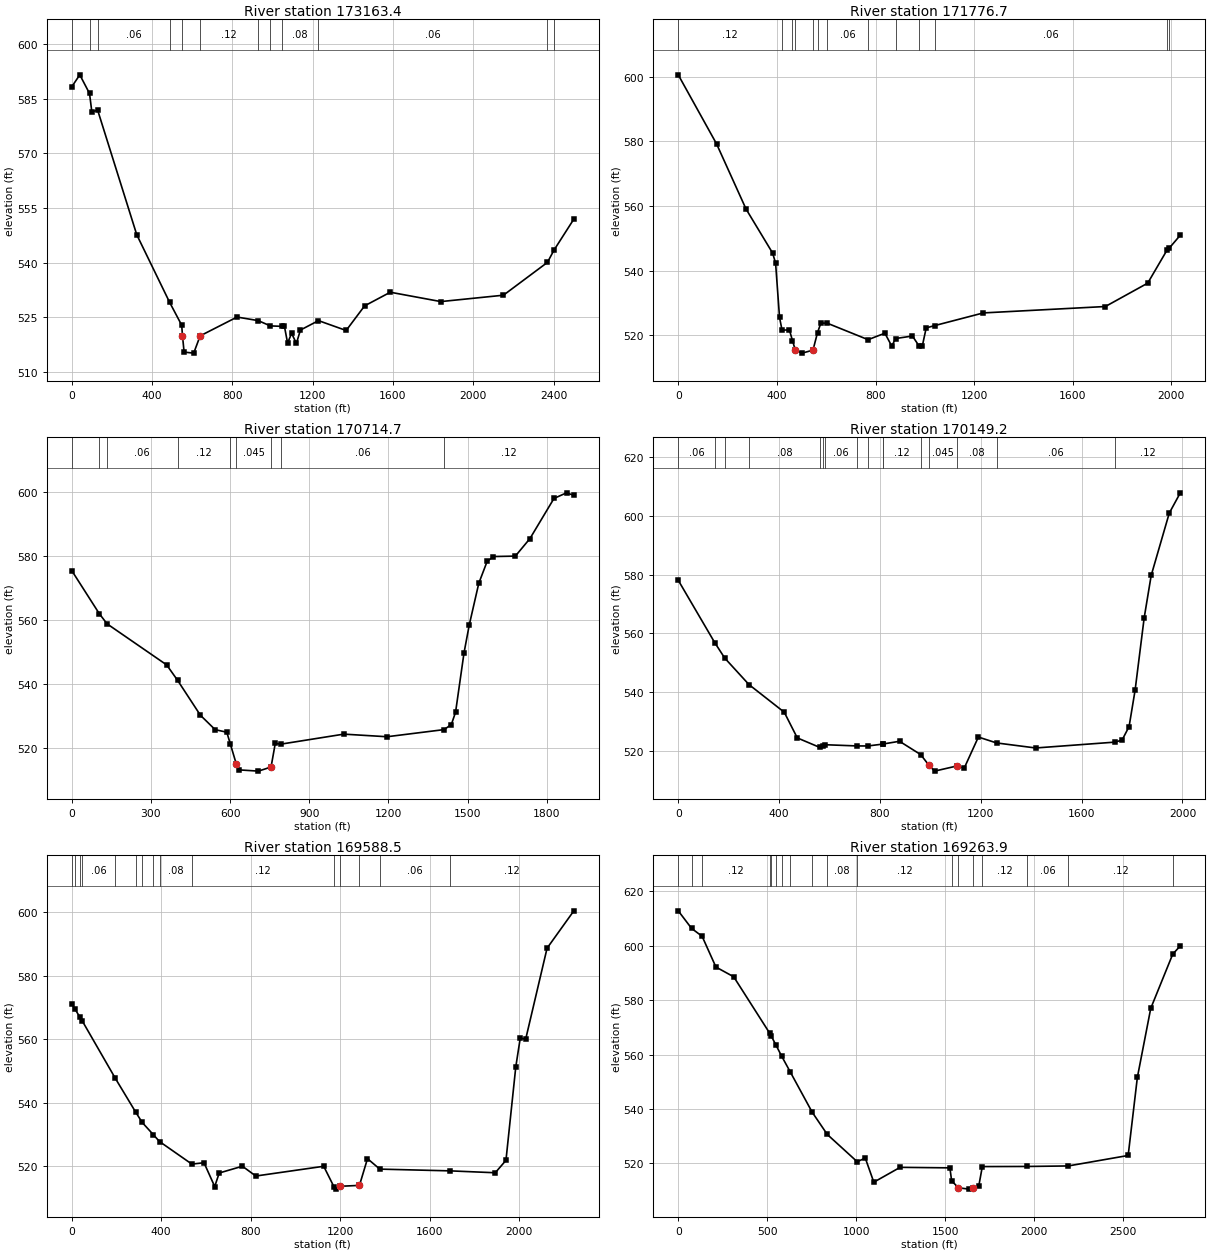
Type RM Length L Ch R = 1 ,173163.4,1416.7,1386.8,1357.9
XS GIS Cut Line= 3
     2341501.995      319302.741     2343425.844       318075.73
     2343519.594      317877.814
#Sta/Elev= 30
       0  588.33      40  591.61   88.46586.4852    99.9  581.46  128.97581.8966
   323.7  547.68  487.34529.1201   547.5  522.84   551.5  519.92   559.5  515.44
   607.4  515.16   639.4   519.9   823.2  525.07   928.3 524.096  989.02522.6436
 1045.74522.5143    1059  522.58    1075  517.92    1095   520.6  1118.9  517.83
  1138.9   521.5 1228.88524.0888  1366.7  521.38  1458.6  528.14  1586.5  531.89
  1838.2  529.32    2150  531.07 2369.17540.0839 2402.09 543.469  2500.8  551.98
#Mann= 12 ,-1 , 0
       0     .12       0   88.46    .016       0  128.97     .06       0
  487.34     .12       0   551.5    .045       0   639.4     .12       0
   928.3     .06       0  989.02     .12       0 1045.74     .08       0
 1228.88     .06       0 2369.17     .12       0 2402.09     .06       0
#XS Ineff= 2 , 0
       0                    1890       0
Permanent Ineff=
       F       F
Bank Sta=551.5,639.4
XS Rating Curve= 0 ,0
Exp/Cntr=0.3,0.1

Type RM Length L Ch R = 1 ,171776.7,1074.9,1062,1049.1
XS GIS Cut Line= 4
      2343027.31      319891.198     2343175.681      319669.122
     2343509.178      318034.064     2343565.504      317951.094
#Sta/Elev= 30
       0  600.55   155.5  579.19   275.1  559.04   382.8  545.44   394.8  542.34
   410.8  525.55  420.98521.6184   450.7  521.69  463.24518.4135   474.7  515.47
   502.6  514.51   546.5  515.44   564.8520.8353   578.5  523.82  604.99523.7428
  769.98518.6674     838  520.67   865.9  516.68  881.43519.0219   949.7   519.8
  977.65516.6104   989.7  516.68  1005.6  522.31 1041.31523.0487  1237.2  526.94
  1732.2  528.92  1903.9  536.15 1982.29546.3715 1991.86547.0266  2036.1  550.98
#Mann= 13 ,-1 , 0
       0     .12       0  420.98    .016       0  463.24     .04       0
   474.7    .045       0   546.5     .04       0   564.8     .12       0
  604.99     .06       0  769.98     .12       0  881.43     .08       0
  977.65     .12       0 1041.31     .06       0 1982.29     .12       0
 1991.86     .06       0
Bank Sta=474.7,546.5
XS Rating Curve= 0 ,0
Exp/Cntr=0.3,0.1

Type RM Length L Ch R = 1 ,170714.7,579,565.5,552.1
XS GIS Cut Line= 3
     2344099.358      319506.649     2343899.803        317973.3
     2344181.053       317754.55
#Sta/Elev= 30
       0  575.36  104.05561.9849  133.75558.7894   359.6     546  400.79541.2205
   487.5  530.32   543.4  525.83   587.4  525.04  600.61521.4575   623.3  515.18
   635.3   513.3   707.2  512.92   755.2   514.2   771.1  521.54   792.9521.3305
  1030.8  524.44  1194.7  523.63 1410.86525.8513  1438.4  527.43  1454.4  531.28
  1486.4  549.75  1506.3  558.46  1542.3   571.4    1574  578.23  1597.8  579.75
  1680.9  579.88  1736.3  585.35  1827.4  597.85  1874.9  599.59  1902.6   598.8
#Mann= 9 ,-1 , 0
       0     .12       0  104.05     .08       0  133.75     .06       0
  400.79     .12       0  600.61     .04       0   623.3    .045       0
   755.2     .12       0   792.9     .06       0 1410.86     .12       0
Bank Sta=623.3,755.2
XS Rating Curve= 0 ,0
Exp/Cntr=0.3,0.1

Type RM Length L Ch R = 1 ,170149.2,528.1,560.7,593.3
XS GIS Cut Line= 5
     2344407.518      319596.059     2344524.803       319263.23
     2344529.046      318615.156     2344463.942      318489.288
     2344535.219      317643.439
#Sta/Elev= 30
       0  578.06  144.57556.8676  184.48551.5708  280.58542.5596   420.5  533.15
   472.2  524.41  562.19521.1436   573.4521.5739  583.61 522.085  707.72 521.677
  752.35521.6646  810.38  522.29  811.75522.3195   877.7  523.26  961.54518.7358
     993  515.26  1016.7   513.1  1107.3  514.89  1134.8  514.21  1190.5   524.7
 1262.47522.6958  1417.7  520.98  1732.1 522.971  1760.4  523.65  1788.3  528.27
  1812.2  540.66  1848.1  565.24    1876   579.7  1947.7  600.92  1991.5  607.82
#Mann= 16 ,-1 , 0
       0     .06       0  144.57     .08       0  184.48     .06       0
  280.58     .08       0  562.19     .06       0   573.4     .08       0
  583.61     .06       0  707.72     .08       0  752.35     .06       0
  810.38     .08       0  811.75     .12       0  961.54     .04       0
     993    .045       0  1107.3     .08       0 1262.47     .06       0
  1732.1     .12       0
Bank Sta=993,1107.3
XS Rating Curve= 0 ,0
Exp/Cntr=0.3,0.1

Type RM Length L Ch R = 1 ,169588.5,293.1,324.6,356.1
XS GIS Cut Line= 3
     2344557.355      319615.574     2345307.355      317730.158
      2345135.48      317599.949
#Sta/Elev= 30
       0  571.08   14.36569.4816   36.18566.9333   46.34565.8021  195.02 547.608
  286.01 536.963  314.75533.7437  365.18529.8424  392.33527.7196  536.91520.6064
   591.2  521.04   639.1  513.53   659.1   517.8   762.9  519.94   822.8  516.85
  1126.4  519.92 1172.41513.4353  1182.3  512.72  1198.3  513.61  1286.2   513.9
  1322.1  522.32 1377.27519.0283 1691.42518.4764  1893.3  517.88  1941.2  521.79
  1985.2   551.3  2005.2  560.38  2029.1  559.91    2125  588.66  2244.7  600.44
#Mann= 15 ,-1 , 0
       0     .08       0   14.36     .06       0   36.18     .08       0
   46.34     .06       0  195.02     .08       0  286.01     .06       0
  314.75     .08       0  365.18     .06       0  392.33     .08       0
  536.91     .12       0 1172.41     .04       0  1198.3    .045       0
  1286.2     .08       0 1377.27     .06       0 1691.42     .12       0
Bank Sta=1198.3,1286.2
XS Rating Curve= 0 ,0
Exp/Cntr=0.3,0.1

Type RM Length L Ch R = 1 ,169263.9,639.7,651.4,663.1
XS GIS Cut Line= 6
     2344359.577       320058.53     2344696.678      319409.064
     2345179.494      318722.071     2345263.745      318690.434
     2345743.553       317919.48     2345701.886       317669.48
#Sta/Elev= 30
       0  612.85   75.21606.3828  134.21603.4924   211.9  592.19   311.9  588.61
  514.74567.8192  522.87566.8509  548.29563.6495  581.84559.3915  630.57553.5568
     753 538.856  838.07  530.66 1006.34520.6368  1051.6  521.99  1099.6  513.12
  1247.6  518.58  1527.4  518.39 1537.13513.6252  1575.3  511.07    1634  510.57
  1657.5  511.09  1689.3  511.55 1709.71518.8574 1963.02518.9025 2192.84519.0886
  2529.7  522.94  2581.4  551.63  2656.6  576.99  2780.3596.9229  2822.9  599.98
#Mann= 18 ,-1 , 0
       0    .016       0   75.21     .08       0  134.21     .12       0
  514.74     .08       0  522.87     .12       0  548.29     .08       0
  581.84     .06       0  630.57     .08       0     753     .06       0
  838.07     .08       0 1006.34     .12       0 1537.13     .04       0
  1575.3    .045       0  1657.5     .08       0 1709.71     .12       0
 1963.02     .06       0 2192.84     .12       0  2780.3     .06       0
Bank Sta=1575.3,1657.5
XS Rating Curve= 0 ,0
Exp/Cntr=0.3,0.1

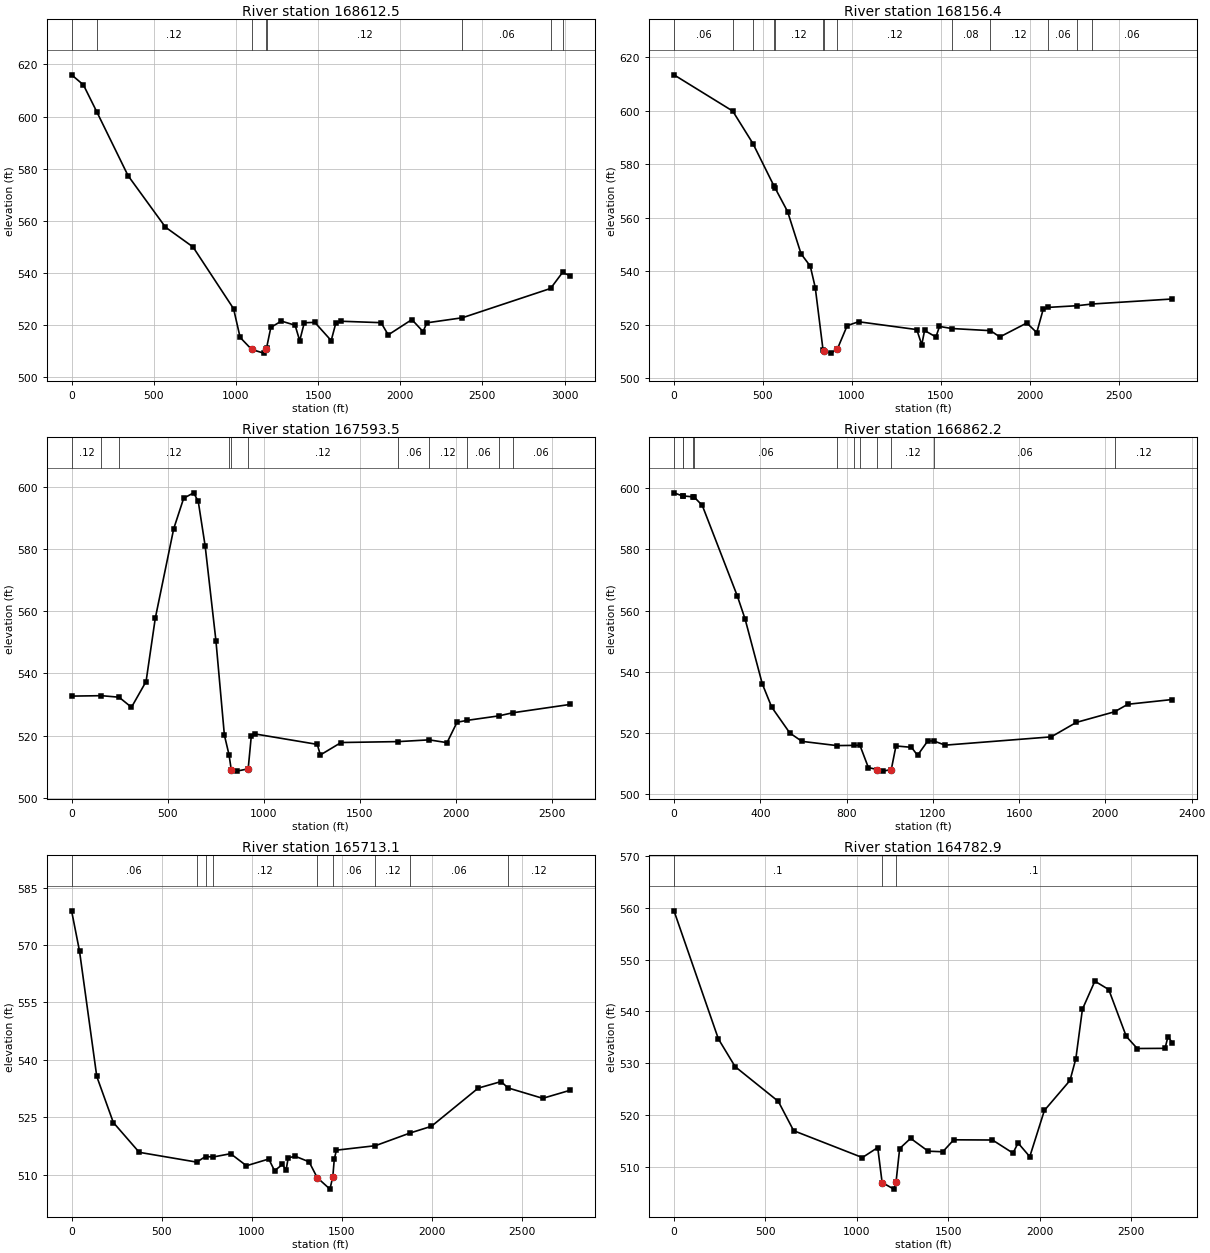
Type RM Length L Ch R = 1 ,168612.5,474.8,456.1,436.9
XS GIS Cut Line= 5
     2344379.856      320130.893       2344887.9      319561.481
     2345091.025      319337.523     2345218.185      319331.189
     2346679.567      318212.523
#Sta/Elev= 30
       0  616.01    71.9  612.16  152.83601.8723   343.6  577.28   571.3  557.49
   739.1  549.88   985.9  526.16  1025.7  515.14 1095.97510.5127  1168.9   509.1
  1184.8  510.54 1186.41510.9948  1212.7  518.97  1276.6  521.42  1360.4  519.81
  1388.4  513.86  1416.3  520.77  1480.2  520.92    1580  513.92    1608  520.57
  1639.9  521.35  1883.4   520.8  1927.3  516.11  2071.1  521.99  2138.9  517.38
  2162.9  520.75 2378.03522.6824 2915.26533.9458 2988.34540.1244  3033.2  538.83
#Mann= 8 ,-1 , 0
       0     .08       0  152.83     .12       0 1095.97    .045       0
  1184.8     .04       0 1186.41     .12       0 2378.03     .06       0
 2915.26     .12       0 2988.34     .04       0
#XS Ineff= 2 , 0
       0                    2506       0
Permanent Ineff=
       F       F
Bank Sta=1095.97,1184.8
XS Rating Curve= 0 ,0
Exp/Cntr=0.3,0.1

Type RM Length L Ch R = 1 ,168156.4,575.8,563,550.5
XS GIS Cut Line= 3
     2344443.393      320240.241     2345199.315       319785.12
     2346835.817      318780.231
#Sta/Elev= 30
       0  613.37  330.34599.8246  444.07 587.686  561.77571.9081  569.17570.9912
   638.8  562.28   714.7  546.46   766.6  541.85   794.5  533.86  838.36510.4996
   842.4  510.23   882.4  509.34   918.3  510.79   974.2  519.62  1038.1  521.07
  1365.4  518.14  1393.4  512.47  1409.4   517.8  1473.2  515.38  1493.2  519.32
  1561.5 518.543 1779.98517.7372  1832.6  515.39  1984.3  520.61  2040.2  517.01
  2076.1  525.65 2104.79526.4369 2268.53527.0727 2351.13   527.7  2802.8  529.58
#Mann= 13 ,-1 , 0
       0     .06       0  330.34     .08       0  444.07     .06       0
  561.77     .08       0  569.17     .12       0  838.36     .04       0
   842.4    .045       0   918.3     .12       0  1561.5     .08       0
 1779.98     .12       0 2104.79     .06       0 2268.53     .12       0
 2351.13     .06       0
Bank Sta=842.4,918.3
XS Rating Curve= 0 ,0
Exp/Cntr=0.3,0.1

Type RM Length L Ch R = 1 ,167593.5,749.4,731.3,713.2
XS GIS Cut Line= 3
     2345033.439      320842.083     2346369.676      319230.778
     2346813.247      319000.717
#Sta/Elev= 30
       0  532.73   155.6 532.864  247.05532.3766   311.6  529.14   387.5  537.41
   435.4  557.71   531.3  586.48   583.2   596.3   635.2  598.03   659.1  595.26
   695.1  580.89     751  550.54     795   520.2  819.08513.9017   830.9  509.02
   858.9  508.63   918.8  509.36   934.8  519.78   954.8  520.57  1278.3  517.22
  1294.3  513.82  1402.2  517.82 1700.49518.1156 1860.54518.6735  1953.5  517.78
  2005.4  524.32 2058.42 524.942 2222.99526.3779 2294.22 527.363    2593  530.05
#Mann= 11 ,-1 , 0
       0     .12       0   155.6    .016       0  247.05     .12       0
  819.08     .04       0   830.9    .045       0   918.8     .12       0
 1700.49     .06       0 1860.54     .12       0 2058.42     .06       0
 2222.99     .12       0 2294.22     .06       0
#XS Ineff= 2 , 0
       0                    2033       0
Permanent Ineff=
       F       F
Bank Sta=830.9,918.8
XS Rating Curve= 0 ,0
Exp/Cntr=0.3,0.1

Type RM Length L Ch R = 1 ,166862.2,1118,1149.1,1180.2
XS GIS Cut Line= 4
     2345967.511      321164.272     2346181.053      320815.314
     2346493.958      319230.269     2346752.483      319109.224
#Sta/Elev= 30
       0  598.46    40.4 597.427   42.99597.4529   86.49597.1519   94.46597.0038
   131.1  594.36   293.9  564.73   329.7  557.24   409.1  536.15   453.1  528.48
   537.1  520.04   593.1  517.32  754.95515.9384  833.94516.0037  861.95516.0406
     901  508.78     941  508.12     969   507.6 1007.33508.1165    1029  515.82
    1101  515.37    1129  512.76  1176.9  517.49 1206.71517.3914  1256.9  516.08
  1748.8  518.79  1864.8   523.5 2042.07526.9712    2104  529.43  2310.2  530.98
#Mann= 12 ,-1 , 0
       0    .016       0    40.4     .08       0   42.99    .016       0
   86.49     .08       0   94.46     .06       0  754.95     .12       0
  833.94    .016       0  861.95     .04       0     941    .045       0
 1007.33     .12       0 1206.71     .06       0 2042.07     .12       0
Bank Sta=941,1007.33
XS Rating Curve= 0 ,0
Exp/Cntr=0.3,0.1

Type RM Length L Ch R = 1 ,165713.1,930.9,930.1,929.3
XS GIS Cut Line= 3
     2346222.719      321127.814     2348082.094      319961.147
     2348553.699      319634.398
#Sta/Elev= 30
       0  578.95      44  568.44   139.9  535.67   231.9  523.63   375.8  515.84
  695.24  513.28  744.05514.7391  786.95514.6225   883.6  515.48   971.6  512.33
  1095.5  514.09  1127.5  511.04  1171.5  512.66  1191.5  511.14  1203.5  514.42
  1243.5  514.79  1319.4  513.36 1364.51509.2315  1435.4  506.22  1451.4   509.5
  1459.4  514.04  1471.4   516.4  1687.8517.5687 1880.28520.8832  1999.2  522.64
  2258.8  532.61  2386.3  534.33 2424.24532.6776  2617.4  529.95  2768.8  532.04
#Mann= 9 ,-1 , 0
       0     .06       0  695.24     .12       0  744.05    .016       0
  786.95     .12       0 1364.51    .045       0  1451.4     .06       0
  1687.8     .12       0 1880.28     .06       0 2424.24     .12       0
Bank Sta=1364.51,1451.4
XS Rating Curve= 0 ,0
Exp/Cntr=0.3,0.1

Type RM Length L Ch R = 1 ,164782.9,662.6,663.7,664.7
XS GIS Cut Line= 3
     2346425.844      321846.564     2346675.844      321612.189
     2348701.268      320354.884
#Sta/Elev= 30
       0  559.43   243.1  534.67   334.7  529.32   570.7  522.62   654.7  516.95
  1030.7  511.76  1114.7  513.69  1138.7  506.94  1202.7  505.66  1214.7  506.97
  1234.7   513.5  1294.7  515.47  1390.7  512.99  1470.6  512.88  1530.6  515.19
  1742.6  515.15  1854.6  512.62  1882.6  514.57  1946.6  511.93  2026.6  520.87
  2166.6  526.66  2198.6  530.86  2234.6  540.42  2302.6  545.84  2378.6  544.22
  2474.6  535.16  2534.6  532.83  2686.6  532.86  2702.6  535.12  2726.6  533.93
#Mann= 3 , 0 , 0
       0      .1       0  1138.7    .045       0  1214.7      .1       0
Bank Sta=1138.7,1214.7
XS Rating Curve= 0 ,0
Exp/Cntr=0.3,0.1

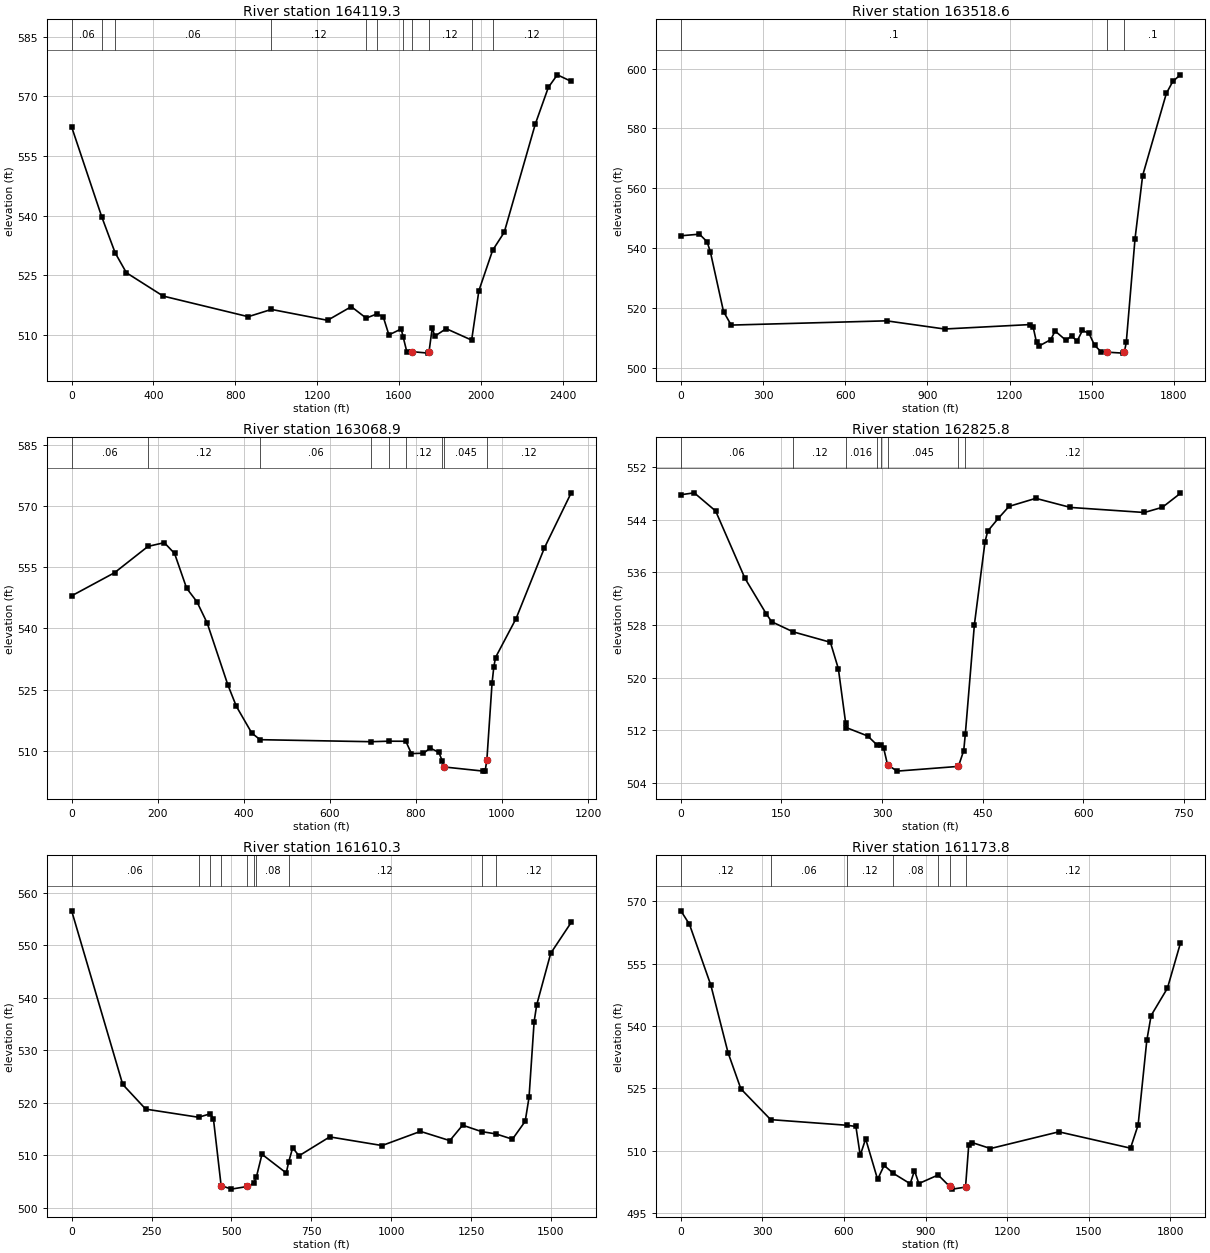
Type RM Length L Ch R = 1 ,164119.3,606.5,600.7,595
XS GIS Cut Line= 4
     2346480.478      322117.847     2346927.527      322204.653
     2348248.761      321310.105     2348634.178      321377.814
#Sta/Elev= 30
       0  562.28  146.96539.7191  212.71530.6338   267.6  525.64   447.4  519.77
   863.3  514.59  976.61516.4153  1251.2  513.68  1367.2  517.11 1440.02 514.227
 1491.59515.2665  1523.1   514.6  1551.1  510.01  1611.1   511.5 1621.37509.3652
  1639.1  505.68  1661.9505.8094  1743.1  505.43  1747.1  505.71    1763  511.82
    1775  509.67    1831  511.58 1955.57508.7041    1991  521.13 2058.25531.2838
  2114.9   535.8  2266.6  562.97  2330.5  572.22  2374.4  575.38  2442.3  573.74
#Mann= 11 ,-1 , 0
       0     .06       0  146.96     .12       0  212.71     .06       0
  976.61     .12       0 1440.02    .016       0 1491.59     .12       0
 1621.37     .04       0  1661.9    .045       0  1747.1     .12       0
 1955.57     .08       0 2058.25     .12       0
Bank Sta=1661.9,1747.1
XS Rating Curve= 0 ,0
Exp/Cntr=0.3,0.1

Type RM Length L Ch R = 1 ,163518.6,436.8,449.7,462.6
XS GIS Cut Line= 4
     2347534.485      322953.617     2347360.874       322661.95
     2348419.167      321841.903     2348556.997       321889.54
#Sta/Elev= 30
       0  544.12    67.9  544.65    95.8   542.1   107.8  538.68   155.7  518.78
   183.7  514.28   751.1   515.7   962.9  512.97  1274.6  514.45  1286.6   513.5
  1298.6  508.48  1306.6  507.22  1350.5  509.42  1366.5   512.3  1406.5  509.16
  1426.5   510.7  1446.5  508.89  1466.4   512.5  1490.4  511.48  1510.4  507.56
  1534.4  505.35  1554.4  505.24  1614.3  504.91 1619.22505.2184  1626.3   508.5
  1658.3  543.15  1686.1  564.24  1772.8  591.72  1796.5  595.72  1824.1  597.89
#Mann= 3 , 0 , 0
       0      .1       0  1554.4    .045       0 1619.22      .1       0
#XS Ineff= 2 , 0
       0     610                       0
Permanent Ineff=
       F       F
Bank Sta=1554.4,1619.22
XS Rating Curve= 0 ,0
Exp/Cntr=0.3,0.1

Type RM Length L Ch R = 1 ,163068.9,252.8,243.1,233.5
XS GIS Cut Line= 4
     2347841.643      322830.071     2347799.976      322566.182
     2348518.726      322302.293     2348588.171      322194.654
#Sta/Elev= 30
       0  547.98    99.7  553.64  177.45560.0764   215.3  560.99   239.2  558.34
   267.2  549.84   291.1  546.54     315  541.32   362.9  526.23   382.8  520.94
   418.7   514.4     438512.7921  695.46 512.298  737.48512.4241  776.62512.4025
   789.6  509.39   817.5  509.49   833.4  510.73   853.4  509.69  861.67507.4813
   865.3  506.12     957   505.1     961  505.12     965  507.94     977  526.67
     981  530.52     985  532.89  1032.8  542.42  1098.8  559.74  1160.9  573.18
#Mann= 9 ,-1 , 0
       0     .06       0  177.45     .12       0     438     .06       0
  695.46     .12       0  737.48    .016       0  776.62     .12       0
  861.67     .04       0   865.3    .045       0     965     .12       0
Bank Sta=865.3,965
XS Rating Curve= 0 ,0
Exp/Cntr=0.3,0.1

Type RM Length L Ch R = 1 ,162825.8,1273.5,1215.5,1156.8
XS GIS Cut Line= 4
     2348291.296       322825.73     2348291.296      322690.314
     2348725.323      322395.175     2348711.435      322311.842
#Sta/Elev= 30
       0  547.81    19.9   548.1    51.8  545.34    95.6  535.09   127.4  529.68
   135.4   528.5  167.31526.9669   222.9  525.38   234.8  521.35  245.65513.1159
   246.8   512.4   278.6  511.13  292.91509.7214  298.38509.7693   302.4  509.25
   308.1506.7615   322.3  505.79   413.8  506.51   421.7  508.92  424.03511.3665
   437.6  528.07   453.5   540.7   457.5  542.28   473.4  544.24   489.3  546.04
   529.1  547.26   580.8  545.88     691  545.11   717.9   545.9   744.8  548.03
#Mann= 8 ,-1 , 0
       0     .06       0  167.31     .12       0  245.65    .016       0
  292.91     .12       0  298.38     .04       0   308.1    .045       0
   413.8     .04       0  424.03     .12       0
Bank Sta=308.1,413.8
XS Rating Curve= 0 ,0
Exp/Cntr=0.3,0.1

Type RM Length L Ch R = 1 ,161610.3,431.7,436.5,441.2
XS GIS Cut Line= 3
     2349625.631      323604.659     2349638.652      323461.429
      2348880.84      322260.909
#Sta/Elev= 30
       0  556.57   159.8  523.51   231.8   518.8   397.1 517.249  433.95517.9075
   443.8  516.92   467.8  504.24   499.7  503.56   550.3 504.069   569.9504.6775
  578.31505.8895   595.7   510.2   671.7  506.63  679.28508.7372   691.7  511.42
   711.7  509.91   807.7  513.51   971.6  511.86  1091.6  514.56  1183.6   512.8
  1223.6  515.74 1282.91514.5179 1327.97514.0782  1379.6  513.07  1419.5  516.48
  1431.5  521.02  1447.5  535.47  1455.5  538.64  1499.5  548.49  1563.5  554.36
#Mann= 10 ,-1 , 0
       0     .06       0   397.1     .12       0  433.95     .04       0
   467.8    .045       0   550.3     .04       0   569.9     .12       0
  578.31     .08       0  679.28     .12       0 1282.91    .016       0
 1327.97     .12       0
Bank Sta=467.8,550.3
XS Rating Curve= 0 ,0
Exp/Cntr=0.3,0.1

Type RM Length L Ch R = 1 ,161173.8,389.5,391.1,392.7
XS GIS Cut Line= 3
     2349850.323      323690.314     2349926.712      323475.036
     2349270.462      322006.286
#Sta/Elev= 30
       0  567.71    31.5  564.47   110.3   549.8   173.3  533.63   220.6   524.9
  330.17517.5012  610.95516.1449   643.6  515.86   659.5  508.92   679.5  512.88
   723.4  503.14   747.4  506.48  781.73504.5638   843.2  502.09   859.1  505.24
   875.1  502.13  946.15504.1915     988501.4637   998.8  500.79  1046.8  501.28
  1058.7   511.5  1070.7  511.99  1138.6  510.55    1390  514.57  1653.5  510.64
  1681.4   516.2  1713.4  536.55  1729.3  542.54  1789.2   549.1  1837.1  559.95
#Mann= 7 ,-1 , 0
       0     .12       0  330.17     .06       0  610.95     .12       0
  781.73     .08       0  946.15     .04       0     988    .045       0
  1046.8     .12       0
Bank Sta=988,1046.8
XS Rating Curve= 0 ,0
Exp/Cntr=0.3,0.1