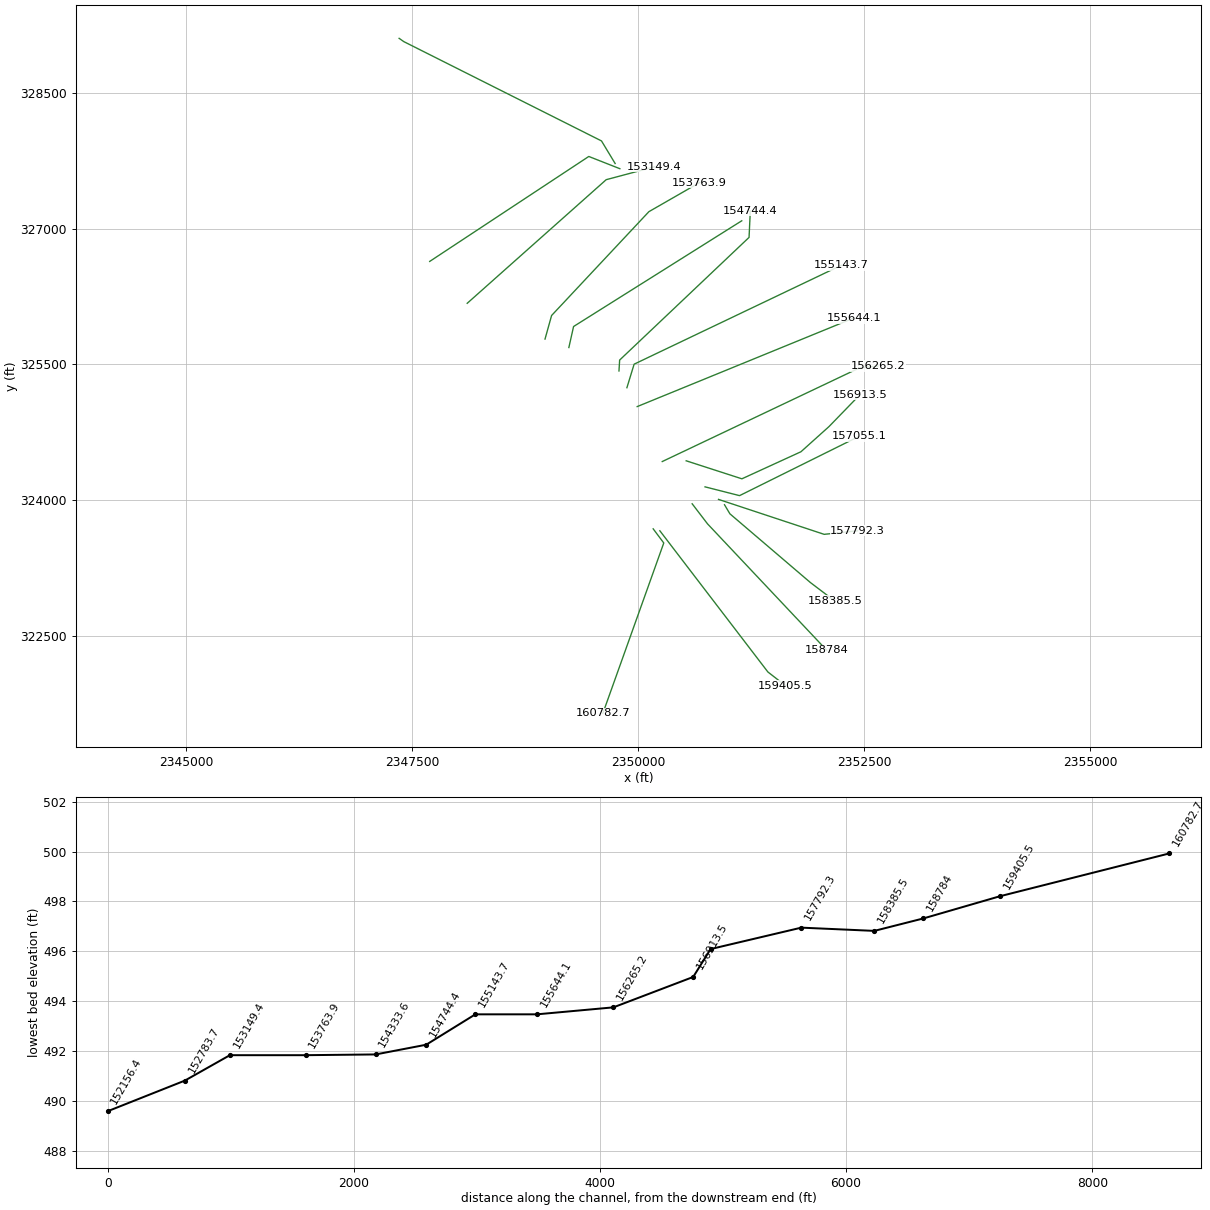
HEC-RAS study BACKCREEK.prj: BACKCREEK

--- BACKCREEK.g01 (geometry) --- (continued)

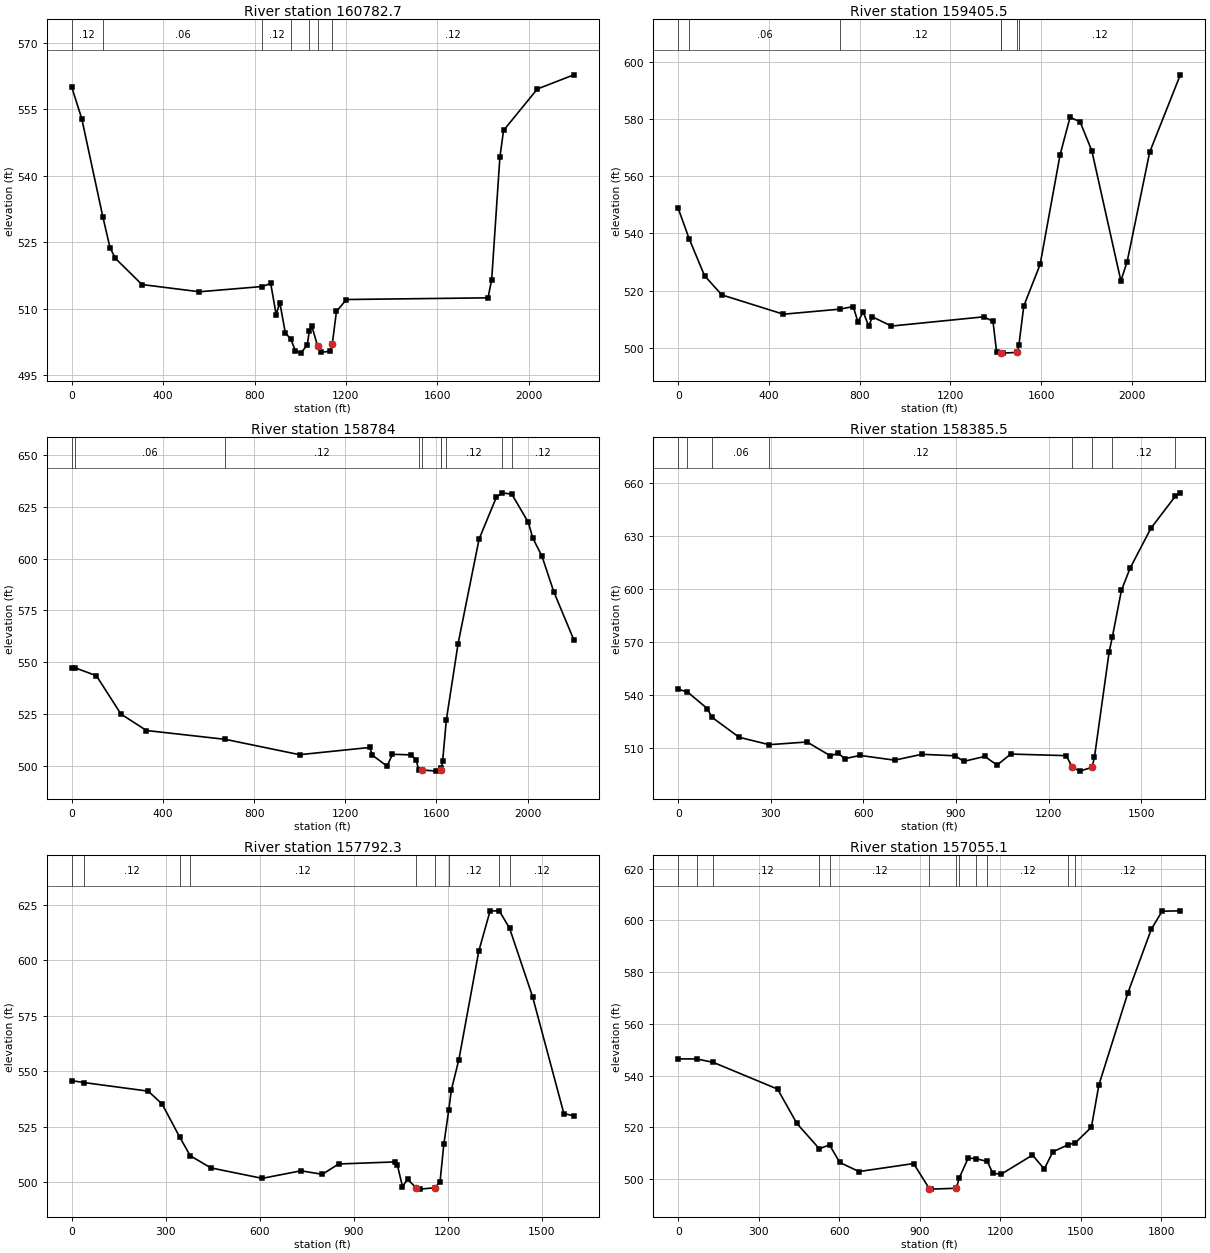
Type RM Length L Ch R = 1 ,160782.7,1338.3,1377.2,1416.2
XS GIS Cut Line= 3
     2350165.374      323680.347     2350282.562      323524.097
     2349608.386      321638.304
#Sta/Elev= 30
       0  559.95    43.8  552.82  136.38530.6167   167.4  523.72   191.3   521.3
   307.2  515.41   559.1  513.78  833.17514.9597   870.9  515.65   894.8  508.64
   910.8  511.33   934.8  504.53  958.83 503.058   978.8  500.49  1002.8  499.93
  1030.8  501.78  1040.1504.9153  1050.8  506.06  1076.6501.4575  1090.7   500.1
  1130.7  500.36 1140.48501.9955  1158.7  509.34  1202.6  512.03  1822.2  512.41
  1838.2  516.45  1874.2  544.12  1890.2  550.19  2038.1  559.54    2198  562.74
#Mann= 7 ,-1 , 0
       0     .12       0  136.38     .06       0  833.17     .12       0
  958.83     .04       0  1040.1     .08       0  1076.6    .045       0
 1140.48     .12       0
Bank Sta=1076.6,1140.48
XS Rating Curve= 0 ,0
Exp/Cntr=0.3,0.1

Type RM Length L Ch R = 1 ,159405.5,614.3,621.5,628.7
XS GIS Cut Line= 3
     2350239.212      323659.064     2351434.752      322096.515
      2351629.22      321945.596
#Sta/Elev= 30
       0  548.73   48.12538.1599     116  525.25     192  518.55   463.9   511.8
  712.69513.5734   771.8  514.47   791.8  509.17   815.8  512.53   839.8  507.63
   855.8  510.89   939.7  507.66  1347.6  510.89  1387.6  509.29  1403.6  498.72
 1422.01498.3401  1423.6  498.36  1431.6  498.21  1495.6  498.48 1502.11501.1317
  1523.6   514.7  1595.6   529.2  1683.5  567.49  1727.5  580.56  1771.5  579.02
  1823.5  568.87  1951.5  523.46  1979.4   530.2  2078.6  568.41  2213.6  595.41
#Mann= 7 ,-1 , 0
       0     .12       0   48.12     .06       0  712.69     .12       0
 1422.01     .04       0  1423.6    .045       0  1495.6     .04       0
 1502.11     .12       0
Bank Sta=1423.6,1495.6
XS Rating Curve= 0 ,0
Exp/Cntr=0.3,0.1

Type RM Length L Ch R = 1 ,158784  ,395.5,398.5,401.9
XS GIS Cut Line= 3
     2350596.851      323957.675      2350766.99      323735.453
     2352086.435      322336.147
#Sta/Elev= 30
       0  547.29   12.52547.2957     108  543.41   215.9  524.87   327.9  516.94
  674.13512.6675   999.6  505.26  1307.5  508.75  1319.5     505  1383.5  499.72
  1407.4  505.46  1487.4  505.18  1511.4  502.88 1521.74497.9363  1535.4  497.91
  1599.4  497.32  1619.4     498 1621.39498.6119  1627.4  502.11 1643.61  522.03
  1695.3  558.92  1787.3  609.38  1863.3  629.67 1889.69631.7549 1931.23631.0721
  2003.2  617.52  2023.2  609.86  2063.2  601.16  2115.2  583.96  2203.2   560.7
#Mann= 10 ,-1 , 0
       0     .12       0   12.52     .06       0  674.13     .12       0
 1521.74     .04       0  1535.4    .045       0  1619.4     .04       0
 1621.39     .08       0 1643.61     .12       0 1889.69    .016       0
 1931.23     .12       0
Bank Sta=1535.4,1619.4
XS Rating Curve= 0 ,0
Exp/Cntr=0.3,0.1

Type RM Length L Ch R = 1 ,158385.5,581.3,593.2,604.6
XS GIS Cut Line= 4
      2350954.49      323947.258     2351014.636      323846.638
     2351905.825      323085.729     2352174.923      322881.736
#Sta/Elev= 30
       0  543.05   29.48 541.664    93.8  532.22  109.36527.2527   197.2  515.97
  294.71511.7675   417.2   513.3   493.2  505.46   517.2  506.87   541.2  503.92
   589.2   505.7   701.1  503.01   789.1  506.34   897.1  505.49   925.1  502.33
   993.1  505.13  1033.1  500.24  1077.1  506.47  1257.1  505.57  1277.1  498.92
    1301  496.82  1340.7  498.96  1348.6  504.74  1396.3   564.4 1406.61572.7257
    1436   599.1  1463.9  611.55  1531.4  634.14 1610.36652.2286  1626.7  654.19
#Mann= 8 ,-1 , 0
       0     .12       0   29.48    .016       0  109.36     .06       0
  294.71     .12       0  1277.1    .045       0  1340.7     .04       0
 1406.61     .12       0 1610.36    .016       0
Bank Sta=1277.1,1340.7
XS Rating Curve= 0 ,0
Exp/Cntr=0.3,0.1

Type RM Length L Ch R = 1 ,157792.3,706.8,737.3,767.7
XS GIS Cut Line= 3
     2350888.518      324006.286     2352057.735      323619.583
     2352426.659      323658.646
#Sta/Elev= 30
       0  545.79   40.41544.9038   243.9  541.07   287.9  535.36   345.1 520.242
   378.1511.9833   443.8  506.52   607.8   501.8   731.7   505.2   799.7  503.62
   851.7  508.27  1031.6   509.2  1039.6   507.6  1055.6  498.08  1071.6  501.36
  1099.6  497.55  1111.6  496.95  1159.5  497.57  1175.5  500.35  1187.5  517.16
 1203.36532.6519  1211.5  541.64  1235.5  555.23  1299.3  604.23  1335.2  622.21
 1364.53622.2579 1397.43614.3912  1470.8  583.58  1570.6     531  1602.5  529.93
#Mann= 9 ,-1 , 0
       0     .06       0   40.41     .12       0   345.1    .016       0
   378.1     .12       0  1099.6    .045       0  1159.5     .04       0
 1203.36     .12       0 1364.53    .016       0 1397.43     .12       0
Bank Sta=1099.6,1159.5
XS Rating Curve= 0 ,0
Exp/Cntr=0.3,0.1

Type RM Length L Ch R = 1 ,157055.1,142.6,141.5,140.3
XS GIS Cut Line= 3
     2350739.212      324145.175     2351121.157      324047.953
     2352444.073      324704.203
#Sta/Elev= 30
       0  546.47   68.44546.4496  130.41545.1221   370.2  534.78     442   521.5
  525.91511.6849  563.66513.2357   601.7  506.42   673.5  502.89   877.1  505.98
  935.62496.2544   940.9  496.09  1036.7  496.43 1046.78500.3512  1080.6  508.11
  1109.3507.8828 1151.72506.7878  1172.4  502.16  1204.3  501.92  1320.1  509.26
    1364  503.86  1395.9  510.53 1452.93513.2634 1479.32513.9848  1539.6  520.04
  1567.5  536.39  1675.3  571.92  1763.1  596.68    1803  603.58  1870.9  603.73
#Mann= 12 ,-1 , 0
       0     .12       0   68.44     .06       0  130.41     .12       0
  525.91    .016       0  563.66     .12       0  935.62    .045       0
  1036.7     .04       0 1046.78     .12       0  1109.3    .016       0
 1151.72     .12       0 1452.93    .016       0 1479.32     .12       0
#XS Ineff= 2 , 0
       0     650            1092       0
Permanent Ineff=
       F       F
Bank Sta=935.62,1036.7
XS Rating Curve= 0 ,0
Exp/Cntr=0.3,0.1

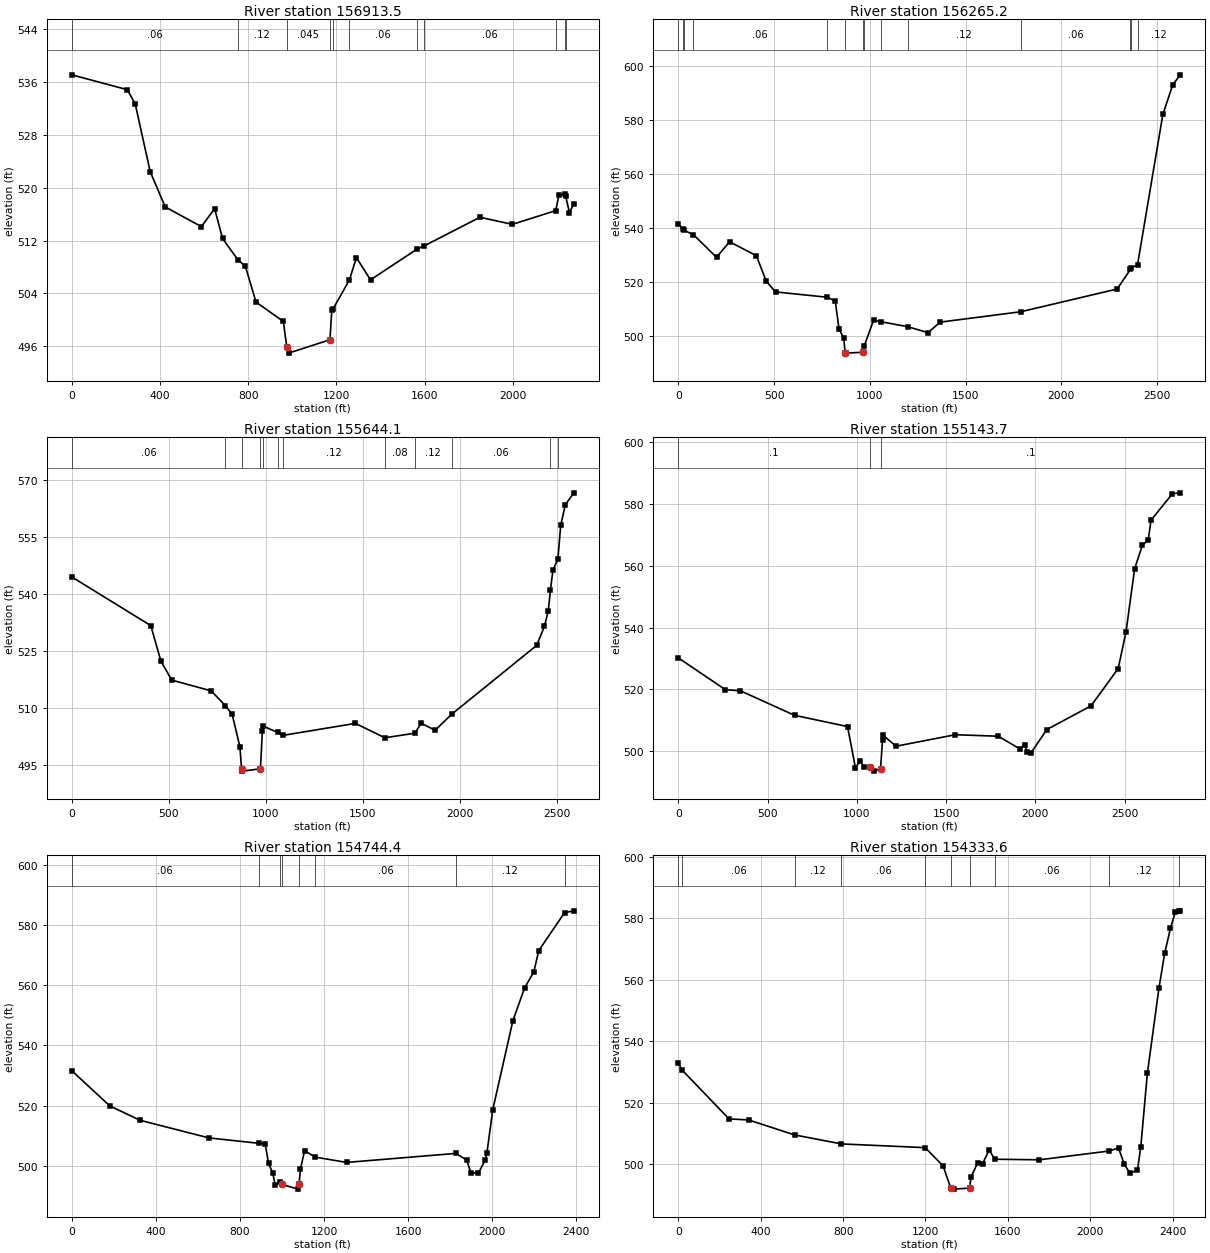
Type RM Length L Ch R = 1 ,156913.5,648.3,648.3,648.4
XS GIS Cut Line= 5
     2350530.879      324433.369     2351147.145      324234.166
     2351800.791      324533.646      2352110.74      324811.842
      2352454.49      325166.008
#Sta/Elev= 30
       0  537.09   251.9  534.84   287.8  532.67   355.8  522.42   423.8   517.1
   587.7  514.11   647.7  516.84   683.6  512.33  753.01509.1107   787.5   508.1
   835.4   502.7   959.2  499.77   975.2  495.85   983.2  494.97  1170.9     497
  1178.9  501.45 1185.36501.6985 1258.82506.0318  1290.8  509.42  1354.7  506.06
 1565.84510.7193 1596.21  511.17  1850.8  515.53  1998.1  514.46 2194.64  516.54
    2209  518.91  2236.4519.0525 2239.27518.7612  2256.8  516.25  2276.7  517.56
#Mann= 11 ,-1 , 0
       0     .06       0  753.01     .12       0   975.2    .045       0
  1170.9     .04       0 1185.36     .12       0 1258.82     .06       0
 1565.84     .12       0 1596.21     .06       0 2194.64    .016       0
  2236.4     .06       0 2239.27     .12       0
#XS Ineff= 2 , 0
       0     903            1303       0
Permanent Ineff=
       F       F
Bank Sta=975.2,1170.9
XS Rating Curve= 0 ,0
Exp/Cntr=0.3,0.1

Type RM Length L Ch R = 1 ,156265.2,623,621.1,619.3
XS GIS Cut Line= 3
     2350265.755      324425.161     2352447.546      325461.147
     2352652.407       325481.98
#Sta/Elev= 30
       0  541.53   26.51539.5321   28.28539.2417   79.21537.5717   199.9  529.18
   267.9  534.94   407.9  529.79   459.9  520.29   507.8  516.39  776.51514.4311
   819.8  513.08   839.7   502.5   863.7  499.46   871.7  493.97   875.7  493.75
  965.06494.0788  970.58496.3048  1019.7   505.9 1056.23505.3901  1197.2  503.54
  1303.6  501.32  1367.6  505.21 1787.89509.0469  2291.3  517.46 2361.14524.7463
 2364.75525.3051 2397.69526.3676  2530.1  582.05  2581.6  592.97  2621.2  596.68
#Mann= 14 ,-1 , 0
       0     .06       0   26.51     .08       0   28.28    .016       0
   79.21     .06       0  776.51     .12       0   871.7    .045       0
  965.06     .04       0  970.58     .12       0 1056.23     .06       0
  1197.2     .12       0 1787.89     .06       0 2361.14     .12       0
 2364.75    .016       0 2397.69     .12       0
Bank Sta=871.7,965.06
XS Rating Curve= 0 ,0
Exp/Cntr=0.3,0.1

Type RM Length L Ch R = 1 ,155644.1,498.3,500.4,502.6
XS GIS Cut Line= 2
      2349988.59      325033.364     2352385.046       326013.23
#Sta/Elev= 30
       0  544.45   407.5  531.67   459.5  522.37   515.4  517.37   719.2  514.54
  792.02510.6456   827.1  508.38     867  499.85  875.39494.0747     879  493.47
  972.86494.0729   982.9  503.99  987.96505.2596 1061.19503.6321 1086.75  502.84
  1462.3     506 1614.26502.2348 1768.71503.4129  1801.9  506.04  1873.9   504.2
 1958.92508.3976  2397.3  526.48  2437.2  531.45  2457.2  535.57 2468.49541.0648
  2481.2  546.26 2506.81549.0854  2521.1  557.98  2545.1  563.42    2589  566.53
#Mann= 12 ,-1 , 0
       0     .06       0  792.02     .12       0  875.39    .045       0
  972.86     .04       0  987.96     .12       0 1061.19     .06       0
 1086.75     .12       0 1614.26     .08       0 1768.71     .12       0
 1958.92     .06       0 2468.49    .016       0 2506.81     .12       0
Bank Sta=875.39,972.86
XS Rating Curve= 0 ,0
Exp/Cntr=0.3,0.1

Type RM Length L Ch R = 1 ,155143.7,387.5,399.3,411
XS GIS Cut Line= 3
     2349874.629      325242.397      2349954.49      325502.814
     2352246.157      326596.564
#Sta/Elev= 30
       0  530.19   264.5  519.86   348.4   519.5   652.3  511.54   948.2  507.92
   992.2  494.55  1020.2  496.85  1040.2  494.69  1073.2  494.87  1096.2  493.47
 1132.86494.2912  1144.2  503.63  1148.1  505.02  1220.1  501.55    1552  505.27
    1792  504.78  1911.9  500.73  1939.9  501.97  1955.9   499.6  1975.9   499.4
  2063.9  506.94  2311.8  514.63  2463.8  526.72  2507.8  538.69  2555.8  559.05
  2599.7  566.77  2631.7   568.3  2647.7  574.81  2767.7   583.4  2811.7  583.67
#Mann= 3 , 0 , 0
       0      .1       0  1073.2    .045       0 1132.86      .1       0
Bank Sta=1073.2,1132.86
XS Rating Curve= 0 ,0
Exp/Cntr=0.3,0.1

Type RM Length L Ch R = 1 ,154744.4,418.2,410.8,403.3
XS GIS Cut Line= 4
     2349786.864      325427.762      2349794.21      325548.319
      2351226.42      326905.809     2351240.172      327199.394
#Sta/Elev= 30
       0  531.59   180.7  519.91   324.5  515.13   652.1  509.27  888.44507.4805
   919.7  507.37   935.7  500.83   955.6  497.68   967.6  493.63  991.98494.5448
   998.2 493.872  1075.5  492.25 1081.41494.0993  1087.5  498.84  1107.4  505.02
  1157.7502.8896  1307.2  501.12    1826504.1113  1878.4  501.94  1898.4  497.59
  1934.3  497.65  1966.3  501.85  1974.3  504.12  2002.2  518.58  2098.1  548.22
  2153.7  559.09  2197.4  564.39  2221.2   571.5 2343.58584.0822    2388  584.71
#Mann= 8 ,-1 , 0
       0     .06       0  888.44     .12       0  991.98     .04       0
   998.2    .045       0 1081.41     .12       0  1157.7     .06       0
    1826     .12       0 2343.58     .06       0
Bank Sta=998.2,1081.41
XS Rating Curve= 0 ,0
Exp/Cntr=0.3,0.1

Type RM Length L Ch R = 1 ,154333.6,560.2,569.8,579.4
XS GIS Cut Line= 3
     2349232.268      325686.842     2349284.351       325919.48
     2351145.462      327089.619
#Sta/Elev= 30
       0  532.88   18.88530.6171   246.4  514.73   342.3  514.37  564.76 509.506
  792.31506.5764 1198.58  505.37  1285.6  499.39  1321.6  492.37  1337.6  491.86
 1413.76492.1932  1421.5  495.86  1453.5  500.51  1477.5  500.19  1509.5   504.7
 1535.07501.5904  1753.3  501.41 2088.68504.2483    2137  505.23    2165  499.94
    2193  497.01    2229   498.1  2244.9  505.57  2276.9  529.59  2332.9  557.19
  2360.8   568.6  2388.8  576.76  2412.8  582.13 2430.76582.4428  2436.8  582.47
#Mann= 10 ,-1 , 0
       0     .12       0   18.88     .06       0  564.76     .12       0
  792.31     .06       0 1198.58     .12       0  1321.6    .045       0
 1413.76     .12       0 1535.07     .06       0 2088.68     .12       0
 2430.76     .08       0
Bank Sta=1321.6,1413.76
XS Rating Curve= 0 ,0
Exp/Cntr=0.3,0.1

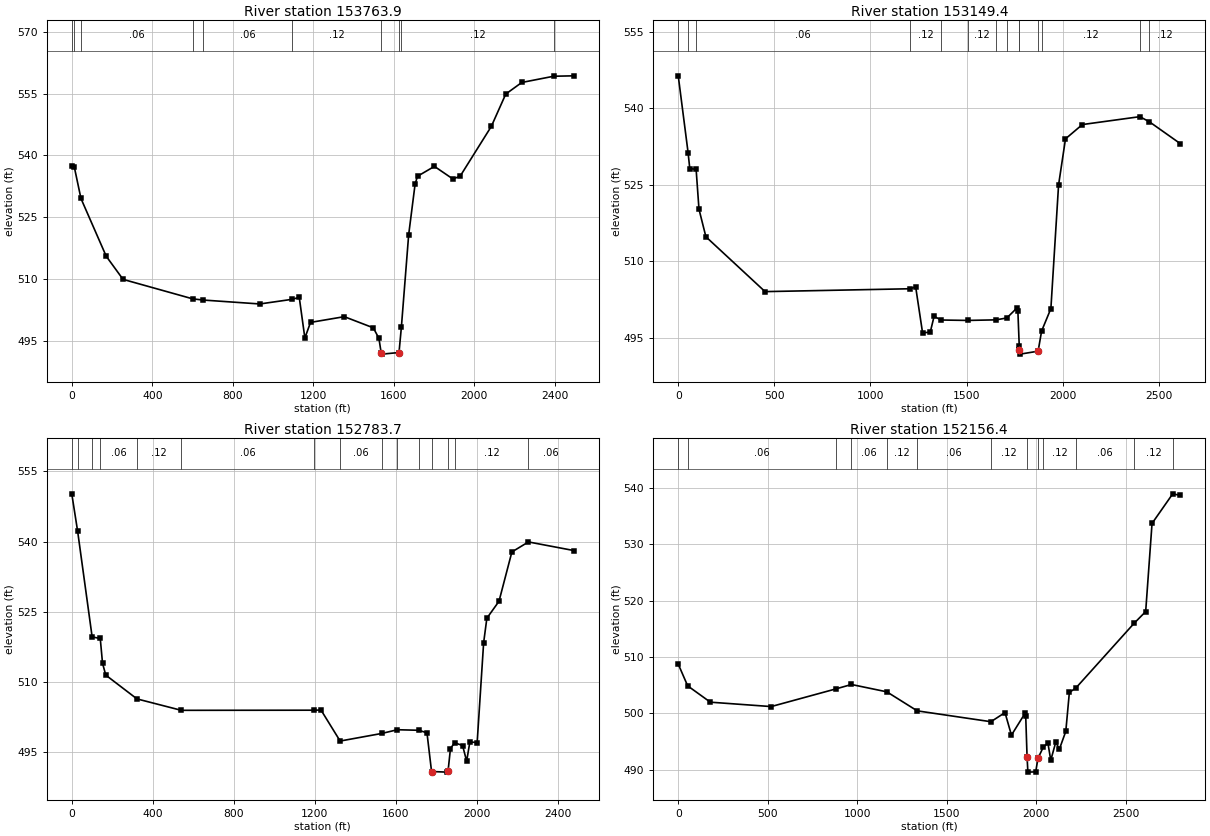
Type RM Length L Ch R = 1 ,153763.9,617.7,614.5,611.1
XS GIS Cut Line= 4
     2348968.379      325780.592     2349041.023       326041.27
     2350117.685      327190.314     2350680.185       327513.23
#Sta/Elev= 30
       0  537.33   12.21537.2742   45.65 529.556   171.1  515.56   254.7  509.95
  600.73505.2281  652.51504.9407     934  503.99 1095.19505.1203  1129.9   505.6
  1157.8  495.72  1185.8  499.52  1353.7  500.91  1497.6  498.21  1525.5  495.67
 1537.19492.0315  1541.5  491.83  1625.4  492.22  1637.2498.3965  1673.4  520.79
  1705.4  533.08  1717.4  534.95  1801.3  537.34    1893  534.29  1928.8  534.94
    2084  547.04  2155.6  554.87  2235.2  557.68  2393.9559.1919  2493.8  559.29
#Mann= 10 ,-1 , 0
       0     .06       0   12.21     .12       0   45.65     .06       0
  600.73     .12       0  652.51     .06       0 1095.19     .12       0
 1537.19    .045       0  1625.4     .04       0  1637.2     .12       0
  2393.9     .06       0
Bank Sta=1537.19,1625.4
XS Rating Curve= 0 ,0
Exp/Cntr=0.3,0.1

Type RM Length L Ch R = 1 ,153149.4,371.1,365.7,360.2
XS GIS Cut Line= 3
     2348107.268      326176.425     2349645.462       327544.48
     2350180.185      327686.842
#Sta/Elev= 30
       0  546.37    51.3531.3082      60   528.2   93.04528.0496   107.9  520.23
   143.9  514.83   451.7  504.08 1207.03504.6418  1235.1  505.02  1271.1  495.99
  1311.1  496.15  1331.1  499.25 1366.52498.5172 1506.64498.4334 1653.69498.5489
  1709.5  498.92  1762.8   500.9  1766.8  500.35 1774.07493.3392  1774.8   492.6
  1778.7  491.83 1872.19492.4056  1890.3  496.35  1938.6  500.76  1978.6  524.99
  2014.6  534.02  2102.3  536.82 2401.24538.3664 2451.06537.3616  2611.9  533.08
#Mann= 14 ,-1 , 0
       0     .12       0    51.3    .016       0   93.04     .06       0
 1207.03     .12       0 1366.52     .06       0 1506.64     .12       0
 1653.69     .06       0  1709.5     .12       0 1774.07     .04       0
  1774.8    .045       0 1872.19     .04       0  1890.3     .12       0
 2401.24    .016       0 2451.06     .12       0
Bank Sta=1774.8,1872.19
XS Rating Curve= 0 ,0
Exp/Cntr=0.3,0.1

Type RM Length L Ch R = 1 ,152783.7,666.8,627.4,587.9
XS GIS Cut Line= 3
     2347692.337      326639.967     2349452.754      327801.425
     2349796.504      327666.008
#Sta/Elev= 30
       0  550.18   29.09542.1575  100.54519.6558  140.65519.3175   151.8  514.04
   167.8  511.51  321.73506.4322  540.67503.9949 1195.35504.0221  1230.3  504.06
  1324.8497.4417 1531.07499.0681  1607.2499.8556 1713.39499.7363  1753.5  499.19
 1776.07490.9416  1853.4  490.81  1857.4  490.96  1869.4  495.85 1889.98497.0797
  1929.3  496.48  1949.3  493.14  1965.2  497.25  2001.2  497.12  2033.2  518.43
  2049.1  523.64    2109  527.26  2172.6  537.78 2254.24539.9178  2478.5  538.08
#Mann= 15 ,-1 , 0
       0     .06       0   29.09     .12       0  100.54    .016       0
  140.65     .06       0  321.73     .12       0  540.67     .06       0
 1195.35     .12       0  1324.8     .06       0 1531.07     .12       0
  1607.2     .06       0 1713.39     .12       0 1776.07    .045       0
  1857.4     .04       0 1889.98     .12       0 2254.24     .06       0
Bank Sta=1776.07,1857.4
XS Rating Curve= 0 ,0
Exp/Cntr=0.3,0.1

Type RM Length L Ch R = 1 ,152156.4,670.2,663.1,656.1
XS GIS Cut Line= 4
     2347353.796      329108.717     2347405.879      329072.258
     2349593.379        327973.3     2349744.421        327723.3
#Sta/Elev= 30
       0  508.76   52.66504.9005   179.4     502   518.8  501.22  881.95504.3722
  967.43505.1399 1165.01503.8357 1334.46500.4604 1745.94498.5315  1824.7  500.15
  1860.7  496.15  1936.5  500.02  1940.5  499.47 1947.94 492.312  1952.5  489.58
  1996.4  489.63  2008.4  492.01 2038.49494.0114  2064.3  494.75  2080.3  491.69
  2108.3  494.91  2128.2  493.64  2164.2  496.82  2184.1  503.72 2221.26504.5461
 2546.14516.0241  2610.3  518.09  2645.8  533.74  2761.3538.9959  2803.7  538.72
#Mann= 13 ,-1 , 0
       0    .016       0   52.66     .06       0  881.95     .08       0
  967.43     .06       0 1165.01     .12       0 1334.46     .06       0
 1745.94     .12       0 1947.94    .045       0  2008.4     .04       0
 2038.49     .12       0 2221.26     .06       0 2546.14     .12       0
  2761.3     .06       0
Bank Sta=1947.94,2008.4
XS Rating Curve= 0 ,0
Exp/Cntr=0.3,0.1