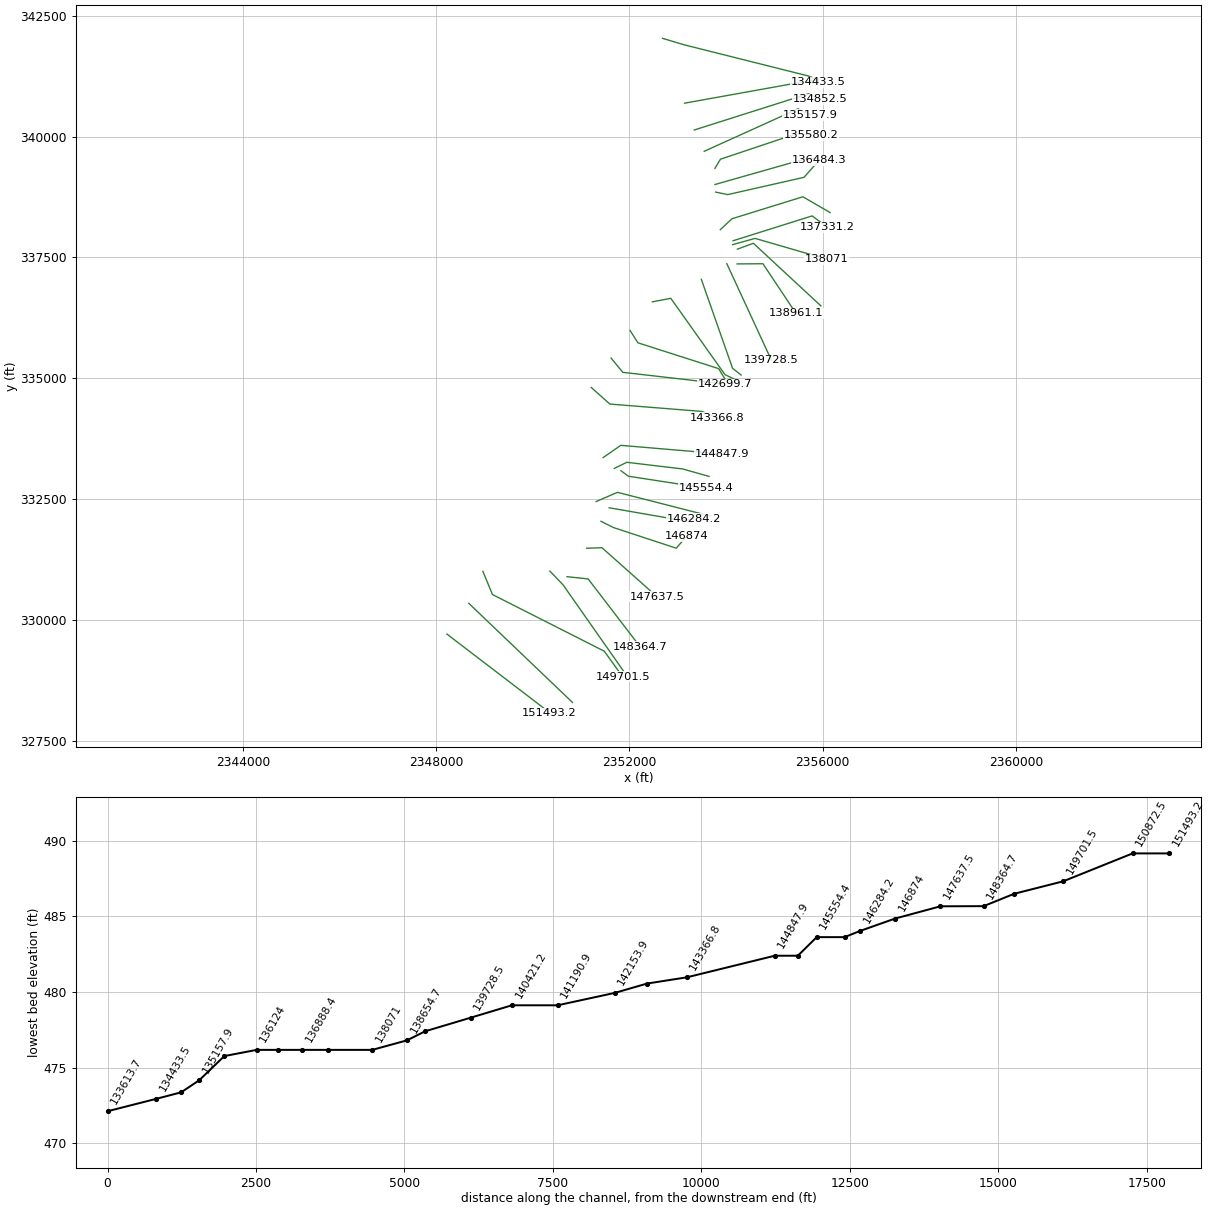
HEC-RAS study BACKCREEK.prj: BACKCREEK

--- BACKCREEK.g01 (geometry) --- (continued)

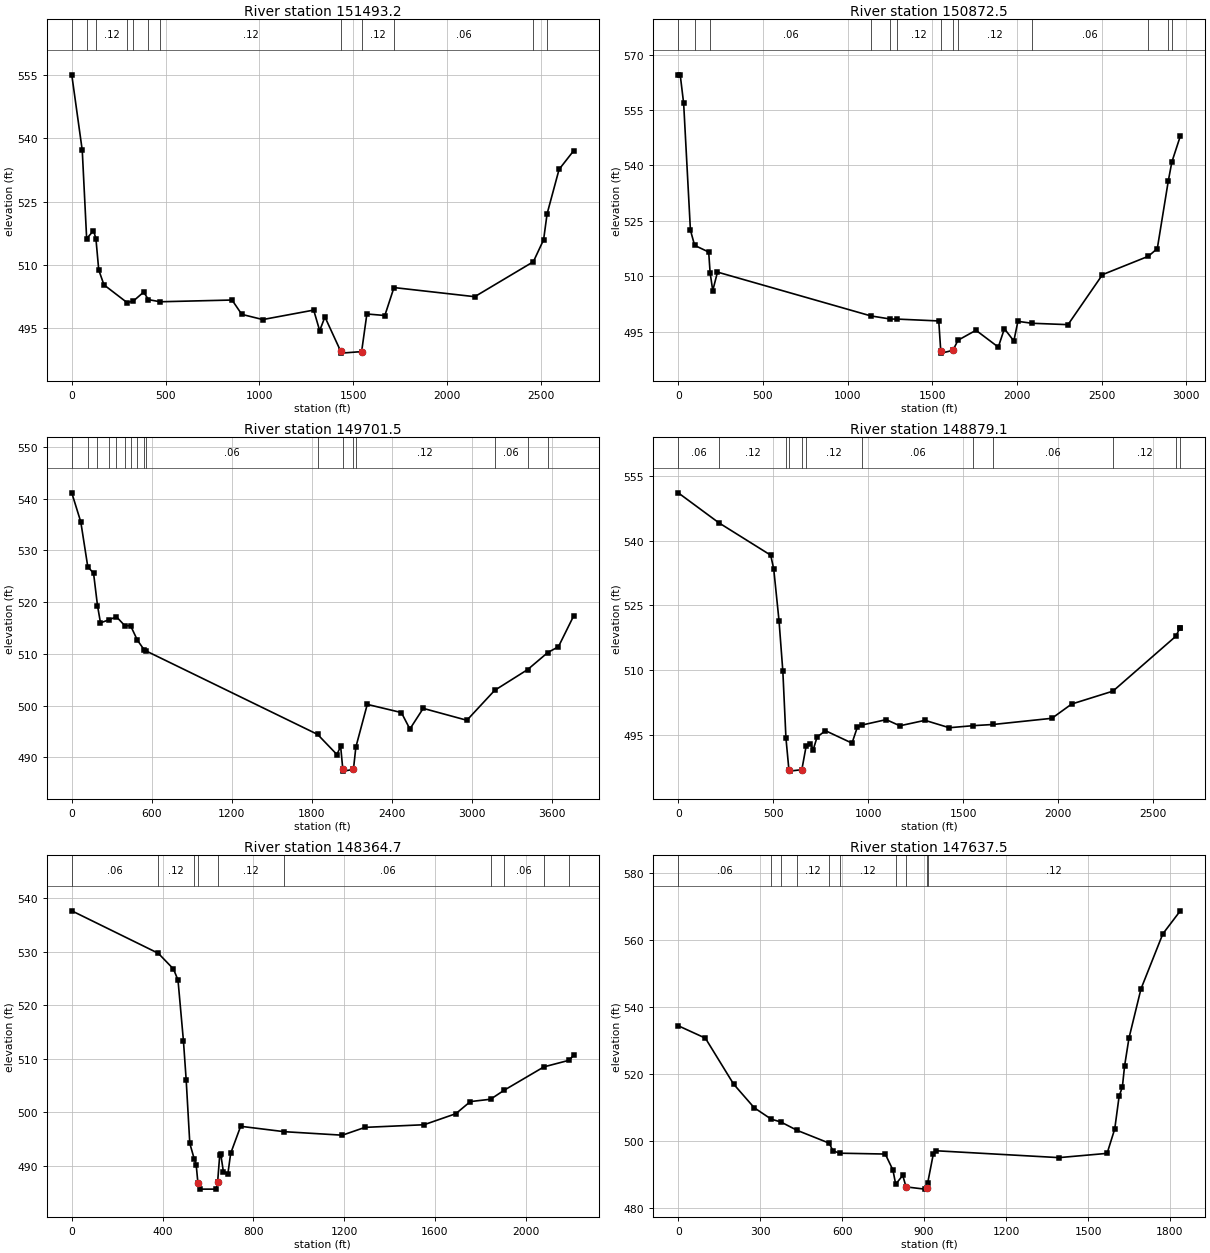
Type RM Length L Ch R = 1 ,151493.2,623.2,620.7,618.3
XS GIS Cut Line= 3
     2348223.587      329707.675     2350213.171      328186.842
     2350338.171       328067.05
#Sta/Elev= 30
       0     555    55.9  537.14   79.35516.2521   115.8  518.13  128.71516.2806
   143.8  508.85   171.7  505.32  294.67 501.133  327.85501.4748   383.4  503.61
  408.97501.8181  471.67501.3207   854.7  501.73   906.6  498.34  1018.5  497.11
  1290.1  499.35    1322  494.48    1350  497.72  1433.9  489.63  1437.9  489.17
  1545.7  489.53  1573.7  498.43  1669.5  498.07 1718.19504.6794  2148.8  502.52
 2461.37510.7849  2516.1  515.98  2534.7 522.114  2598.7  532.64  2677.4   537.1
#Mann= 12 ,-1 , 0
       0     .12       0   79.35    .016       0  128.71     .12       0
  294.67     .06       0  327.85     .12       0  408.97     .06       0
  471.67     .12       0  1433.9    .045       0  1545.7     .12       0
 1718.19     .06       0 2461.37     .12       0  2534.7     .06       0
Bank Sta=1433.9,1545.7
XS Rating Curve= 0 ,0
Exp/Cntr=0.3,0.1

Type RM Length L Ch R = 1 ,150872.5,1161.9,1171,1180
XS GIS Cut Line= 2
     2348676.712      330343.092     2350819.888       328294.93
#Sta/Elev= 30
       0  564.52      12  564.39      32  556.76    71.9  522.49   96.71 518.348
   179.8  516.54  188.17510.9966   203.8  506.09   231.7  511.11 1137.44499.2455
  1252.7   498.4 1290.14 498.393  1538.2  497.88  1550.2  489.64  1554.2  489.17
  1622.1  489.93 1651.77492.6568  1757.9  495.36  1889.8   490.8  1925.7  495.79
  1981.6  492.46  2005.6  497.78 2087.98 497.257  2301.3  496.88    2505  510.42
 2775.53 515.392  2828.6  517.47 2893.61535.8135 2914.63540.9284  2964.5  547.92
#Mann= 13 ,-1 , 0
       0     .12       0   96.71    .016       0  188.17     .06       0
 1137.44     .08       0  1252.7     .06       0 1290.14     .12       0
  1550.2    .045       0  1622.1     .04       0 1651.77     .12       0
 2087.98     .06       0 2775.53     .12       0 2893.61     .06       0
 2914.63     .12       0
Bank Sta=1550.2,1622.1
XS Rating Curve= 0 ,0
Exp/Cntr=0.3,0.1

Type RM Length L Ch R = 1 ,149701.5,839.9,822.4,804.8
XS GIS Cut Line= 4
     2348968.379       331004.55     2349166.296      330525.383
     2351478.796      329353.508     2351861.555      328822.708
#Sta/Elev= 30
       0  541.11    67.8  535.47  119.83526.8583   163.5  525.55  192.87519.3149
   215.4  515.98  278.71516.5678  335.04517.1542  397.23515.4448  441.42515.4068
  492.78 512.596  543.32510.7613  554.47510.5829 1843.52 494.417  1988.4  490.53
  2016.4  492.11  2032.4  487.75  2036.4  487.32  2112.3  487.65 2130.54491.9646
  2216.1  500.22  2471.8  498.64  2535.7  495.46  2635.6  499.45  2963.1  497.15
 3171.49502.9321 3419.08506.9516    3570510.2473  3649.6  511.36  3765.3  517.39
#Mann= 17 ,-1 , 0
       0     .06       0  119.83    .016       0  192.87     .06       0
  278.71     .08       0  335.04     .06       0  397.23    .016       0
  441.42     .08       0  492.78     .06       0  543.32     .12       0
  554.47     .06       0 1843.52     .12       0  2032.4    .045       0
  2112.3     .04       0 2130.54     .12       0 3171.49     .06       0
 3419.08     .12       0    3570     .06       0
Bank Sta=2032.4,2112.3
XS Rating Curve= 0 ,0
Exp/Cntr=0.3,0.1

Type RM Length L Ch R = 1 ,148879.1,513.3,514.4,515.6
XS GIS Cut Line= 3
     2350353.796      331009.758     2350624.629      330728.508
      2351917.11      328885.208
#Sta/Elev= 30
       0  551.14  214.11544.1678   486.4  536.66   502.4  533.46   530.4  521.39
   550.4  509.68  566.74494.1573   582.4  486.76   586.4   486.5   650.4  486.84
  672.77492.2558   694.4   492.9   710.4   491.5   730.3  494.39   774.3   495.9
   914.3     493   942.3   496.7  967.93497.2163  1094.2  498.46  1166.2  497.03
  1298.2   498.3  1426.1  496.58 1552.95497.0641 1656.27497.3314    1966  498.77
  2069.9  502.08 2287.28505.0811 2618.27 517.832 2639.42519.7371  2641.7  519.72
#Mann= 12 ,-1 , 0
       0     .06       0  214.11     .12       0  566.74     .04       0
   582.4    .045       0   650.4     .04       0  672.77     .12       0
  967.93     .06       0 1552.95     .12       0 1656.27     .06       0
 2287.28     .12       0 2618.27     .06       0 2639.42     .12       0
Bank Sta=582.4,650.4
XS Rating Curve= 0 ,0
Exp/Cntr=0.3,0.1

Type RM Length L Ch R = 1 ,148364.7,720.2,727.2,734.3
XS GIS Cut Line= 3
     2350707.962      330895.175     2351145.462        330848.3
     2352223.587       329442.05
#Sta/Elev= 30
       0  537.59  381.21529.6672     448  526.74     468  524.67     492  513.32
     504  506.08     520  494.22  539.89491.2508     548  490.25     556  486.75
     564  485.68     636  485.68  642.62487.0225     652  492.12     656  492.26
     668  488.95     688  488.59     700  492.34     744   497.4  935.76496.3959
    1192  495.74    1292   497.2    1552  497.69    1692  499.75    1756  502.01
 1844.94502.4453 1905.23504.1315 2080.16508.4828 2192.15509.7276    2212  510.74
#Mann= 10 ,-1 , 0
       0     .06       0  381.21     .12       0  539.89     .04       0
     556    .045       0  642.62     .12       0  935.76     .06       0
 1844.94     .12       0 1905.23     .06       0 2080.16     .12       0
 2192.15    .016       0
Bank Sta=556,642.62
XS Rating Curve= 0 ,0
Exp/Cntr=0.3,0.1

Type RM Length L Ch R = 1 ,147637.5,747.7,763.5,779.3
XS GIS Cut Line= 3
     2351114.212      331483.717     2351431.921      331494.133
     2352567.337      330483.717
#Sta/Elev= 30
       0  534.47    99.3  530.77   202.6  517.05   278.1  509.98  340.33506.5714
  375.41505.7351  435.61503.2128   552.7 499.399   565.9  497.14  590.65 496.405
   757.8  496.15   785.8  491.39  795.95487.1314   821.8  489.78   833.8  486.34
   901.8  485.67   909.8  486.03  913.07487.4933   933.8  496.21   941.8  497.14
  1393.8  495.08  1569.8  496.35  1597.8  503.66  1613.8  513.39  1625.8  516.24
  1633.8  522.46  1649.8  530.75  1693.8  545.47  1773.8  561.92  1837.8   568.8
#Mann= 10 ,-1 , 0
       0     .06       0  340.33     .12       0  375.41     .06       0
  435.61     .12       0   552.7     .06       0  590.65     .12       0
  795.95     .04       0   833.8    .045       0   909.8     .04       0
  913.07     .12       0
Bank Sta=833.8,909.8
XS Rating Curve= 0 ,0
Exp/Cntr=0.3,0.1

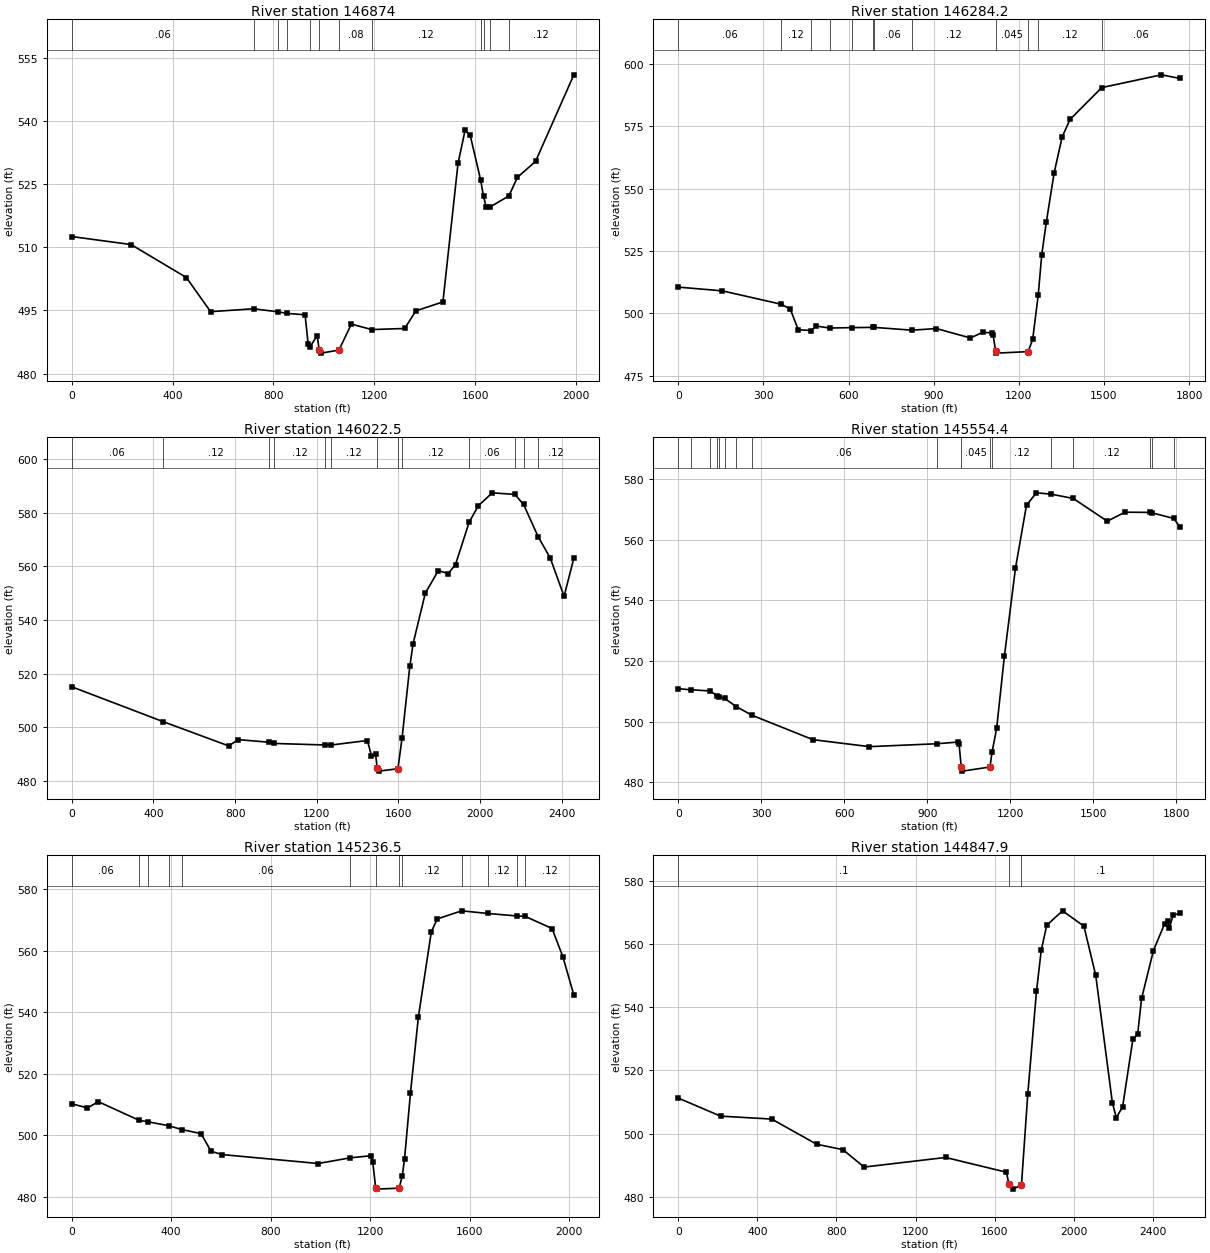
Type RM Length L Ch R = 1 ,146874  ,584.4,589.7,595.1
XS GIS Cut Line= 4
     2351411.087      332041.008     2351671.504        331910.8
     2352967.972      331484.285     2353188.865      331737.189
#Sta/Elev= 30
       0  512.53   235.3  510.63   454.8   502.8   550.6   494.7  721.13  495.39
  818.17  494.66   852.4 494.292   925.7  493.96   937.6  487.05   943.6486.2025
   973.6  489.02   981.6  485.54   989.5  484.86 1060.06485.5852  1109.2  491.75
 1189.81490.4523  1320.8  490.71  1364.7  494.88  1472.4  497.02  1532.3  529.88
  1560.2  537.72  1580.2  536.68 1622.16 525.928 1633.47 522.088    1644  519.57
 1661.04519.6162 1733.96 522.166  1767.9  526.58  1839.9  530.38  1991.8  550.92
#Mann= 12 ,-1 , 0
       0     .06       0  721.13     .08       0  818.17     .06       0
   852.4     .12       0   943.6     .04       0   981.6    .045       0
 1060.06     .08       0 1189.81     .12       0 1622.16     .04       0
 1633.47     .12       0 1661.04     .04       0 1733.96     .12       0
Bank Sta=981.6,1060.06
XS Rating Curve= 0 ,0
Exp/Cntr=0.3,0.1

Type RM Length L Ch R = 1 ,146284.2,264.8,261.7,258.9
XS GIS Cut Line= 3
     2351581.226      332320.522     2353098.587      332056.633
     2353324.282      332094.828
#Sta/Elev= 30
       0  510.51   155.6  509.01  363.04503.6323     395  501.66   422.9  493.41
  468.23493.1109   486.8  494.89  533.52   494.1  611.29494.2638  686.86494.3628
  689.32494.3751  822.56493.2466   909.7  493.88  1029.4  490.13  1073.3   492.4
  1105.2  492.13  1109.2  491.39 1118.51484.7663  1121.2  484.04  1232.9  484.64
  1248.9  489.59 1268.37507.3106  1280.8   523.5  1296.8  536.55  1324.7  556.46
  1352.6  570.69  1380.5  577.76 1492.04590.5012    1702  595.63    1769  594.16
#Mann= 12 ,-1 , 0
       0     .06       0  363.04     .12       0  468.23     .06       0
  533.52     .08       0  611.29     .06       0  686.86     .08       0
  689.32     .06       0  822.56     .12       0 1118.51    .045       0
  1232.9     .04       0 1268.37     .12       0 1492.04     .06       0
Bank Sta=1118.51,1232.9
XS Rating Curve= 0 ,0
Exp/Cntr=0.3,0.1

Type RM Length L Ch R = 1 ,146022.5,464.2,468.1,471.6
XS GIS Cut Line= 3
     2351310.393      332448.994     2351751.365      332639.967
     2353668.964        332150.4
#Sta/Elev= 30
       0   515.1  446.17502.1348   768.4  493.05   816.4  495.38  967.36494.4083
  992.51 493.957 1240.82493.3833 1267.72493.3488  1448.1  495.05  1468.1  489.45
  1488.1  490.12  1496.1   484.8  1504.1  483.63 1597.81484.5219 1618.09 495.996
    1656  522.72    1672  531.16    1732  550.06    1796  558.48  1843.9  557.32
  1879.9  560.72 1946.65576.5156  1991.9  582.67  2059.8  587.48 2170.44586.8917
 2213.31 583.162 2285.39570.9811  2343.7   563.2  2411.7  548.87  2459.6  563.08
#Mann= 13 ,-1 , 0
       0     .06       0  446.17     .12       0  967.36     .06       0
  992.51     .12       0 1240.82     .06       0 1267.72     .12       0
  1496.1    .045       0 1597.81     .04       0 1618.09     .12       0
 1946.65     .06       0 2170.44     .12       0 2213.31     .06       0
 2285.39     .12       0
#XS Ineff= 2 , 0
       0     750                       0
Permanent Ineff=
       F       F
Bank Sta=1496.1,1597.81
XS Rating Curve= 0 ,0
Exp/Cntr=0.3,0.1

Type RM Length L Ch R = 1 ,145554.4,316.3,317.9,319.4
XS GIS Cut Line= 3
     2351824.282      333087.883      2351977.06        332973.3
     2353581.226      332726.772
#Sta/Elev= 30
       0  510.82   45.41  510.48  115.92510.0849  140.62508.4138  146.04508.2377
  167.75 507.616  209.39504.9482  265.49502.1093   486.8  494.01   690.7  491.71
   933.6492.6597  1010.5  493.22  1014.5  492.69  1022.5     485  1026.5  483.63
  1126.4  484.99 1133.77489.9008  1150.4  497.73  1178.4  521.56  1218.3  550.52
  1258.3  571.43  1294.3  575.47  1348.2575.0233 1427.16573.6104  1550.1  566.11
  1614.1  569.08 1702.75569.0119 1713.27568.8292 1789.75567.0294    1814  564.07
#Mann= 17 ,-1 , 0
       0    .016       0   45.41     .06       0  115.92     .12       0
  140.62     .06       0  146.04     .12       0  167.75     .06       0
  209.39    .016       0  265.49     .06       0   933.6     .12       0
  1022.5    .045       0  1126.4     .04       0 1133.77     .12       0
  1348.2     .06       0 1427.16     .12       0 1702.75     .06       0
 1713.27     .12       0 1789.75     .06       0
Bank Sta=1022.5,1126.4
XS Rating Curve= 0 ,0
Exp/Cntr=0.3,0.1

Type RM Length L Ch R = 1 ,145236.5,387.4,388.6,389.8
XS GIS Cut Line= 4
     2351686.511      333134.832      2351945.81      333261.494
     2353099.158      333123.918     2353647.198      332969.828
#Sta/Elev= 30
       0  510.18    63.2  508.83   106.7  510.87  271.18504.7867  307.42504.3086
  391.37503.0132  442.79501.7791   520.1  500.47     560  494.74   603.9  493.66
   991.1  490.74  1120.1492.5902  1202.6  493.27  1210.6  491.18  1222.6  482.62
  1226.6   482.4 1316.79482.7228 1329.27486.7369  1338.3  492.12  1362.3  513.69
  1394.2   538.5  1446.1  566.13    1470  570.36 1568.37572.9943 1672.21572.1413
 1791.03 571.318 1824.62571.1536  1931.8  567.24  1975.6  557.95  2019.4  545.59
#Mann= 13 ,-1 , 0
       0     .06       0  271.18     .12       0  307.42     .06       0
  391.37     .08       0  442.79     .06       0  1120.1     .12       0
  1222.6    .045       0 1316.79     .04       0 1329.27     .12       0
 1568.37     .06       0 1672.21     .12       0 1791.03     .06       0
 1824.62     .12       0
Bank Sta=1222.6,1316.79
XS Rating Curve= 0 ,0
Exp/Cntr=0.3,0.1

Type RM Length L Ch R = 1 ,144847.9,1480.4,1481.1,1481.7
XS GIS Cut Line= 3
     2351455.608       333358.79      2351820.81      333612.189
     2353907.615      333435.105
#Sta/Elev= 30
       0  511.22   214.3  505.49   472.5  504.57   700.3  496.59   832.2   494.9
   940.1  489.38  1351.8  492.42  1659.5  487.75 1671.83484.0082  1691.5   482.4
  1735.5   483.7  1767.4  512.38  1811.4  544.94  1835.4  557.93  1863.4   565.9
  1943.3  570.46  2051.2  565.61  2111.2  550.03  2195.1  509.79  2215.1  504.97
    2247  508.44    2299  529.83    2323  531.39    2343  542.72  2402.9  557.89
  2458.9   566.3  2474.9   567.3  2482.8  565.02  2502.8  569.07  2538.8  569.73
#Mann= 3 , 0 , 0
       0      .1       0 1671.83    .045       0  1735.5      .1       0
Bank Sta=1671.83,1735.5
XS Rating Curve= 0 ,0
Exp/Cntr=0.3,0.1

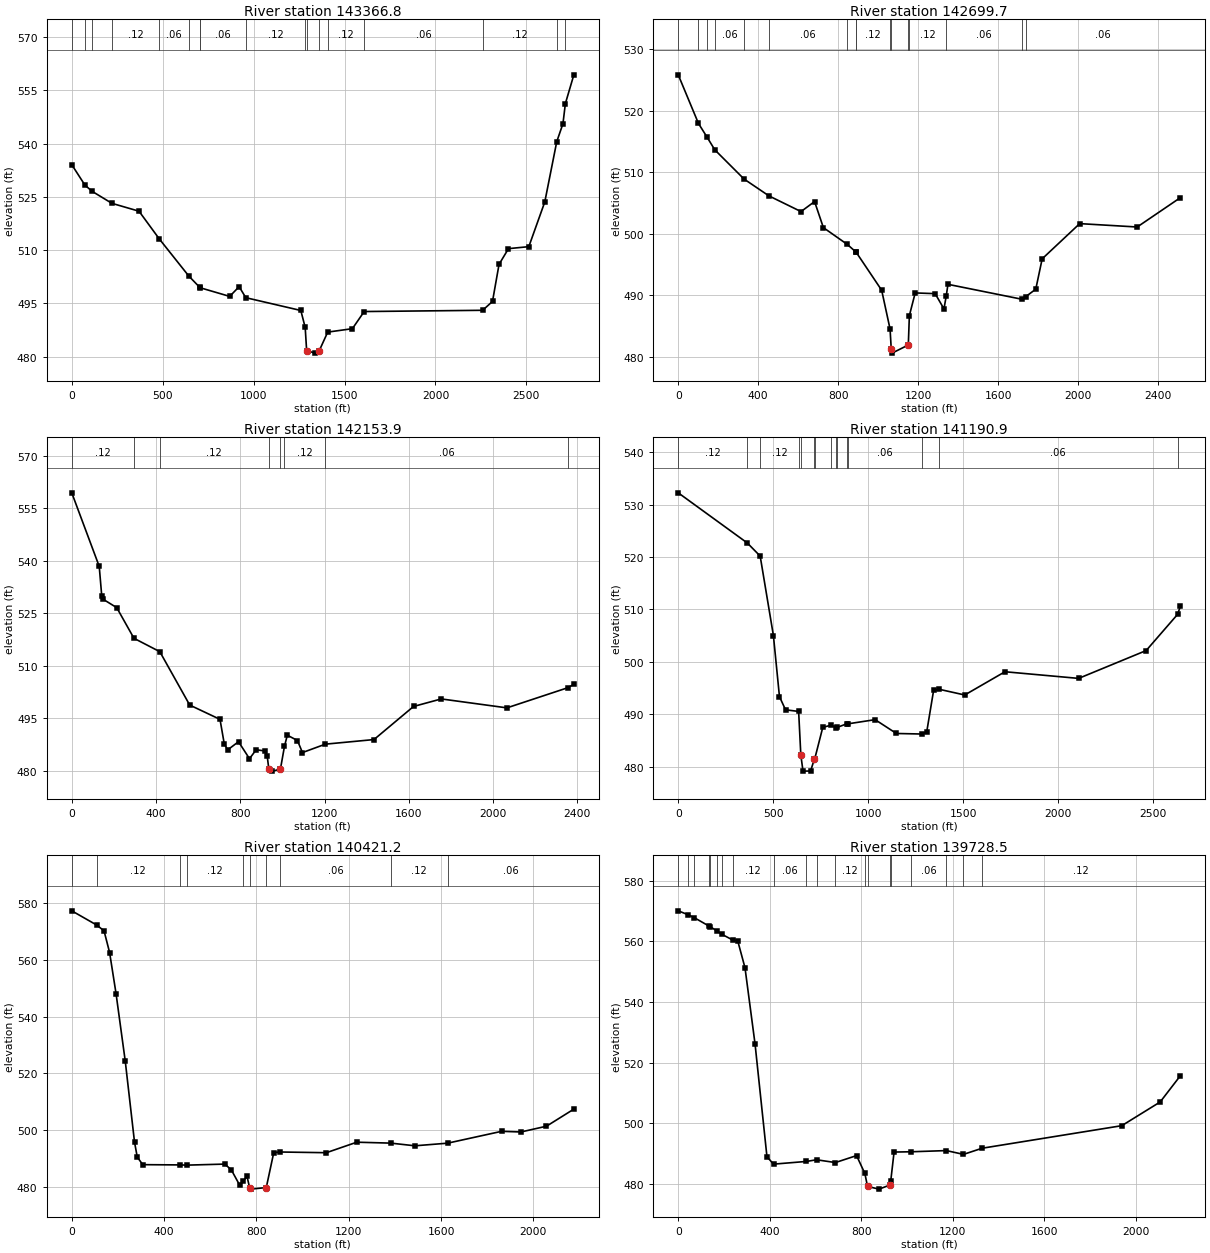
Type RM Length L Ch R = 1 ,143366.8,668,667.1,666.2
XS GIS Cut Line= 4
     2351209.081      334810.179     2351595.115      334466.355
     2353501.365      334313.578     2353806.921      334185.105
#Sta/Elev= 30
       0  534.08   72.16528.3406  112.12 526.567  220.69  523.19   369.8  520.97
  481.27513.1579  643.26 502.714  703.05499.5412  707.75499.3708   868.3  496.96
   920.2   499.7  957.08496.5941  1259.5  492.99 1283.58488.1992  1291.5  481.67
  1337.7  480.97 1360.79481.6461 1407.35486.8952    1543  487.86 1607.87492.6909
 2259.27493.0432  2313.5  495.54  2349.5     506  2401.4  510.42  2513.2  510.98
    2601  523.58 2666.76540.5627  2700.9  545.64 2714.17 551.295  2760.8  559.41
#Mann= 17 ,-1 , 0
       0     .12       0   72.16     .08       0  112.12     .06       0
  220.69     .12       0  481.27     .06       0  643.26    .016       0
  703.05     .12       0  707.75     .06       0  957.08     .12       0
 1283.58     .04       0  1291.5    .045       0 1360.79     .04       0
 1407.35     .12       0 1607.87     .06       0 2259.27     .12       0
 2666.76    .016       0 2714.17     .12       0
Bank Sta=1291.5,1360.79
XS Rating Curve= 0 ,0
Exp/Cntr=0.3,0.1

Type RM Length L Ch R = 1 ,142699.7,553.3,545.8,538.3
XS GIS Cut Line= 3
     2351619.421      335417.744     2351862.476      335122.605
      2353977.06       334879.55
#Sta/Elev= 30
       0  525.86  101.24517.9394  143.95515.7234  182.72513.6568  329.04508.8989
  453.52506.1568     614   503.6   681.8  505.23   725.8  500.99   845.9 498.244
  887.67 497.048  889.37497.0034  1017.3   490.8 1059.33484.4767  1065.2  481.24
  1069.2  480.56 1150.59481.8865 1155.85486.6669    1185  490.36  1284.9  490.24
  1328.8  487.76 1340.01489.8192  1348.8  491.76  1721.2489.3144 1737.27489.7415
    1788  490.97    1820  495.91  2007.7  501.64  2295.2  501.09  2510.8  505.86
#Mann= 16 ,-1 , 0
       0     .06       0  101.24    .016       0  143.95     .12       0
  182.72     .06       0  329.04     .12       0  453.52     .06       0
   845.9     .12       0  887.67     .06       0  889.37     .12       0
 1059.33     .04       0  1065.2    .045       0 1150.59     .04       0
 1155.85     .12       0 1340.01     .06       0  1721.2     .04       0
 1737.27     .06       0
Bank Sta=1065.2,1150.59
XS Rating Curve= 0 ,0
Exp/Cntr=0.3,0.1

Type RM Length L Ch R = 1 ,142153.9,987.7,963,938.3
XS GIS Cut Line= 4
     2352011.782      335990.661     2352174.976      335733.717
     2353845.115      335198.994     2354015.254      334921.217
#Sta/Elev= 30
       0  559.39   130.4  538.38   142.3  529.94   146.3   529.1   213.5  526.61
   295.2517.8638  418.05514.0396     560   498.8   703.8  494.72   723.8   487.8
   739.8  485.99   791.7  488.34   843.7  483.49   875.6  486.04   915.6  485.71
   927.6  484.39   935.5  480.58   951.5  479.94   990.5480.4475 1009.88487.0203
  1023.4   490.2  1071.4  488.68  1095.3  485.24 1203.92487.6383  1434.9  488.95
  1622.6   498.4  1754.4  500.55    2066     498 2356.05503.7704  2383.8  504.72
#Mann= 8 ,-1 , 0
       0     .12       0   295.2     .06       0  418.05     .12       0
   935.5    .045       0   990.5     .04       0 1009.88     .12       0
 1203.92     .06       0 2356.05     .12       0
#XS Ineff= 2 , 0
       0                    1786       0
Permanent Ineff=
       F       F
Bank Sta=935.5,990.5
XS Rating Curve= 0 ,0
Exp/Cntr=0.3,0.1

Type RM Length L Ch R = 1 ,141190.9,780.2,769.7,758.7
XS GIS Cut Line= 4
     2352473.587      336580.939     2352855.532      336653.855
      2353977.06      335073.994     2354261.782      334938.578
#Sta/Elev= 30
       0  532.27  363.35522.6946  431.09520.1895   500.7  505.02   532.6  493.34
   564.6  490.83  633.48490.5236     645  482.17   656.5  479.12   696.4  479.14
   716.4  481.44   717.7481.3945   760.4  487.47  803.58487.8976  830.46487.4384
  837.84  487.49  886.23488.1543  890.65488.1406    1036  488.95  1147.8  486.31
 1284.28 486.204  1307.6  486.66  1343.6  494.54    1371 494.765  1507.4  493.66
  1719.1   498.1  2106.6  496.83    2462  502.15 2627.43509.0664  2641.6  510.59
#Mann= 15 ,-1 , 0
       0     .12       0  363.35    .016       0  431.09     .12       0
  633.48     .04       0     645    .045       0   716.4     .04       0
   717.7     .12       0  803.58     .06       0  830.46     .12       0
  837.84     .06       0  886.23     .12       0  890.65     .06       0
 1284.28     .12       0    1371     .06       0 2627.43     .12       0
#XS Ineff= 2 , 0
       0                    1719       0
Permanent Ineff=
       F       F
Bank Sta=645,716.4
XS Rating Curve= 0 ,0
Exp/Cntr=0.3,0.1

Type RM Length L Ch R = 1 ,140421.2,689.3,692.7,696.4
XS GIS Cut Line= 3
     2353487.476      337046.217      2354133.31      335205.939
     2354310.393       335067.05
#Sta/Elev= 30
       0  577.39   109.3 572.309   139.9   570.3   163.9  562.67   191.8  548.19
   231.8  524.27   271.8  495.77   283.8  490.42   307.7  487.76  467.62487.6702
  498.67487.5933   663.4  487.96   691.4  485.91   727.4  480.54  743.83482.0899
   759.3  483.61   771.3  479.39   775.3  479.12  842.74479.6746   875.2  492.04
   902.5492.2304    1103  491.98  1234.9  495.69  1382.3 495.365  1486.7  494.42
  1628.3495.3441  1862.4  499.53  1946.3   499.3  2056.9  501.34  2175.4  507.37
#Mann= 10 ,-1 , 0
       0     .06       0   109.3     .12       0  467.62    .016       0
  498.67     .12       0  743.83     .04       0   771.3    .045       0
  842.74     .12       0   902.5     .06       0  1382.3     .12       0
  1628.3     .06       0
#XS Ineff= 2 , 0
       0                    1500       0
Permanent Ineff=
       F       F
Bank Sta=771.3,842.74
XS Rating Curve= 0 ,0
Exp/Cntr=0.3,0.1

Type RM Length L Ch R = 1 ,139728.5,761.5,767.4,773.2
XS GIS Cut Line= 2
     2354015.254      337369.133     2354935.393      335376.078
#Sta/Elev= 30
       0  570.02   41.72 568.777   70.85567.7318  136.67564.9016  138.75564.8444
  169.15563.3684  190.04562.3116  239.97560.3342   259.9  560.19   291.9  551.25
   335.9   526.1   387.9  488.97  416.66486.5332  560.75487.4276  604.71487.9755
  687.23487.0586   779.7  489.35  815.87483.4736   827.7  479.19   877.8   478.3
   927.7  479.71  929.04480.9294   943.7  490.52 1019.13490.6124 1172.24491.0016
 1247.19489.7546 1328.86 491.779  1939.3  499.21  2107.2  507.03  2195.2  515.65
#Mann= 20 ,-1 , 0
       0     .06       0   41.72     .12       0   70.85     .06       0
  136.67     .12       0  138.75     .06       0  169.15     .12       0
  190.04     .06       0  239.97     .12       0  416.66     .06       0
  560.75    .016       0  604.71     .06       0  687.23     .12       0
  815.87     .04       0   827.7    .045       0   927.7     .04       0
  929.04     .12       0 1019.13     .06       0 1172.24     .12       0
 1247.19     .06       0 1328.86     .12       0
Bank Sta=827.7,927.7
XS Rating Curve= 0 ,0
Exp/Cntr=0.3,0.1

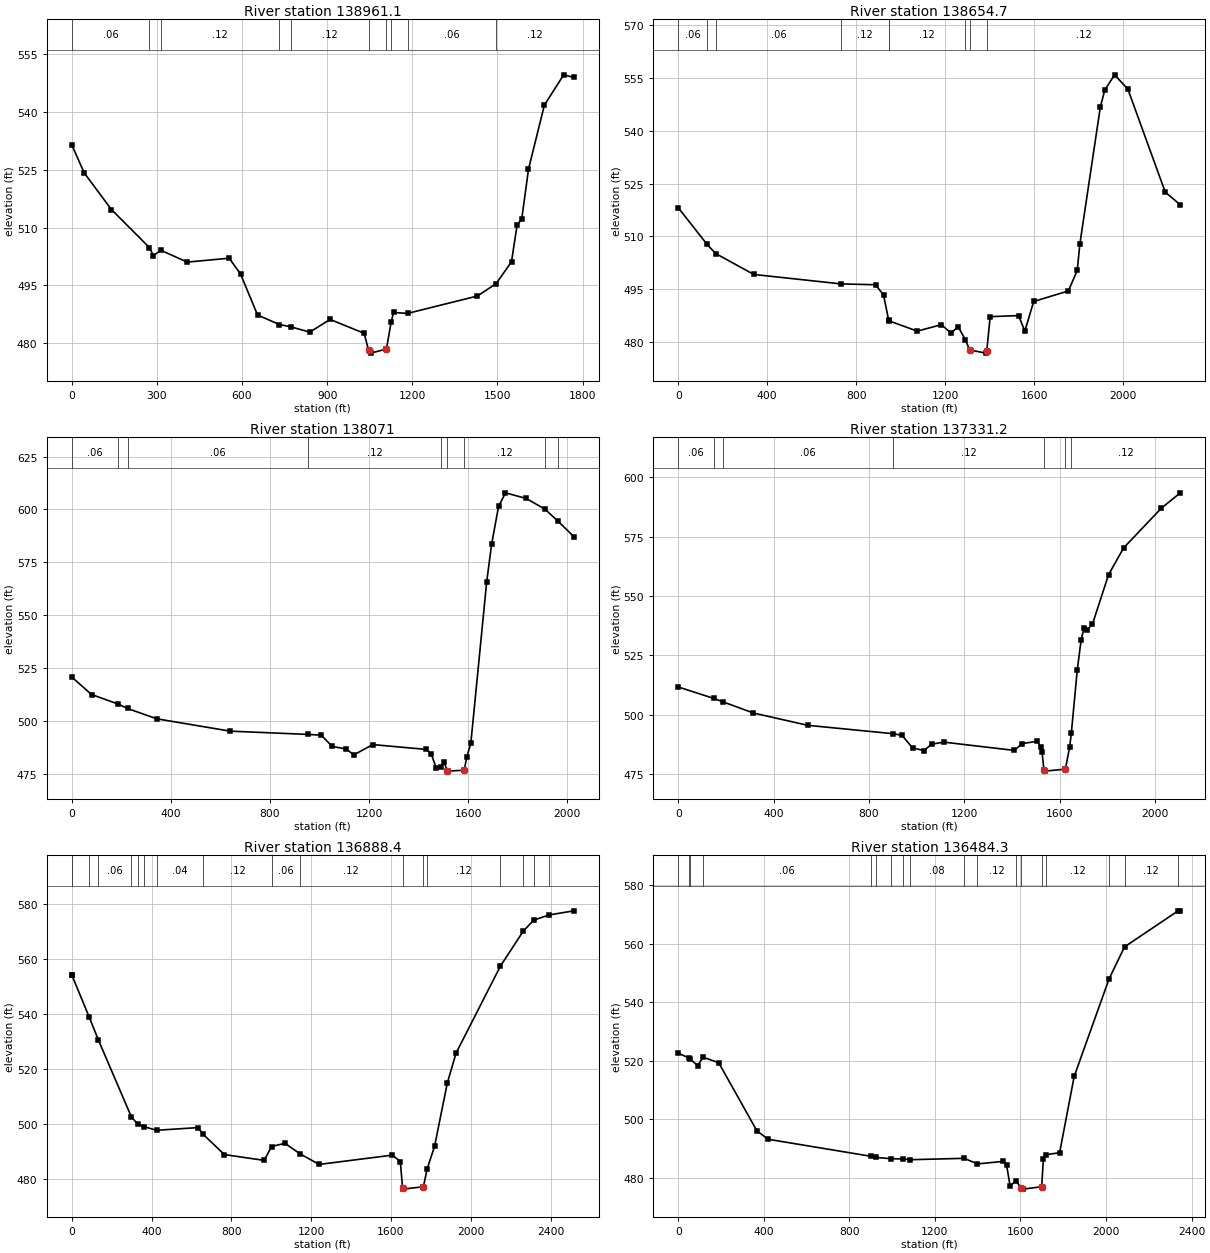
Type RM Length L Ch R = 1 ,138961.1,297.5,306.4,315.3
XS GIS Cut Line= 3
      2354227.06      337365.661     2354761.782      337369.133
      2355445.81      336341.355
#Sta/Elev= 30
       0  531.47    43.9  524.18   139.7  514.68  273.66504.8067   287.3  502.74
  314.73504.0604     407  501.03   554.7  502.04   594.7  497.95   654.6   487.3
  731.23484.8274  771.91484.2289   838.4  482.85   910.3  486.14  1030.2  482.55
  1046.2  478.11  1054.1   477.4  1108.9 478.474 1125.24485.3555    1134  487.95
 1183.22487.7122  1429.7  492.23 1495.77495.4602  1549.6  501.12  1569.6  510.78
  1585.5  512.11  1609.5  525.14  1665.4  541.76  1733.4  549.64  1769.3  548.97
#Mann= 10 ,-1 , 0
       0     .06       0  273.66    .016       0  314.73     .12       0
  731.23    .016       0  771.91     .12       0  1046.2    .045       0
  1108.9     .04       0 1125.24     .12       0 1183.22     .06       0
 1495.77     .12       0
Bank Sta=1046.2,1108.9
XS Rating Curve= 0 ,0
Exp/Cntr=0.3,0.1

Type RM Length L Ch R = 1 ,138654.7,566.2,583.7,601.2
XS GIS Cut Line= 3
     2354234.004      337671.217     2354563.865      337792.744
     2355960.485      336497.465
#Sta/Elev= 30
       0  518.14  129.45507.7193  168.04505.1124   339.6  499.16  731.48496.4785
   886.6  496.23   922.6  493.34   945.9486.0739  947.31485.9684  1074.3  483.05
  1182.1  484.88  1226.1  482.53    1258   484.3  1289.6 480.663  1309.9   477.7
  1381.8   476.8 1386.59477.4288  1401.8  487.16  1529.6  487.47  1557.5  483.05
  1597.4  491.48  1753.2  494.47  1793.1  500.33  1805.1  507.92    1897   546.8
  1916.9  551.56  1960.8   555.9  2020.7  551.83  2188.5  522.57  2256.3  518.95
#Mann= 9 ,-1 , 0
       0     .06       0  129.45    .016       0  168.04     .06       0
  731.48     .12       0   945.9     .07       0  947.31     .12       0
  1289.6     .04       0  1309.9    .045       0 1386.59     .12       0
Bank Sta=1309.9,1386.59
XS Rating Curve= 0 ,0
Exp/Cntr=0.3,0.1

Type RM Length L Ch R = 1 ,138071  ,717.7,739.8,761.9
XS GIS Cut Line= 3
     2354136.782      337764.967     2354598.587      337893.439
     2356084.698      337462.883
#Sta/Elev= 30
       0  520.68    79.9  512.42  186.16507.9558  224.97 505.817   343.5  500.92
   639.3  495.09  952.82493.5458  1007.1  493.18  1051.1  487.86    1107  486.66
    1139  483.89    1215  488.73  1430.9  486.44  1450.9  484.42  1470.8  477.68
 1490.65478.1175  1502.8  480.61  1514.8  476.43  1518.8  476.17 1583.96476.6173
  1594.8  483.05  1610.8  489.41  1674.7  565.64  1694.7  583.54  1722.7  601.42
  1750.7  607.87  1834.7  605.19 1909.49600.1671 1962.68594.4538  2026.6  587.14
#Mann= 9 ,-1 , 0
       0     .06       0  186.16    .016       0  224.97     .06       0
  952.82     .12       0 1490.65     .04       0  1514.8    .045       0
 1583.96     .12       0 1909.49     .06       0 1962.68     .12       0
Bank Sta=1514.8,1583.96
XS Rating Curve= 0 ,0
Exp/Cntr=0.3,0.1

Type RM Length L Ch R = 1 ,137331.2,442.9,442.8,442.6
XS GIS Cut Line= 3
     2354143.726      337844.828     2355779.143      338358.717
     2356095.115      338126.078
#Sta/Elev= 30
       0  511.63  149.52506.7809  189.04505.3042   315.7  500.64   543.4  495.47
  900.78491.9425     939  491.26     983  485.96    1031  484.84  1062.9  487.52
  1114.9  488.38  1410.6  484.89  1442.5  487.79  1506.5   488.7  1522.4  486.15
  1526.4  484.31  1534.4   476.7  1538.4  476.17 1624.36477.0042  1642.3  486.34
 1649.41492.2311  1674.3  518.83  1690.3  531.29  1702.3  536.35  1714.2  535.46
    1738   538.1  1805.4  558.89  1868.8  570.22  2027.4  586.97  2106.6  593.41
#Mann= 7 ,-1 , 0
       0     .06       0  149.52    .016       0  189.04     .06       0
  900.78     .12       0  1534.4    .045       0 1624.36     .04       0
 1649.41     .12       0
Bank Sta=1534.4,1624.36
XS Rating Curve= 0 ,0
Exp/Cntr=0.3,0.1

Type RM Length L Ch R = 1 ,136888.4,406.8,404.2,401.5
XS GIS Cut Line= 4
     2353879.837      338073.994     2354120.734      338299.711
     2355588.171       338754.55     2356150.671      338428.161
#Sta/Elev= 30
       0  554.07    1.26554.0605   86.37539.0316  133.28  530.55  298.49502.5503
  329.72499.9461  359.94498.9678  425.89497.6236   633.4  498.59  659.22496.0888
   765.1  488.75   964.6  486.65 1001.55491.6901  1068.4  492.88  1144.9489.0085
  1239.9  485.17    1607  488.56    1647  486.22 1658.02476.6804  1658.9  476.17
  1762.7  477.03 1781.38483.5218  1818.6  491.77  1882.4  514.81  1926.3  525.72
 2148.76557.4373 2263.44570.1934 2315.84574.2043 2393.12576.0805  2516.8  577.58
#Mann= 18 ,-1 , 0
       0     .06       0    1.26     .12       0   86.37    .016       0
  133.28     .06       0  298.49     .08       0  329.72    .016       0
  359.94     .12       0  425.89     .04       0  659.22     .12       0
 1001.55     .06       0  1144.9     .12       0 1658.02    .045       0
  1762.7     .04       0 1781.38     .12       0 2148.76     .06       0
 2263.44     .12       0 2315.84     .06       0 2393.12     .12       0
#XS Ineff= 2 , 0
       0    1060                       0
Permanent Ineff=
       F       F
Bank Sta=1658.02,1762.7
XS Rating Curve= 0 ,0
Exp/Cntr=0.3,0.1

Type RM Length L Ch R = 1 ,136484.3,358.8,360.3,361.8
XS GIS Cut Line= 4
     2353782.615      338851.772     2354033.428      338799.574
     2355612.476      339157.328     2355924.976      339511.494
#Sta/Elev= 30
       0  522.64   49.32521.0495      54 520.774    90.6  518.43  116.32521.2689
   189.2  519.39   368.1  496.08   420.1  493.22  901.15487.4003   924.7 487.001
  996.75486.5614 1053.06 486.487 1083.44486.2259 1337.06486.7062 1398.78484.7862
  1519.5  485.66  1535.4  484.38  1551.4  477.37 1580.06478.8616  1603.4  476.65
  1611.4  476.17  1699.4  476.98  1707.4  486.63 1718.36487.8976  1783.3  488.64
  1851.3  514.69  2014.7548.1128 2086.82559.0098 2337.51571.3297  2347.6   571.3
#Mann= 18 ,-1 , 0
       0     .06       0   49.32     .04       0      54    .016       0
  116.32     .06       0  901.15     .08       0   924.7     .06       0
  996.75     .08       0 1053.06     .06       0 1083.44     .08       0
 1337.06     .06       0 1398.78     .12       0 1580.06     .04       0
  1603.4    .045       0  1699.4     .04       0 1718.36     .12       0
  2014.7     .06       0 2086.82     .12       0 2337.51     .06       0
Bank Sta=1603.4,1699.4
XS Rating Curve= 0 ,0
Exp/Cntr=0.3,0.1

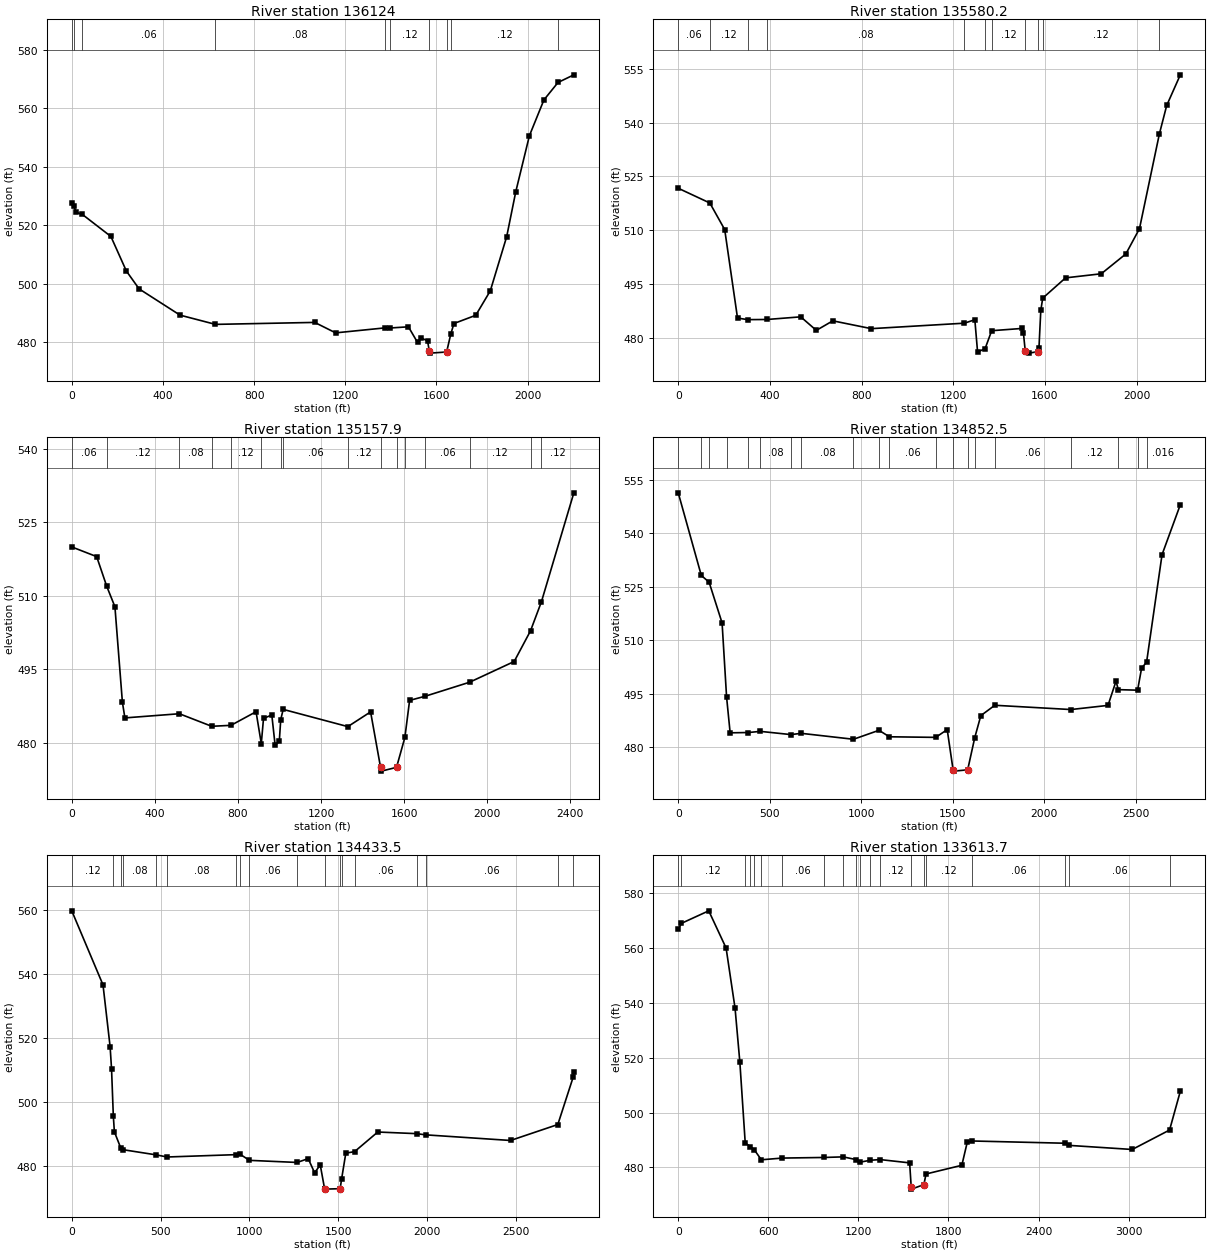
Type RM Length L Ch R = 1 ,136124  ,541.7,543.7,545.9
XS GIS Cut Line= 3
     2353768.726      339008.022     2355650.671      339542.744
     2355897.198      339553.161
#Sta/Elev= 30
       0  527.59    8.21526.5374      20  524.38   46.68523.6561   171.7  516.12
   239.6  504.28   295.5  498.17   475.1  489.18  630.63486.0148  1066.1  486.69
  1157.9  483.11 1373.37484.8079 1397.14484.7803  1477.3  485.18  1517.2  479.84
  1533.2  481.36  1561.2  480.39  1569.1  476.78  1573.1  476.17    1645  476.56
  1663.2  482.72    1677  486.31  1772.8  489.13  1836.6  497.51  1908.5  516.06
  1948.4  531.47  2008.2  550.63  2071.8  562.88 2133.69568.8608  2203.2  571.48
#Mann= 10 ,-1 , 0
       0     .06       0    8.21    .016       0   46.68     .06       0
  630.63     .08       0 1373.37     .06       0 1397.14     .12       0
  1569.1    .045       0    1645     .04       0  1663.2     .12       0
 2133.69     .06       0
Bank Sta=1569.1,1645
XS Rating Curve= 0 ,0
Exp/Cntr=0.3,0.1

Type RM Length L Ch R = 1 ,135580.2,418.5,422.4,426.2
XS GIS Cut Line= 4
     2353768.726      339341.355      2353883.31      339532.328
     2355449.282      340056.633     2355765.254      340032.328
#Sta/Elev= 30
       0   521.7  137.91517.5893   202.8  510.18   258.7  485.53  303.47485.0907
  386.73485.1326   534.6  485.87   602.6   482.1   674.6  484.76   842.5  482.58
 1249.02484.1037  1294.3  485.07  1306.3  476.07 1339.15477.0151 1367.82482.0072
  1498.3  482.63  1506.2  481.45  1514.2  476.42  1530.2  475.76 1571.07476.1801
  1574.2  477.26  1582.2  487.69  1590.6 491.079  1690.2  496.73  1846.1  497.87
  1953.4   503.4  2012.8  510.44  2099.7  536.85  2131.6  544.76    2191   553.3
#Mann= 11 ,-1 , 0
       0     .06       0  137.91     .12       0  303.47     .06       0
  386.73     .08       0 1249.02     .12       0 1339.15     .04       0
 1367.82     .12       0  1514.2    .045       0 1571.07     .04       0
  1590.6     .12       0  2099.7     .06       0
Bank Sta=1514.2,1571.07
XS Rating Curve= 0 ,0
Exp/Cntr=0.3,0.1

Type RM Length L Ch R = 1 ,135157.9,309.9,305.3,300.8
XS GIS Cut Line= 3
     2353546.504      339695.522     2355487.476      340573.994
     2355744.421      340445.522
#Sta/Elev= 30
       0  519.99   119.9  518.01  168.58511.9215   207.8  507.76   243.8  488.25
   255.8  485.04  518.07485.8909  673.97 483.325  766.64483.5207   887.4   486.3
  912.66479.7997   923.4  484.94   963.3  485.64   979.3  479.43   999.3  480.22
 1006.31484.7051 1018.12486.7806 1329.48483.2603    1439  486.27    1487  474.92
    1491  474.16 1563.92474.9323 1604.07481.0389  1626.9  488.62 1701.69 489.465
  1915.7492.3325  2130.5  496.57 2209.11502.8372  2261.9508.8114  2417.8  531.05
#Mann= 16 ,-1 , 0
       0     .06       0  168.58     .12       0  518.07     .08       0
  673.97     .06       0  766.64     .12       0  912.66     .08       0
 1006.31     .12       0 1018.12     .06       0 1329.48     .12       0
    1487    .045       0 1563.92     .04       0 1604.07     .12       0
 1701.69     .06       0  1915.7     .12       0 2209.11     .06       0
  2261.9     .12       0
#XS Ineff= 2 , 0
       0                    1700       0
Permanent Ineff=
       F       F
Bank Sta=1487,1563.92
XS Rating Curve= 0 ,0
Exp/Cntr=0.3,0.1

Type RM Length L Ch R = 1 ,134852.5,425.8,419,412.3
XS GIS Cut Line= 3
     2353341.643      340136.494     2355701.832      340885.208
     2355944.888      340774.097
#Sta/Elev= 30
       0  551.39  126.09528.2152  168.55526.3465   239.6  514.91  264.24494.0952
   283.6   484.1  382.93484.1835  448.75484.5051  615.46483.6041  672.27 483.956
  957.58482.2934 1096.86484.8056 1153.67482.9896 1406.94482.8242  1469.7     485
  1501.6   473.8  1505.6  473.36  1581.5  473.72  1620.3482.7668  1653.4  488.92
  1729.8491.8231 2145.45490.6272  2348.3  491.79  2392.2   498.6 2404.39496.2058
 2509.92496.0544  2531.9  502.25 2559.12503.9012  2643.6  534.06  2743.4  548.05
#Mann= 20 ,-1 , 0
       0     .12       0  126.09    .016       0  168.55     .12       0
  264.24     .08       0  382.93     .12       0  448.75     .08       0
  615.46     .06       0  672.27     .08       0  957.58     .06       0
 1096.86     .08       0 1153.67     .06       0 1406.94     .12       0
  1501.6    .045       0  1581.5     .04       0  1620.3     .12       0
  1729.8     .06       0 2145.45     .12       0 2404.39     .04       0
 2509.92     .12       0 2559.12    .016       0
Bank Sta=1501.6,1581.5
XS Rating Curve= 0 ,0
Exp/Cntr=0.3,0.1

Type RM Length L Ch R = 1 ,134433.5,834,819.8,805.5
XS GIS Cut Line= 3
     2353139.332      340690.764     2355829.437      341174.271
     2355909.298      341127.396
#Sta/Elev= 30
       0  559.82   175.8   536.7   215.8  517.41   223.8  510.54  233.89495.7602
   239.8  490.83  276.07485.7175  288.15485.2444  474.21483.6341  537.01482.9628
  924.11483.6942  946.66483.8349 1000.09481.9137  1268.5 481.259  1330.6  482.46
  1366.6  478.05  1398.6  480.47  1422.6  473.12  1426.5  472.93  1510.5  473.07
 1518.79476.1353  1542.4  484.17 1591.59484.6303  1722.2  490.76  1940.7 490.253
 1991.08489.8803  2469.5  488.12 2735.59493.1006 2823.06508.0791  2825.8  509.55
#Mann= 18 ,-1 , 0
       0     .12       0  233.89    .016       0  276.07     .06       0
  288.15     .08       0  474.21     .06       0  537.01     .08       0
  924.11     .06       0  946.66     .08       0 1000.09     .06       0
  1268.5     .12       0  1422.6    .045       0  1510.5     .04       0
 1518.79     .12       0 1591.59     .06       0  1940.7     .12       0
 1991.08     .06       0 2735.59     .12       0 2823.06    .016       0
#XS Ineff= 2 , 0
       0                    1786       0
Permanent Ineff=
       F       F
Bank Sta=1422.6,1510.5
XS Rating Curve= 0 ,0
Exp/Cntr=0.3,0.1

Type RM Length L Ch R = 1 ,133613.7,685.8,670.7,655.7
XS GIS Cut Line= 4
     2352684.775      342032.401     2353115.947      341902.668
     2355689.907      341256.633     2355915.601      341174.168
#Sta/Elev= 30
       0   566.8   21.21568.9736   203.2  573.53   318.8  559.97   378.5  538.04
   410.4  518.42  446.26488.9091  480.68487.6413  505.74486.5201  553.46482.8059
  692.76483.4268  971.21483.6482 1098.68483.8645 1184.01 482.881 1209.56481.9271
 1280.48482.6356 1344.43482.8795  1541.4  481.68 1551.73472.9909  1553.4  472.11
 1636.28473.7538 1650.55477.6265  1889.1   480.8    1925  489.17  1958.3 489.654
 2573.47488.8388 2603.78488.0504  3024.1  486.56 3272.83493.6457  3344.4  507.77
#Mann= 20 ,-1 , 0
       0    .016       0   21.21     .12       0  446.26    .016       0
  480.68     .12       0  505.74     .06       0  553.46     .12       0
  692.76     .06       0  971.21     .12       0 1098.68     .06       0
 1184.01     .12       0 1209.56     .04       0 1280.48     .06       0
 1344.43     .12       0 1551.73    .045       0 1636.28     .04       0
 1650.55     .12       0  1958.3     .06       0 2573.47     .12       0
 2603.78     .06       0 3272.83     .12       0
#XS Ineff= 2 , 0
       0                    2035       0
Permanent Ineff=
       F       F
Bank Sta=1551.73,1636.28
XS Rating Curve= 0 ,0
Exp/Cntr=0.3,0.1