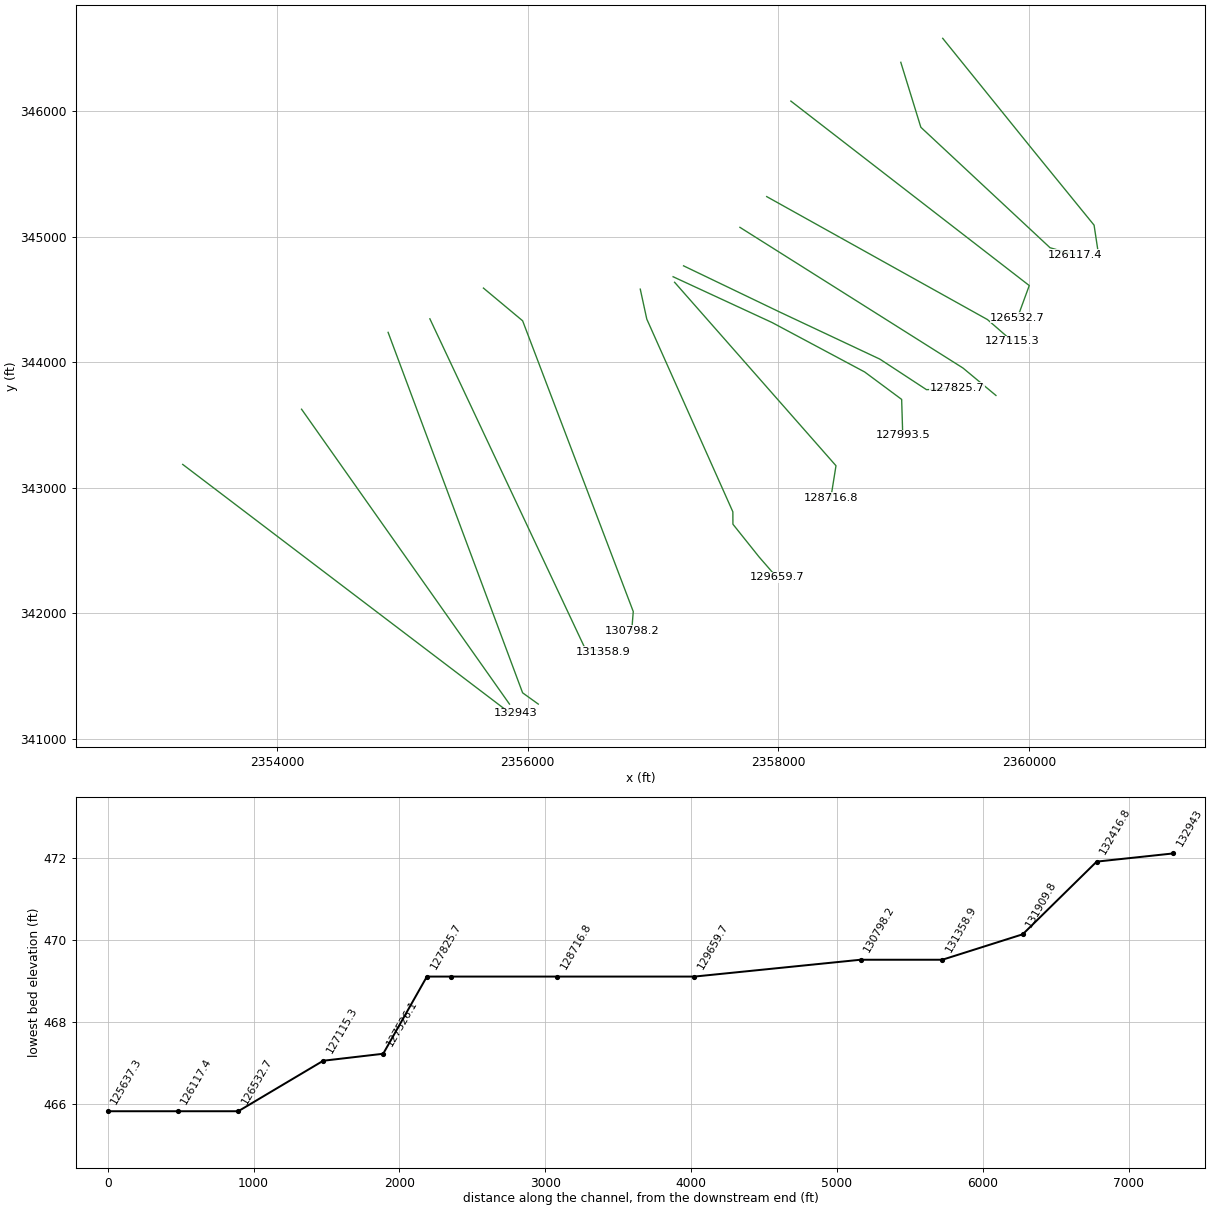
HEC-RAS study BACKCREEK.prj: BACKCREEK

--- BACKCREEK.g01 (geometry) --- (continued)

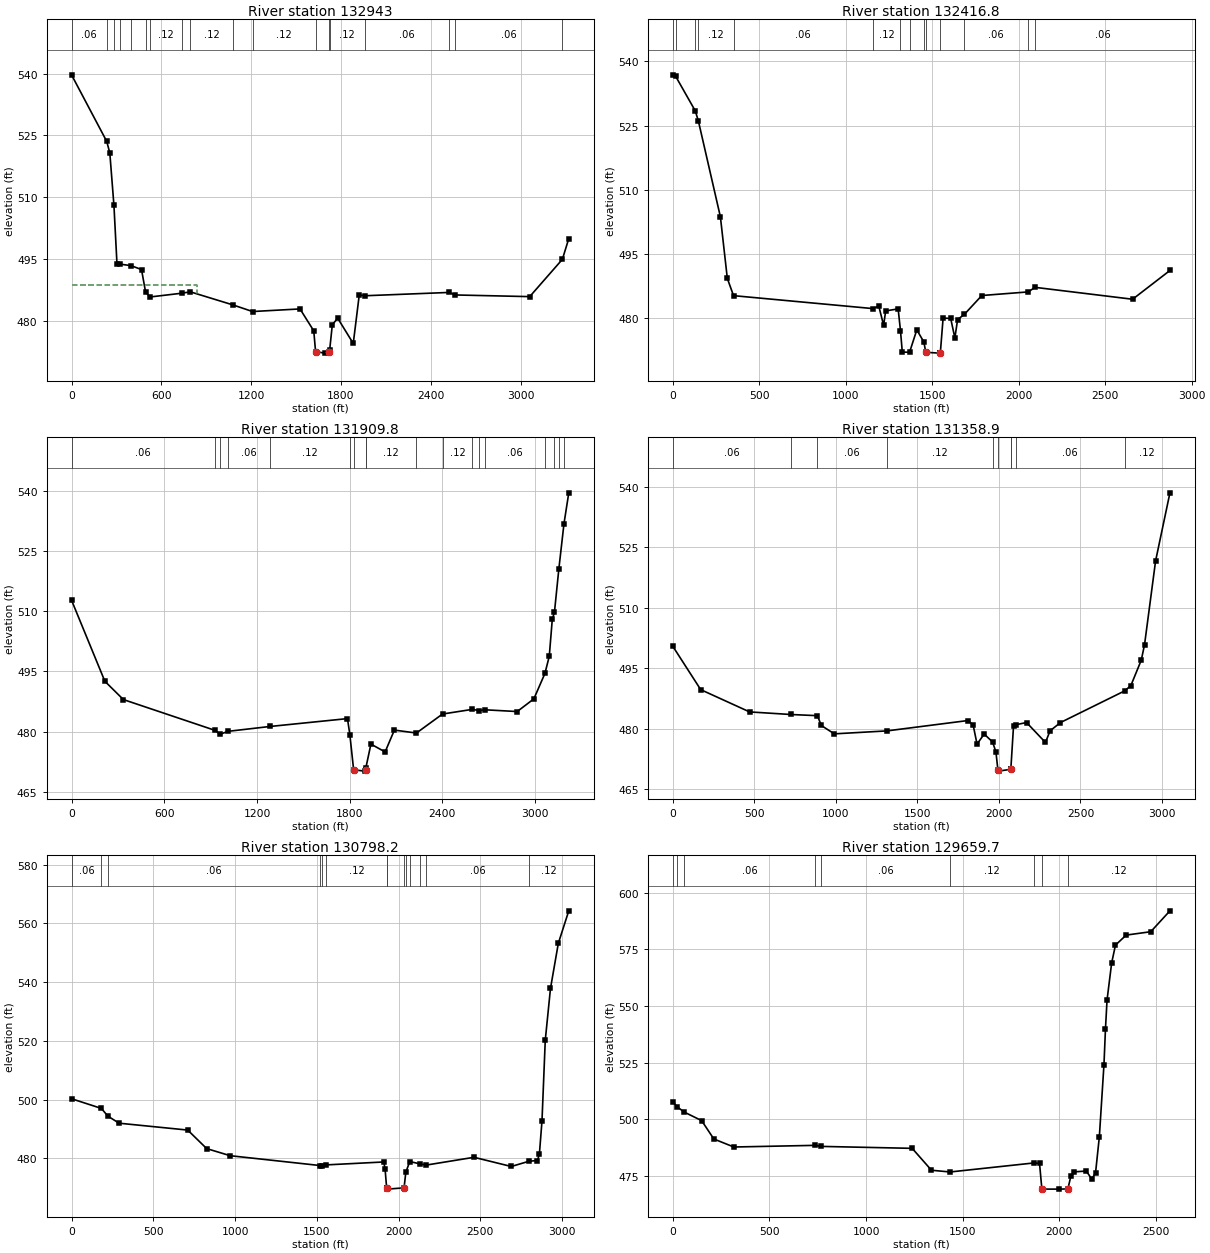
Type RM Length L Ch R = 1 ,132943  ,538,526.2,514.3
XS GIS Cut Line= 3
     2353249.011      343186.915     2355846.798      341215.937
     2355906.921       341204.55
#Sta/Elev= 30
       0  539.74  234.98523.5782   255.8  520.75  283.33507.9928   303.7  493.76
  325.13493.7345  397.37493.3664   467.6  492.42  494.77486.9342  524.81485.7565
  736.21486.6689  793.28487.0062  1076.8 483.844 1209.41482.2184  1526.5  482.85
  1618.4  477.52  1630.4  472.49  1690.1  472.11 1723.13472.4645 1724.78472.9306
  1742.3     479  1778.3   480.6  1882.2  474.46  1922.2  486.23 1958.14  486.05
 2521.86486.8565 2562.85486.2471  3061.1  485.84 3279.39494.9064  3322.1  499.95
#Mann= 18 ,-1 , 0
       0     .06       0  234.98     .12       0  283.33    .016       0
  325.13     .06       0  397.37     .12       0  494.77     .06       0
  524.81     .12       0  736.21     .06       0  793.28     .12       0
  1076.8     .06       0 1209.41     .12       0  1630.4    .045       0
 1723.13     .04       0 1724.78     .12       0 1958.14     .06       0
 2521.86     .12       0 2562.85     .06       0 3279.39     .12       0
#XS Ineff= 2 , 0
       0   839.2  488.65    2315       0
Permanent Ineff=
       F       F
Bank Sta=1630.4,1723.13
XS Rating Curve= 0 ,0
Exp/Cntr=0.3,0.1

Type RM Length L Ch R = 1 ,132416.8,515.5,507,498
XS GIS Cut Line= 2
     2354196.851      343626.425     2355854.837      341278.335
#Sta/Elev= 30
       0  536.83   17.41 536.473  130.47528.4244  148.46526.0773   275.8   503.7
   315.8  489.34  351.76485.3176  1156.5482.3023  1191.4  482.86  1219.3  478.42
  1231.3  481.76  1303.3  482.23 1316.78477.1463  1327.3  472.16 1369.27  472.11
  1411.2  477.34 1451.98474.4984  1463.2   472.1  1543.2  471.91  1547.2     472
  1563.2  480.09  1607.1     480  1631.1  475.45  1647.1  479.75 1685.63480.9344
    1787  485.35 2055.52486.1923 2094.35487.2569  2658.6  484.48  2874.4  491.19
#Mann= 14 ,-1 , 0
       0     .06       0   17.41     .12       0  130.47     .06       0
  148.46     .12       0  351.76     .06       0  1156.5     .12       0
 1316.78     .04       0 1369.27     .12       0 1451.98     .04       0
  1463.2    .045       0  1547.2     .12       0 1685.63     .06       0
 2055.52     .12       0 2094.35     .06       0
#XS Ineff= 2 , 0
       0                    2115       0
Permanent Ineff=
       F       F
Bank Sta=1463.2,1547.2
XS Rating Curve= 0 ,0
Exp/Cntr=0.3,0.1

Type RM Length L Ch R = 1 ,131909.8,548.9,551,553.4
XS GIS Cut Line= 3
     2354886.955      344238.404     2355959.511      341368.245
     2356084.645      341278.437
#Sta/Elev= 30
       0  512.71   215.7  492.52   335.6  487.96  928.02480.3017  962.52479.3289
 1013.08480.0516 1284.93481.2619  1785.7  483.22 1801.15479.2433  1825.6  470.47
  1897.5  470.14 1902.49470.4151 1904.73470.9471  1937.5  476.87  2029.4  474.92
  2089.3  480.36 2232.04479.6282 2401.04484.3621 2593.95485.5201  2637.4 485.224
 2674.19485.4175  2884.2  484.98  2992.1  488.14 3063.73494.4813  3091.7  498.74
  3111.4     508 3125.23509.7052 3153.54520.4297 3186.96531.7638    3218  539.45
#Mann= 18 ,-1 , 0
       0     .06       0  928.02     .12       0  962.52     .08       0
 1013.08     .06       0 1284.93     .12       0 1801.15     .04       0
  1825.6    .045       0 1902.49     .04       0 1904.73     .12       0
 2232.04     .06       0 2401.04     .12       0 2593.95    .016       0
  2637.4     .12       0 2674.19     .06       0 3063.73     .12       0
 3125.23    .016       0 3153.54     .12       0 3186.96     .06       0
#XS Ineff= 2 , 0
       0                    2560       0
Permanent Ineff=
       F       F
Bank Sta=1825.6,1902.49
XS Rating Curve= 0 ,0
Exp/Cntr=0.3,0.1

Type RM Length L Ch R = 1 ,131358.9,563.8,560.7,557.6
XS GIS Cut Line= 3
     2355220.062      344346.146     2356453.796      341729.724
     2356605.705      341695.001
#Sta/Elev= 30
       0  500.51   171.8  489.72   471.5   484.2  723.26  483.56  887.44483.2653
     911  480.84   990.9  478.76 1313.07 479.491  1809.9  482.06  1841.9  480.99
  1865.9  476.22  1909.8  478.71 1961.24476.7382  1981.8  474.26  1993.7  469.82
  1997.7  469.52 2072.31469.9704 2073.28 470.128  2089.6  480.71 2104.74481.0262
  2169.5  481.57  2285.4  476.62  2313.4   479.5  2377.3  481.56 2770.51489.4015
  2808.8  490.71  2872.7  497.03  2892.7  500.83  2960.6  521.65  3048.5  538.51
#Mann= 10 ,-1 , 0
       0     .06       0  723.26     .12       0  887.44     .06       0
 1313.07     .12       0 1961.24     .04       0  1993.7    .045       0
 2072.31     .04       0 2073.28     .12       0 2104.74     .06       0
 2770.51     .12       0
Bank Sta=1993.7,2072.31
XS Rating Curve= 0 ,0
Exp/Cntr=0.3,0.1

Type RM Length L Ch R = 1 ,130798.2,1151.4,1138.5,1125.1
XS GIS Cut Line= 4
     2355647.145      344590.937     2355959.645      344330.521
     2356841.989      342015.246      2356829.23      341859.932
#Sta/Elev= 30
       0   500.3  182.53497.0048  222.21494.3785   291.1  491.97   710.5  489.63
   826.4  483.32   970.3   480.9 1521.52477.5433 1534.05477.5531 1558.43477.7763
  1909.4  478.77  1917.4  476.23 1926.56469.9815 1927.06469.9002  1929.4  469.52
  2033.3  469.95 2043.76475.2269 2068.01478.9109 2131.72478.1086 2168.51477.7074
  2460.9  480.36  2688.7  477.23 2797.79479.0262  2848.5  479.26  2860.5  481.39
  2876.5  492.74  2896.5   520.2  2928.4  537.85  2976.4  553.24  3040.3   564.3
#Mann= 14 ,-1 , 0
       0     .06       0  182.53     .08       0  222.21     .06       0
 1521.52     .12       0 1534.05     .06       0 1558.43     .12       0
 1926.56     .04       0 1927.06    .045       0  2033.3     .04       0
 2043.76     .12       0 2068.01     .06       0 2131.72     .12       0
 2168.51     .06       0 2797.79     .12       0
Bank Sta=1927.06,2033.3
XS Rating Curve= 0 ,0
Exp/Cntr=0.3,0.1

Type RM Length L Ch R = 1 ,129659.7,916.4,943,970
XS GIS Cut Line= 6
     2356897.794      344582.493     2356949.878      344343.777
     2357636.118      342809.414     2357636.728      342710.729
     2357845.062      342450.312     2357985.687      342288.854
#Sta/Elev= 30
       0   507.7   23.35505.4957   57.67503.2372   149.8  499.37   212.8  491.26
   316.2  487.72   735.7488.4494  768.28487.9868  1238.5  487.13  1338.3  477.45
 1434.78476.6921 1869.08480.6844  1897.2  480.44  1909.2  469.13  1996.2  469.11
  2043.7   469.2  2059.6     475  2075.5  476.73    2139   477.1  2166.8  473.61
  2186.6  476.12  2206.5   492.3  2230.3  524.08  2238.2  540.06  2246.2   552.6
    2270  568.99  2289.8  576.93  2345.4  581.35  2472.3  582.84  2571.5  592.07
#Mann= 9 ,-1 , 0
       0     .06       0   23.35    .016       0   57.67     .06       0
   735.7     .08       0  768.28     .06       0 1434.78     .12       0
 1869.08     .04       0  1909.2    .045       0  2043.7     .12       0
#XS Ineff= 2 , 0
       0    1238                       0
Permanent Ineff=
       F       F
Bank Sta=1909.2,2043.7
XS Rating Curve= 0 ,0
Exp/Cntr=0.3,0.1

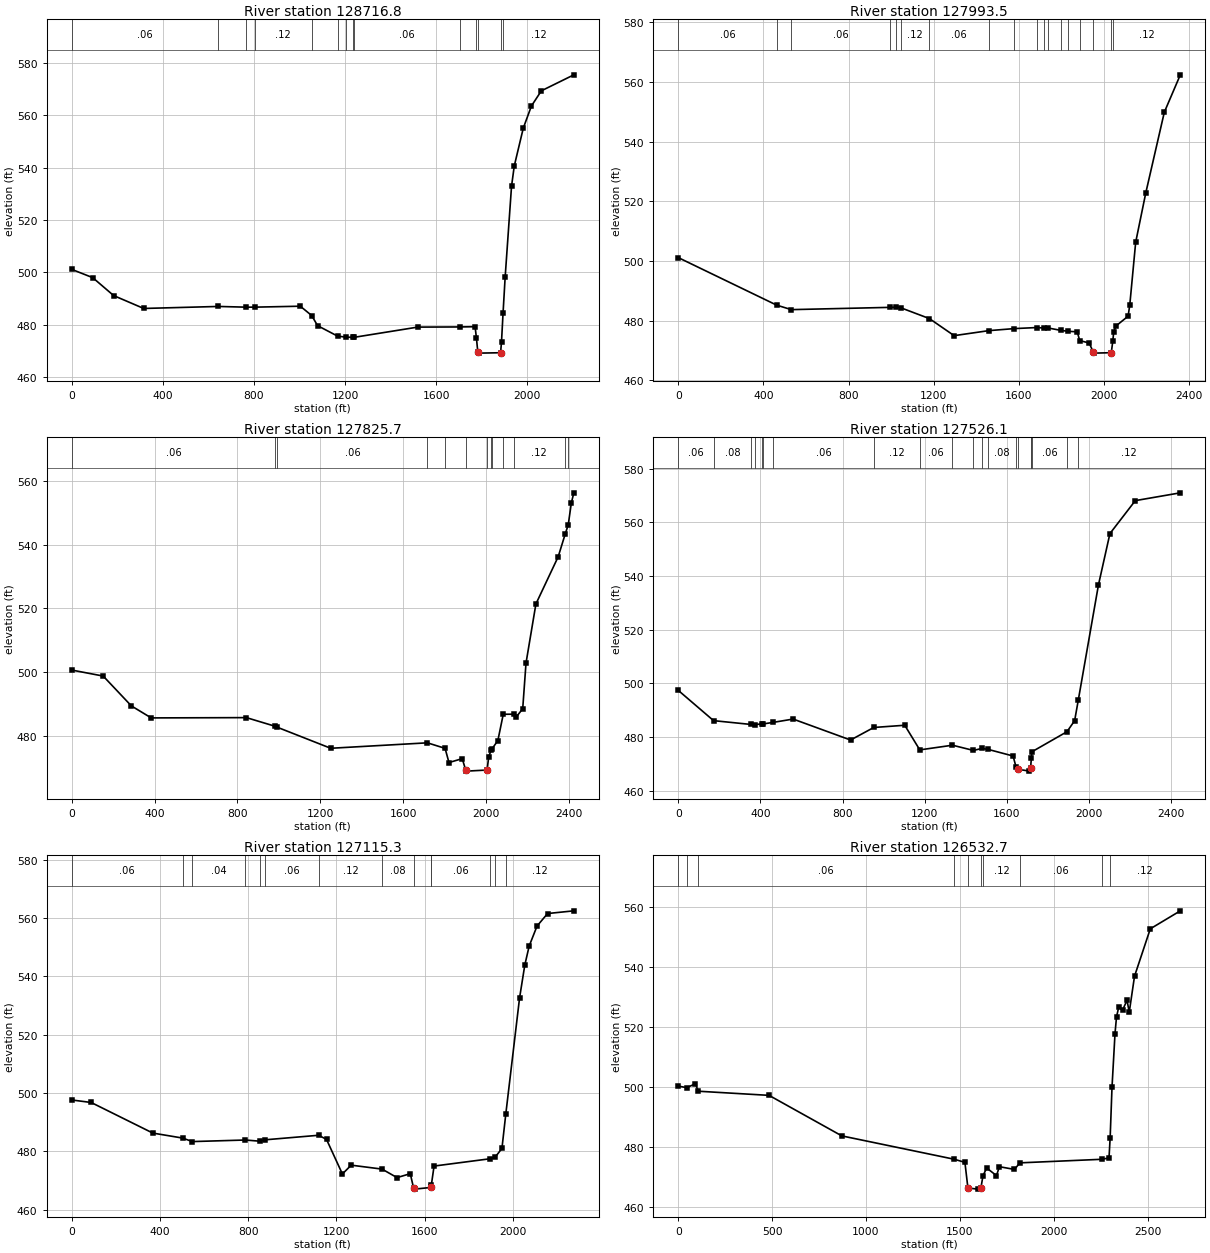
Type RM Length L Ch R = 1 ,128716.8,715.3,723.2,731.2
XS GIS Cut Line= 3
     2357171.666      344637.035     2358458.551      343176.492
      2358417.76      342922.192
#Sta/Elev= 30
       0  501.09    91.9  497.94   183.9  491.09   315.8  486.17  643.86486.9363
     764486.6655  802.91486.6712  1003.3  487.03 1053.23483.4755  1079.2   479.6
 1166.76475.6185 1203.45475.2124 1235.82475.1557 1239.92  475.15  1518.9  479.05
 1704.49479.1097  1770.7   479.2 1776.41474.9796  1782.7  469.41  1786.7  469.11
  1882.6  469.26  1886.6  473.39 1893.31484.2471  1902.6  498.11  1930.6  532.81
  1942.6  540.58  1982.3  555.06  2017.9  563.49  2061.5  569.29  2204.2   575.4
#Mann= 14 ,-1 , 0
       0     .06       0  643.86     .12       0     764     .06       0
  802.91     .12       0 1053.23     .06       0 1166.76     .08       0
 1203.45     .07       0 1235.82     .08       0 1239.92     .06       0
 1704.49     .12       0 1776.41     .04       0  1782.7    .045       0
  1882.6     .04       0 1893.31     .12       0
#XS Ineff= 2 , 0
       0     955                       0
Permanent Ineff=
       F       F
Bank Sta=1782.7,1882.6
XS Rating Curve= 0 ,0
Exp/Cntr=0.3,0.1

Type RM Length L Ch R = 1 ,127993.5,165.7,167.9,170
XS GIS Cut Line= 5
     2357159.645      344681.215     2357948.707      344316.632
     2358687.554      343922.714     2358982.214      343704.479
     2358990.895      343419.757
#Sta/Elev= 30
       0  501.14  462.52485.1891  531.28483.6924  994.73484.4541 1024.88484.4991
 1045.63484.3046 1179.47480.6947  1295.8  474.97 1457.65476.6402 1576.81477.3278
  1686.3477.6929 1719.73477.4946 1736.98477.5445 1797.58476.7331 1831.48476.4223
  1873.9  476.26 1885.45473.3122  1929.7  472.52  1949.6  469.43  1953.6  469.11
 2033.82469.2535 2041.09473.2162  2045.3  476.32  2057.2  478.29  2112.8   481.5
  2120.7  485.28  2148.4  506.29  2195.8  522.82  2282.9  549.88    2358  562.41
#Mann= 18 ,-1 , 0
       0     .06       0  462.52     .12       0  531.28     .06       0
  994.73     .12       0 1024.88     .06       0 1045.63     .12       0
 1179.47     .06       0 1457.65     .08       0 1576.81     .06       0
  1686.3     .12       0 1719.73     .06       0 1736.98     .12       0
 1797.58     .06       0 1831.48     .12       0 1885.45     .04       0
  1949.6    .045       0 2033.82     .04       0 2041.09     .12       0
#XS Ineff= 2 , 0
       0     775                       0
Permanent Ineff=
       F       F
Bank Sta=1949.6,2033.82
XS Rating Curve= 0 ,0
Exp/Cntr=0.3,0.1

Type RM Length L Ch R = 1 ,127825.7,299,299.6,300.2
XS GIS Cut Line= 5
     2357242.978      344768.021     2358010.339      344399.965
      2358808.95      344024.965     2359180.478       343781.91
     2359427.006      343795.798
#Sta/Elev= 30
       0  500.73   151.8  498.85   287.7  489.52   383.6  485.76   843.1  485.85
  980.62483.1695  992.09482.8416  1250.3  476.26 1717.18477.9654  1802.5 476.234
  1821.3  471.79  1885.3  473.02  1901.3  469.58  1905.3  469.11  2005.3  469.45
  2013.3  473.68 2026.08475.8275 2028.04475.9721  2057.3  478.67 2083.37486.9016
 2133.48486.9247  2145.3  485.99  2177.3  488.62  2193.2   502.9    2241   521.4
  2348.6  536.19 2381.82543.1464 2397.14546.1924  2412.3  553.09  2424.2  556.18
#Mann= 13 ,-1 , 0
       0     .06       0  980.62     .08       0  992.09     .06       0
 1717.18     .12       0  1802.5     .08       0  1901.3    .045       0
  2005.3     .04       0 2026.08     .08       0 2028.04     .06       0
 2083.37    .016       0 2133.48     .12       0 2381.82     .06       0
 2397.14     .12       0
#XS Ineff= 2 , 0
       0     827                       0
Permanent Ineff=
       F       F
Bank Sta=1901.3,2005.3
XS Rating Curve= 0 ,0
Exp/Cntr=0.3,0.1

Type RM Length L Ch R = 1 ,127526.1,408.7,410.8,412.9
XS GIS Cut Line= 3
     2357692.499      345074.535     2359470.538      343954.853
     2359734.166      343735.994
#Sta/Elev= 30
       0  497.36  172.02486.0613  355.87484.6281  372.84  484.57  407.37484.8593
  412.76484.8234  461.41485.4072   559.3  486.65   838.9  478.83  951.67483.5097
  1102.5  484.34 1175.71 475.152 1334.88476.8987 1436.88 474.947 1477.62 475.693
 1507.84475.3473  1629.8  472.87    1644468.8455  1653.8  467.93  1709.7  467.23
 1714.72468.4344 1719.29472.2575 1721.36474.4413 1891.97481.9233  1929.4  486.04
 1947.64493.9068  2045.3  536.67  2101.2  555.84  2224.7  568.13  2443.8  571.04
#Mann= 20 ,-1 , 0
       0     .06       0  172.02     .08       0  355.87     .04       0
  372.84     .06       0  407.37     .08       0  412.76     .04       0
  461.41     .06       0  951.67     .12       0 1175.71     .06       0
 1334.88     .12       0 1436.88     .06       0 1477.62     .12       0
 1507.84     .08       0    1644     .04       0  1653.8    .045       0
 1714.72     .04       0 1719.29     .12       0 1721.36     .06       0
 1891.97    .016       0 1947.64     .12       0
#XS Ineff= 2 , 0
       0    1055                       0
Permanent Ineff=
       F       F
Bank Sta=1653.8,1714.72
XS Rating Curve= 0 ,0
Exp/Cntr=0.3,0.1

Type RM Length L Ch R = 1 ,127115.3,588.5,582.6,576.6
XS GIS Cut Line= 3
     2357906.041      345319.327     2359666.458       344340.16
     2359864.374      344168.285
#Sta/Elev= 30
       0  497.64    87.9  496.78   367.7  486.28  502.81484.5724  546.67483.3691
  787.07483.9059   852.8   483.5  875.48483.9695 1119.63485.5354  1155.1  484.11
    1227  472.26    1267  475.28 1406.91473.9283  1474.8  471.01  1534.8  472.36
 1549.83467.4483  1554.8  467.06 1628.26467.6372 1630.07468.3069  1642.7  474.97
 1897.83477.4898 1919.65478.0148  1950.5  481.04 1967.98492.8394  2030.3  532.59
  2054.1  543.92    2074  550.45  2109.7  557.31  2157.4  561.59  2276.5  562.52
#Mann= 14 ,-1 , 0
       0     .06       0  502.81     .12       0  546.67     .04       0
  787.07     .06       0   852.8     .12       0  875.48     .06       0
 1119.63     .12       0 1406.91     .08       0 1549.83    .045       0
 1628.26     .04       0 1630.07     .06       0 1897.83     .12       0
 1919.65    .016       0 1967.98     .12       0
#XS Ineff= 2 , 0
       0    1020                       0
Permanent Ineff=
       F       F
Bank Sta=1549.83,1628.26
XS Rating Curve= 0 ,0
Exp/Cntr=0.3,0.1

Type RM Length L Ch R = 1 ,126532.7,418.5,415.3,412.2
XS GIS Cut Line= 3
     2358098.749      346079.744     2359999.791      344610.994
     2359906.041      344355.785
#Sta/Elev= 30
       0  500.19   45.78499.6667    91.9  500.99  106.34498.4824   483.7   497.1
   871.4  483.58 1469.91 475.798  1526.9  474.76  1542.9  466.21  1594.7  465.83
 1611.91466.1573 1623.29470.3178  1642.9  472.87  1694.8  470.35  1710.8  473.31
  1790.8   472.4 1819.58474.5926 2255.06475.7776  2294.4  476.22 2300.44 482.841
  2310.4  499.83  2326.4  517.73  2334.4  523.27  2346.4  526.58  2366.4   525.5
  2390.3  528.79  2402.3  524.88  2430.3  536.83  2514.3  552.64  2674.2  558.64
#Mann= 10 ,-1 , 0
       0     .06       0   45.78     .12       0  106.34     .06       0
 1469.91     .12       0  1542.9    .045       0 1611.91     .04       0
 1623.29     .12       0 1819.58     .06       0 2255.06    .016       0
 2300.44     .12       0
#XS Ineff= 2 , 0
       0    1300                       0
Permanent Ineff=
       F       F
Bank Sta=1542.9,1611.91
XS Rating Curve= 0 ,0
Exp/Cntr=0.3,0.1

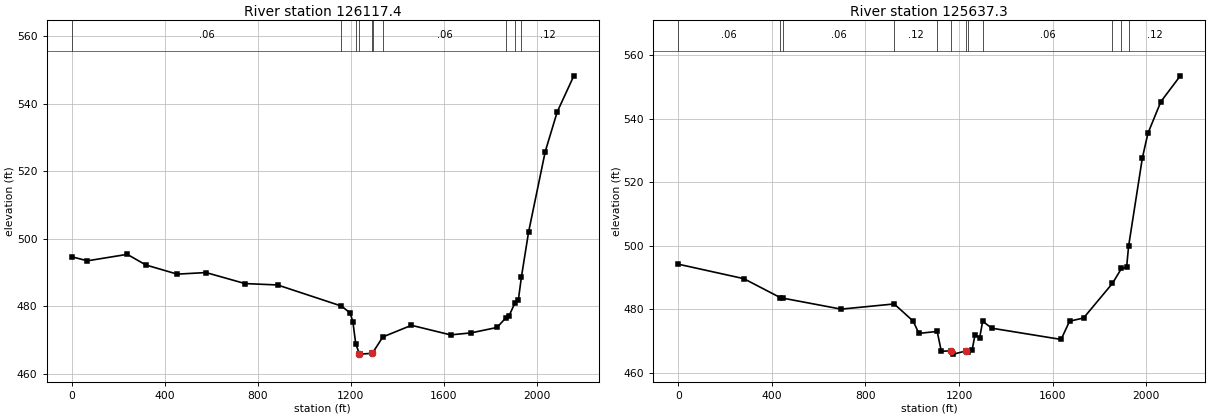
Type RM Length L Ch R = 1 ,126117.4,485.5,480.1,474.9
XS GIS Cut Line= 4
     2358975.443      346388.507     2359135.208       345871.41
     2360165.543      344912.224     2360367.847      344854.049
#Sta/Elev= 30
       0  494.63    67.6  493.45   238.8  495.36   318.4  492.22   453.7   489.5
   577.2  489.97   745.2  486.71   885.1   486.3 1159.86480.0582  1197.1  478.02
  1209.1   475.4 1221.14468.9369  1237.1  465.88  1241.1  465.83  1293.1  466.08
 1293.73466.1813 1337.83470.9154    1461  474.36    1629  471.53    1717  472.11
  1828.9  473.72 1867.14476.5904  1880.9  477.17 1906.47481.0525  1920.9  481.94
 1933.85488.6451  1964.8  501.99  2036.3  525.76  2087.9  537.52  2159.4  548.19
#Mann= 10 ,-1 , 0
       0     .06       0 1159.86     .12       0 1221.14     .04       0
  1237.1    .045       0  1293.1     .04       0 1293.73     .12       0
 1337.83     .06       0 1867.14     .12       0 1906.47    .016       0
 1933.85     .12       0
#XS Ineff= 2 , 0
       0    1060                       0
Permanent Ineff=
       F       F
Bank Sta=1237.1,1293.1
XS Rating Curve= 0 ,0
Exp/Cntr=0.3,0.1

Type RM Length L Ch R = 1 ,125637.3,444.3,448.1,451.7
XS GIS Cut Line= 4
     2359309.645      346579.479     2360046.723      345668.281
     2360516.678       345091.92     2360550.964      344865.069
#Sta/Elev= 30
       0  494.18     280  489.62  436.21483.6369   447.1483.4688     696  480.01
  922.65481.6436    1004  476.22    1028  472.36 1106.36472.9848    1124  466.72
  1166.1466.8891    1176  465.83    1228  466.81 1236.22466.5322    1256  467.27
    1268  471.95  1287.9  470.99 1300.61476.1794  1339.9     474  1635.8  470.46
  1671.8   476.2  1731.8  477.22 1855.07 488.118 1893.68492.8328  1915.7  493.19
 1924.06499.7997  1982.9  527.64  2006.6   535.4    2062   545.4  2145.1  553.54
#Mann= 12 ,-1 , 0
       0     .06       0  436.21     .12       0   447.1     .06       0
  922.65     .12       0 1106.36     .04       0  1166.1    .045       0
    1228     .04       0 1236.22     .12       0 1300.61     .06       0
 1855.07     .12       0 1893.68    .016       0 1924.06     .12       0
#XS Ineff= 2 , 0
       0     800                       0
Permanent Ineff=
       F       F
Bank Sta=1166.1,1228
XS Rating Curve= 0 ,0
Exp/Cntr=0.3,0.1