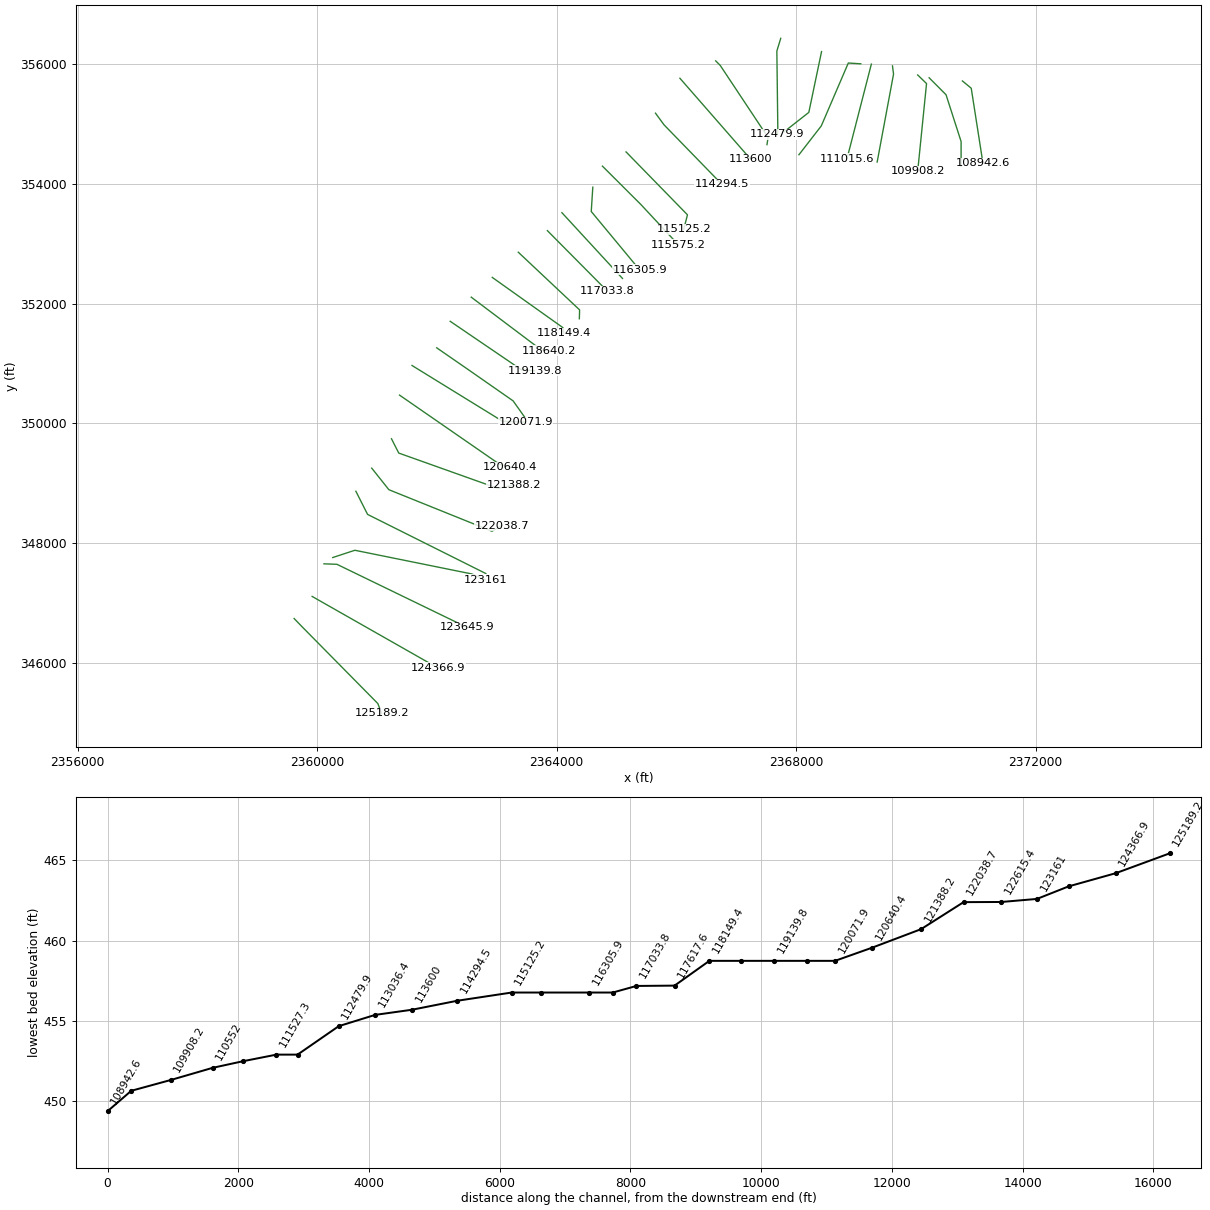
HEC-RAS study BACKCREEK.prj: BACKCREEK

--- BACKCREEK.g01 (geometry) --- (continued)

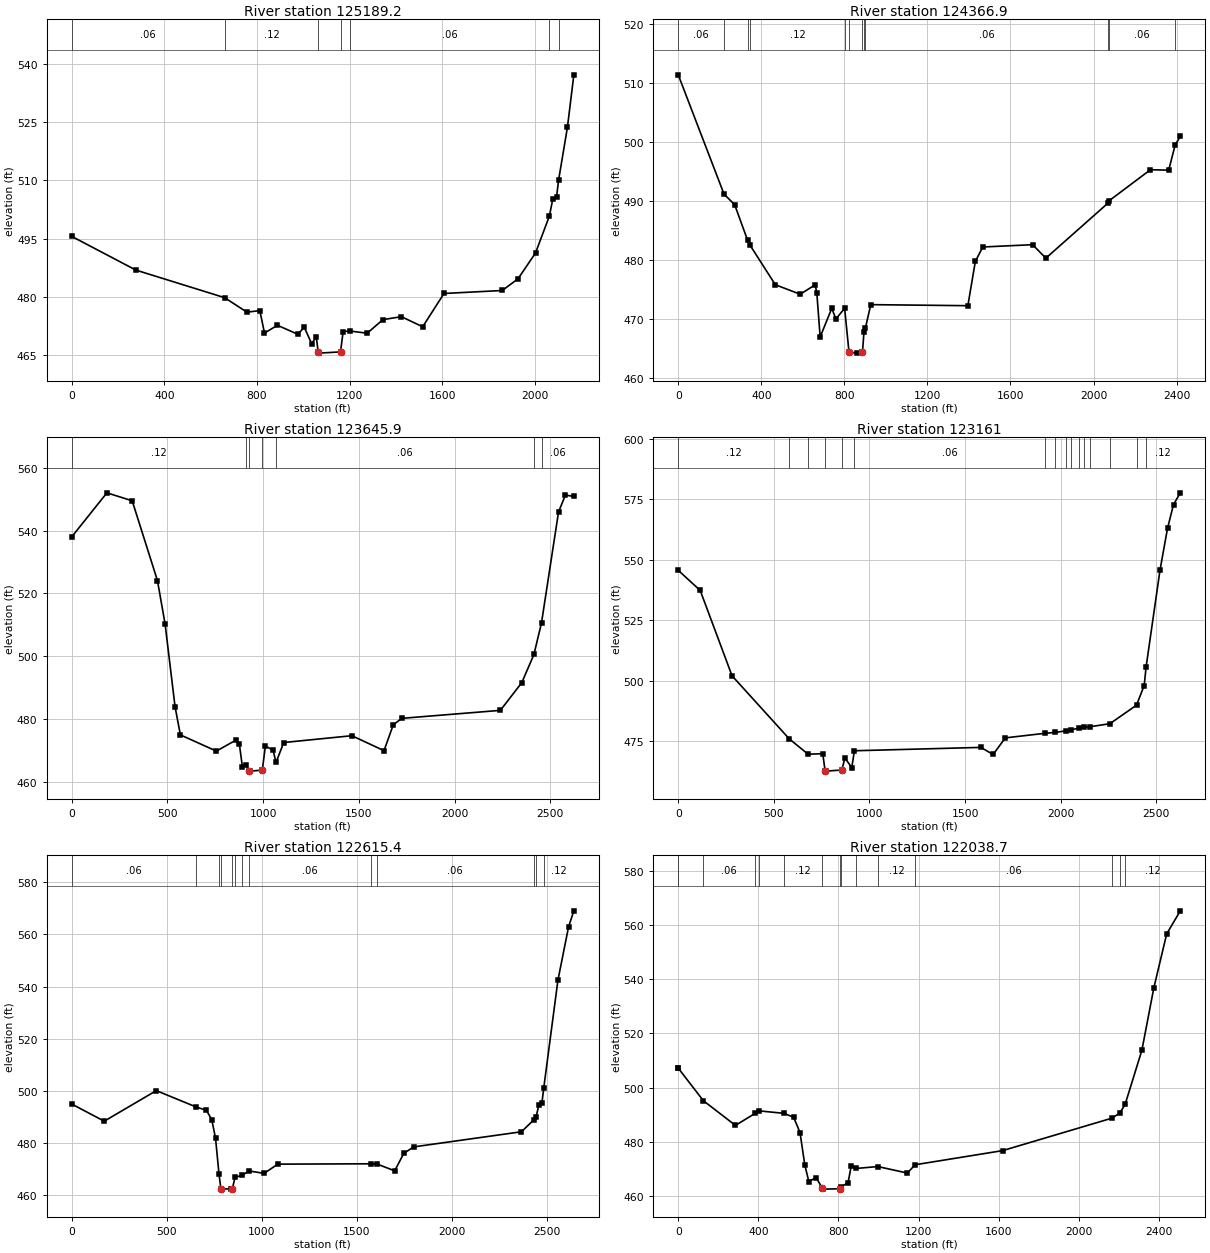
Type RM Length L Ch R = 1 ,125189.2,811.5,822.3,833.1
XS GIS Cut Line= 4
     2359615.242      346742.504      2359741.11      346612.296
     2361012.708      345323.248     2361077.916      345158.303
#Sta/Elev= 30
       0  495.55     277  486.86  660.47479.7365   756.7     476   812.6  476.39
   832.6   470.6   888.6  472.61   976.5  470.29  1004.5  472.11  1036.5  467.84
  1056.5  469.62  1064.5  465.76  1068.5  465.42 1161.18465.7384  1172.4     471
  1200.8 471.137  1276.3  470.56  1344.3  474.07  1424.2  474.83  1516.1  472.22
  1608.1  480.82  1859.9  481.59  1927.8   484.6  2003.6  491.27 2063.67500.8331
  2078.5  505.31  2094.3  505.66 2103.28510.0805  2141.6  523.78  2169.2  537.27
#Mann= 7 ,-1 , 0
       0     .06       0  660.47     .12       0  1064.5    .045       0
 1161.18     .12       0  1200.8     .06       0 2063.67    .016       0
 2103.28     .12       0
Bank Sta=1064.5,1161.18
XS Rating Curve= 0 ,0
Exp/Cntr=0.3,0.1

Type RM Length L Ch R = 1 ,124366.9,718.6,721,723.5
XS GIS Cut Line= 2
     2359916.168      347111.428      2362018.31      345916.405
#Sta/Elev= 30
       0  511.31  220.47491.1182   271.8  489.32  333.71 483.329  346.64482.4168
   467.6  475.77   587.5  474.16   659.5  475.76   667.5  474.36   683.5  466.92
   739.4  471.77   759.4  469.98  801.42471.7725  822.41464.3415   860.5  464.19
   887.3  464.32   894.7 467.835  901.28468.4243   927.3   472.4  1394.9  472.22
  1430.9  479.72  1466.8  482.16  1706.6  482.55  1770.6  480.27 2067.93489.5324
 2075.77490.0057  2274.2  495.24  2362.1  495.17 2393.41499.4451  2418.1  500.88
#Mann= 12 ,-1 , 0
       0     .06       0  220.47     .12       0  333.71     .06       0
  346.64     .12       0  801.42     .04       0  822.41    .045       0
   887.3     .04       0   894.7     .12       0  901.28     .06       0
 2067.93     .12       0 2075.77     .06       0 2393.41    .016       0
#XS Ineff= 2 , 0
       0                    1510       0
Permanent Ineff=
       F       F
Bank Sta=822.41,887.3
XS Rating Curve= 0 ,0
Exp/Cntr=0.3,0.1

Type RM Length L Ch R = 1 ,123645.9,475.8,484.8,493.9
XS GIS Cut Line= 3
     2360114.497      347656.032     2360329.941      347648.175
      2362495.74      346597.828
#Sta/Elev= 30
       0  538.06   183.6  552.08   315.6  549.54   447.5  524.11   487.5  510.27
   539.5  483.89   567.4  474.92   755.4  469.75   859.3  473.32   875.3  472.04
   891.3  464.74  910.44465.2834   927.3  463.55   931.3  463.37   995.3  463.69
  1011.3  471.36  1051.3  470.08 1066.99 466.142  1107.2  472.49  1463.1  474.66
    1631  469.89    1679  478.08    1723  480.19  2238.8  482.74  2350.8  491.58
 2414.05500.5509 2453.75510.6623  2542.7     546  2578.7  551.37  2622.6  550.91
#Mann= 7 ,-1 , 0
       0     .12       0  910.44     .04       0   927.3    .045       0
   995.3     .12       0 1066.99     .06       0 2414.05    .016       0
 2453.75     .06       0
Bank Sta=927.3,995.3
XS Rating Curve= 0 ,0
Exp/Cntr=0.3,0.1

Type RM Length L Ch R = 1 ,123161  ,555.3,545.6,536.1
XS GIS Cut Line= 4
     2360260.497      347761.023     2360629.421       347882.55
     2362583.282      347486.883      2362808.24      347392.099
#Sta/Elev= 30
       0  545.61   114.9  537.29   281.4  502.01  581.03475.9051  679.42469.5793
     756   469.8     768  462.74     772  462.59   855.8  463.05   871.8  468.03
   907.8  464.03   921.3471.0125  1582.9   472.4  1646.9  469.47  1710.8  476.34
 1918.03478.2235 1972.73478.5968 2027.78479.2407 2056.58  479.64 2094.18480.3881
 2123.31480.8109 2153.74480.9442 2257.72482.1951 2397.03489.8569  2437.1  497.97
 2447.24 505.705  2519.8  545.68  2559.1  562.95  2590.6  572.82  2626.1  577.65
#Mann= 16 ,-1 , 0
       0     .12       0  581.03     .06       0  679.42     .12       0
     768    .045       0   855.8     .12       0   921.3     .06       0
 1918.03     .08       0 1972.73     .06       0 2027.78     .08       0
 2056.58     .06       0 2094.18     .08       0 2123.31     .06       0
 2153.74     .08       0 2257.72     .06       0 2397.03    .016       0
 2447.24     .12       0
Bank Sta=768,855.8
XS Rating Curve= 0 ,0
Exp/Cntr=0.3,0.1

Type RM Length L Ch R = 1 ,122615.4,573.6,576.7,579.7
XS GIS Cut Line= 3
     2360646.782      348867.794     2360842.094      348481.509
     2362817.457      347493.541
#Sta/Elev= 30
       0  494.99   170.8  488.43   444.8  500.14  651.07493.9747   708.4  492.57
   736.4  489.04   756.4  481.88  774.57468.2097   784.3  462.58   840.2   462.4
  845.16462.6132  858.99466.9583  897.25467.6756  931.07469.3737    1012  468.44
  1083.9  471.97    1576472.1065 1605.09472.0418  1698.9  469.41  1746.9   476.1
  1798.8  478.58  2365.9  484.38 2430.21488.9037  2442.3  489.92  2457.8  494.73
  2473.8  495.54 2482.98501.0398  2557.6  542.38  2613.6  562.87  2641.5  569.03
#Mann= 13 ,-1 , 0
       0     .06       0  651.07     .12       0  774.57     .04       0
   784.3    .045       0  845.16     .12       0  858.99     .06       0
  897.25     .12       0  931.07     .06       0    1576     .08       0
 1605.09     .06       0 2430.21     .12       0  2442.3    .016       0
 2482.98     .12       0
Bank Sta=784.3,845.16
XS Rating Curve= 0 ,0
Exp/Cntr=0.3,0.1

Type RM Length L Ch R = 1 ,122038.7,649,650.5,652
XS GIS Cut Line= 4
     2360911.539      349254.078     2361197.997      348893.835
      2362918.95      348200.517     2363086.018      348294.877
#Sta/Elev= 30
       0  507.18    1.23507.0631  125.72495.0952   285.7  485.98  384.17490.4306
  401.28491.3733  527.69490.4458   576.2  488.99   608.2  483.33   632.2  471.29
   652.2  465.21   688.2  466.68   720.2   462.7   724.2  462.39   808.1  462.52
  810.75463.0765   848.1   464.8   864.1     471  887.47470.0409  997.03470.7457
    1144  468.34 1183.14471.4143  1619.9  476.64 2164.38488.6217 2205.11490.4858
 2232.18493.8307  2315.6   513.8  2375.6  537.01  2439.5  556.87  2507.5   565.4
#Mann= 15 ,-1 , 0
       0     .12       0    1.23     .08       0  125.72     .06       0
  384.17     .08       0  401.28     .06       0  527.69     .12       0
   720.2    .045       0   808.1     .04       0  810.75     .12       0
  887.47     .06       0  997.03     .12       0 1183.14     .06       0
 2164.38     .12       0 2205.11    .016       0 2232.18     .12       0
Bank Sta=720.2,808.1
XS Rating Curve= 0 ,0
Exp/Cntr=0.3,0.1

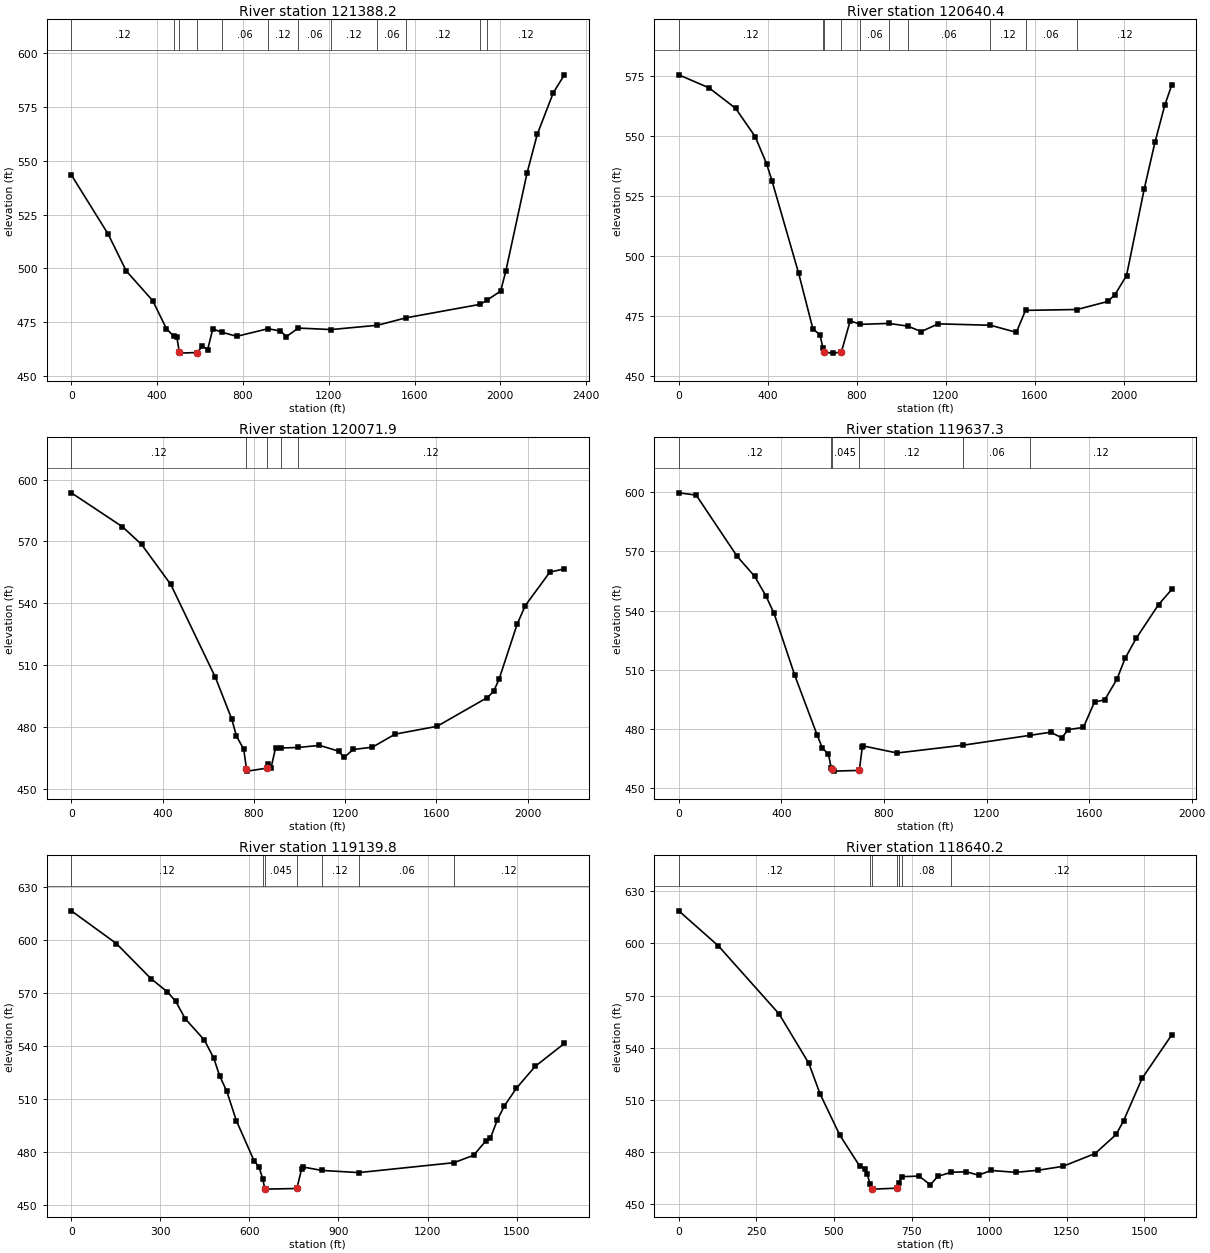
Type RM Length L Ch R = 1 ,121388.2,757.7,747.8,738
XS GIS Cut Line= 4
       2361241.4       349744.53     2361362.928      349505.814
     2363018.306       348916.06     2363285.671       348971.96
#Sta/Elev= 30
       0  543.42   171.9   515.9   255.9  498.87   379.7  485.01   443.6  471.96
  478.45468.4942   491.5  468.39   503.5  461.08   507.5  460.71   587.4     461
   611.3  464.07   635.3  462.28   659.3  471.91  702.77470.3926   771.1  468.51
  917.12472.0378   974.8  470.96  1002.7   468.4 1057.83472.3384 1211.42  471.65
  1427.1473.6425  1559.8477.0827 1906.71483.3765 1938.03485.3267  2001.2  489.51
  2025.2  498.74  2124.1  544.23  2171.6  562.21  2246.8  581.59  2298.3  589.86
#Mann= 12 ,-1 , 0
       0     .12       0  478.45     .04       0   503.5    .045       0
   587.4     .12       0  702.77     .06       0  917.12     .12       0
 1057.83     .06       0 1211.42     .12       0  1427.1     .06       0
  1559.8     .12       0 1906.71     .06       0 1938.03     .12       0
Bank Sta=503.5,587.4
XS Rating Curve= 0 ,0
Exp/Cntr=0.3,0.1

Type RM Length L Ch R = 1 ,120640.4,566.5,568.5,570.4
XS GIS Cut Line= 3
     2361375.948      350473.696     2363044.722      349319.779
     2363224.907      349267.099
#Sta/Elev= 30
       0  575.48   135.8  570.08   255.6  561.52   343.5  549.75   395.4  538.34
   419.4  531.26   539.2  492.75   603.1  469.68     635  467.15  647.81 461.846
     651  459.94   691.9  459.56   730.9  459.96   770.8  473.04   815.8471.5395
  943.82  471.94 1029.29470.8156  1090.3  468.53  1166.2  471.76 1401.49471.1685
  1517.7  468.22 1558.91477.3697 1790.65477.7291    1929  481.08    1961  483.92
  2012.9  491.83  2092.8  528.03  2140.7  547.33  2184.6  562.72  2216.6  571.33
#Mann= 10 ,-1 , 0
       0     .12       0  647.81     .04       0     651    .045       0
   730.9     .12       0   815.8     .06       0  943.82     .12       0
 1029.29     .06       0 1401.49     .12       0 1558.91     .06       0
 1790.65     .12       0
Bank Sta=651,730.9
XS Rating Curve= 0 ,0
Exp/Cntr=0.3,0.1

Type RM Length L Ch R = 1 ,120071.9,436.6,434.6,432.6
XS GIS Cut Line= 3
     2361584.282      350968.488     2363099.039      350035.328
     2363480.983      350022.307
#Sta/Elev= 30
       0  593.57   223.9  577.15   307.8  568.58   435.8   549.2   631.7  504.11
   703.6  483.86   723.6  475.76   755.6   469.4   767.6  459.99   771.6  458.74
   855.6  460.15   863.6  462.25   875.6  460.36   895.6  470.18  919.23469.9567
  994.66470.1958  1087.5  471.22  1171.4  468.43  1195.4  465.36  1235.4  469.22
  1319.4  470.32  1419.3  476.66  1603.2  480.45  1822.9  494.34  1850.8  497.34
  1874.7   503.2  1954.3  529.95  1990.1  538.98  2097.6  555.15  2161.3  556.73
#Mann= 5 ,-1 , 0
       0     .12       0   767.6    .045       0   855.6     .12       0
  919.23     .06       0  994.66     .12       0
Bank Sta=767.6,855.6
XS Rating Curve= 0 ,0
Exp/Cntr=0.3,0.1

Type RM Length L Ch R = 1 ,119637.3,497.2,497.4,497.8
XS GIS Cut Line= 4
     2361996.608      351263.627     2362526.254      350897.852
     2363272.816       350377.52     2363486.296      350076.864
#Sta/Elev= 30
       0  599.54      68  598.39   227.9  567.37   295.8  557.32   339.8  547.42
   371.8  538.49   451.8  507.39   539.7  476.99   559.7  470.48   583.7  467.25
  594.44460.3451   595.7  459.63   603.7  458.74  704.03459.1031   715.5  470.76
   719.5  471.48   851.2  467.91 1110.19471.8891 1370.54476.8678  1449.9  478.43
  1493.8  475.57  1517.8  479.76  1577.5  480.84  1621.1  493.75  1660.7  494.78
  1708.3   505.2    1740  515.75  1783.6  525.94  1870.9  543.03  1922.4   550.7
#Mann= 6 ,-1 , 0
       0     .12       0  594.44     .04       0   595.7    .045       0
  704.03     .12       0 1110.19     .06       0 1370.54     .12       0
Bank Sta=595.7,704.03
XS Rating Curve= 0 ,0
Exp/Cntr=0.3,0.1

Type RM Length L Ch R = 1 ,119139.8,501.4,499.6,497.8
XS GIS Cut Line= 3
     2362222.303      351706.335     2363415.622      350894.325
     2363632.893      350881.682
#Sta/Elev= 30
       0  616.28   151.9  597.75   267.9  577.95   323.9  570.35   351.8  565.01
   383.8  555.14   447.8  543.22   479.8  532.92   499.8  522.79   523.8  514.06
   555.8  497.56   615.7  474.75   631.7  471.48  644.72464.6741   651.7  458.92
   655.7  458.74   759.7   459.1   775.7  470.09   779.7  471.29  843.53469.3312
  968.72468.1012 1289.01473.7123  1355.4  477.92  1395.4  485.85  1411.4  487.43
  1435.4  498.06  1459.2  505.94  1498.8  515.73  1562.1  528.17    1661  541.23
#Mann= 7 ,-1 , 0
       0     .12       0  644.72     .04       0   651.7    .045       0
   759.7     .08       0  843.53     .12       0  968.72     .06       0
 1289.01     .12       0
Bank Sta=651.7,759.7
XS Rating Curve= 0 ,0
Exp/Cntr=0.3,0.1

Type RM Length L Ch R = 1 ,118640.2,489.7,490.8,491.8
XS GIS Cut Line= 3
     2362573.431      352109.547      2363737.06      351233.245
     2363867.268      351215.884
#Sta/Elev= 30
       0  618.78   127.7  598.61   323.3  559.45     419  531.06     455  513.56
   518.8  489.75   582.7     472   598.6  470.34   606.6  467.64  616.24461.6318
  622.23458.9243   626.6  458.74   702.4  459.29  708.31462.3925  718.39465.8981
   774.2  466.24   810.2  461.21   834.1  466.06  877.32468.4532   925.9  468.71
   965.8  466.77  1005.7  469.49  1085.5  468.39  1157.4   469.6  1237.2  471.84
    1341  479.22  1408.8  490.18  1432.7  498.09  1492.5  522.52    1588   547.5
#Mann= 7 ,-1 , 0
       0     .12       0  616.24     .04       0  622.23    .045       0
   702.4     .04       0  708.31     .12       0  718.39     .08       0
  877.32     .12       0
Bank Sta=622.23,702.4
XS Rating Curve= 0 ,0
Exp/Cntr=0.3,0.1

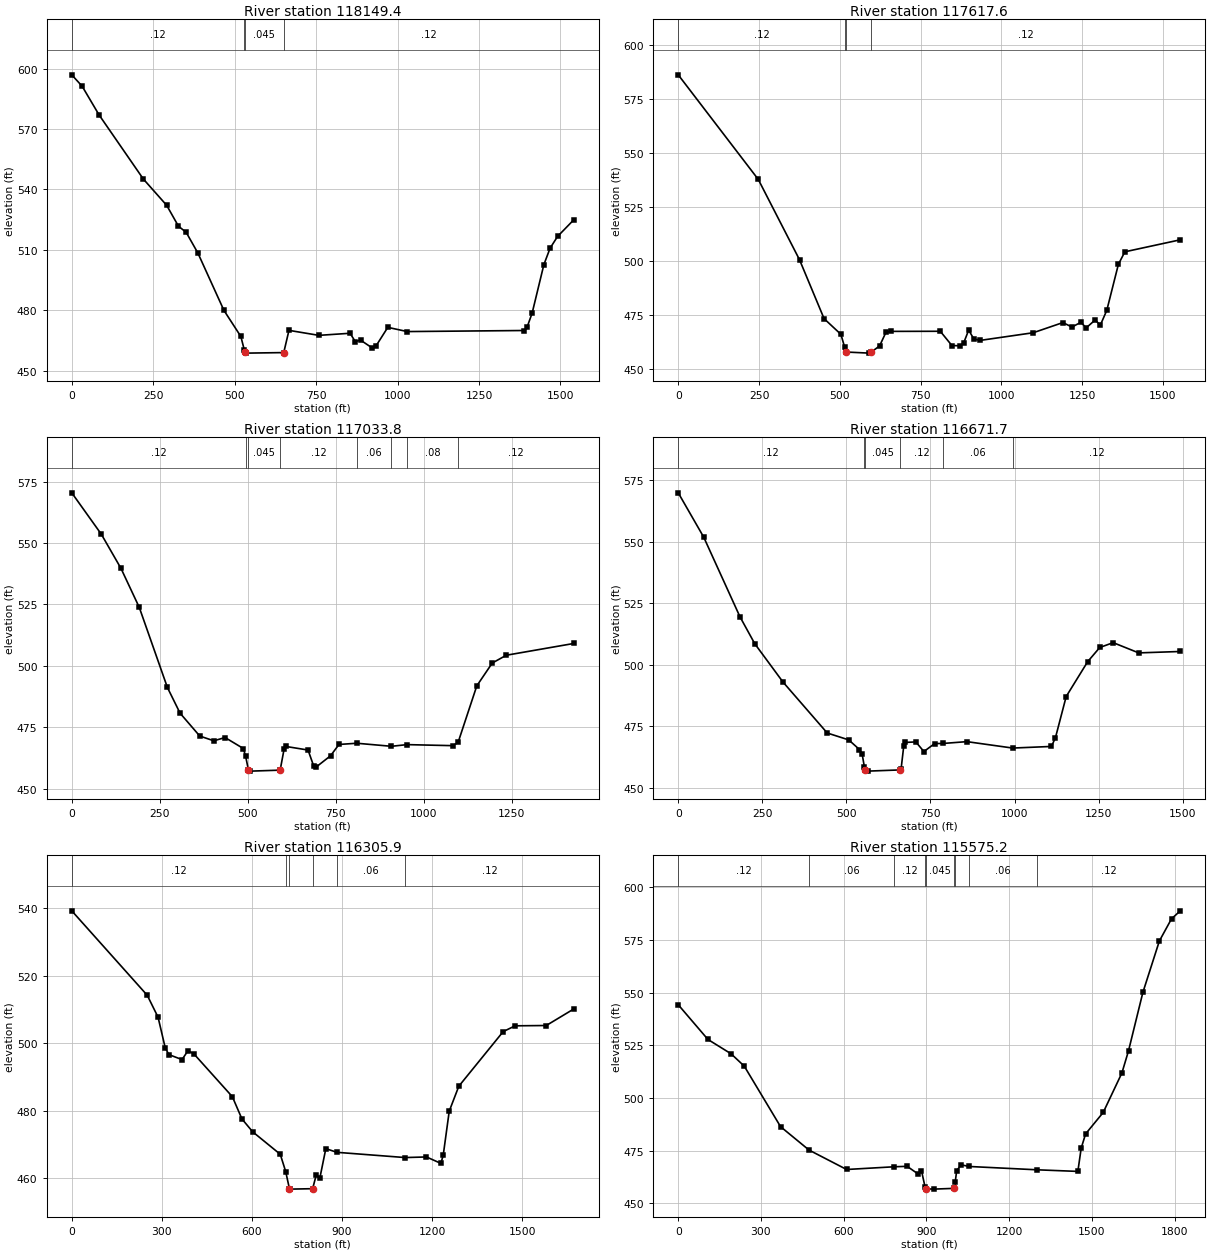
Type RM Length L Ch R = 1 ,118149.4,536.9,531.8,526.7
XS GIS Cut Line= 3
     2362924.994      352439.408     2364105.983      351599.564
     2364119.004      351508.419
#Sta/Elev= 30
       0  596.87    31.9  591.19    83.8  576.97   219.6  545.17   291.4  532.09
   327.4  521.76   351.3  518.67   387.2  508.39   467.1  479.95     519  467.01
   529.7460.2585     531  459.42     535  458.74   650.7  459.01   666.7  470.04
   758.5  467.56   854.3   468.6   870.3  464.45   886.3  465.22   922.2  461.31
   934.2  462.38   970.1  471.53    1030  469.44  1389.3  469.97  1397.3  471.47
  1413.2  478.62  1449.2  502.66  1468.3  510.84  1491.4  516.68  1541.2  524.95
#Mann= 4 ,-1 , 0
       0     .12       0   529.7     .04       0     531    .045       0
   650.7     .12       0
Bank Sta=531,650.7
XS Rating Curve= 0 ,0
Exp/Cntr=0.3,0.1

Type RM Length L Ch R = 1 ,117617.6,585.2,583.8,582.4
XS GIS Cut Line= 3
     2363359.021      352860.415     2364383.327      351896.873
     2364378.987      351749.304
#Sta/Elev= 30
       0  586.07   247.7  537.64   375.5   500.4   451.4  473.16   503.4  465.91
  514.79460.0745   519.4  457.71   591.3   457.2  597.16457.6571   623.2  460.53
   643.2  466.96   659.2  467.27     811  467.32     847  460.72   870.9   460.6
   882.9  461.72   898.9  467.87   914.9  463.74   934.8   463.1  1098.6  466.64
  1190.5  471.35  1218.5  469.28  1246.5   471.5  1262.4  468.88  1290.4  472.55
  1306.4  470.17  1326.4  477.03  1362.3  498.35  1382.3  504.12  1553.9  509.68
#Mann= 4 ,-1 , 0
       0     .12       0  514.79     .04       0   519.4    .045       0
  597.16     .12       0
Bank Sta=519.4,597.16
XS Rating Curve= 0 ,0
Exp/Cntr=0.3,0.1

Type RM Length L Ch R = 1 ,117033.8,363.4,362,360.6
XS GIS Cut Line= 2
     2363845.132      353220.658     2364849.937      352207.248
#Sta/Elev= 30
       0   570.4      84  553.56   139.9  539.65   191.9  523.78   271.8  491.21
   307.8  480.76   363.8  471.45   403.8  469.52   435.7  470.85   487.7  466.38
  494.26 463.152  502.27457.5718   507.7  457.18  592.32457.5742   603.6  466.23
   607.6  467.24   671.6  465.76   687.6  459.27   695.6  458.95   735.5  463.42
   759.5  468.03  810.24468.5226  908.75467.2806  952.82467.9635  1083.3  467.54
 1098.08468.8638  1151.3  491.88  1195.2  501.16  1235.2  504.33  1427.1  509.12
#Mann= 8 ,-1 , 0
       0     .12       0  494.26     .04       0  502.27    .045       0
  592.32     .12       0  810.24     .06       0  908.75     .12       0
  952.82     .08       0 1098.08     .12       0
Bank Sta=502.27,592.32
XS Rating Curve= 0 ,0
Exp/Cntr=0.3,0.1

Type RM Length L Ch R = 1 ,116671.7,367,365.9,364.7
XS GIS Cut Line= 2
     2364088.188      353520.137     2365099.473      352422.047
#Sta/Elev= 30
       0  569.84    75.8  551.82   183.6  519.46   227.5  508.54   311.3  492.99
     443  472.26   506.9  469.46   538.8  465.55   546.8  463.72  553.56458.3832
   554.8  457.23   562.8  456.77  660.74457.2647   662.6  457.66   670.6  467.05
   674.6  468.44   706.5  468.63   730.4  464.72   762.4  467.98  786.12467.9977
   858.2  468.75  994.33466.1425  1109.6   466.8  1121.6  470.38  1153.5  487.09
  1217.4  501.25  1253.3     507  1293.2  508.97  1369.1  504.81  1492.8  505.38
#Mann= 6 ,-1 , 0
       0     .12       0  553.56     .04       0   554.8    .045       0
  660.74     .12       0  786.12     .06       0  994.33     .12       0
Bank Sta=554.8,660.74
XS Rating Curve= 0 ,0
Exp/Cntr=0.3,0.1

Type RM Length L Ch R = 1 ,116305.9,729,730.6,732.3
XS GIS Cut Line= 3
     2364603.916      353946.666     2364577.874      353540.416
     2365385.166      352566.458
#Sta/Elev= 30
       0   539.3   251.4  514.25   287.4  507.75   311.3  498.66   323.3  496.67
   367.2  495.18   387.1  497.83   407.1  496.84   534.8  484.18   566.7  477.58
   602.6  473.76   694.4   467.1  712.46461.9709  724.84456.9235   726.3  456.77
   802.2   456.9   814.1  460.94   826.1  460.01   846.1  468.78  882.81467.6872
 1110.24466.1316  1181.3  466.31  1229.2  464.41  1237.1  466.83  1257.1  479.89
    1289  487.29  1436.7  503.48  1476.6   505.2  1580.3  505.29  1672.1  510.21
#Mann= 6 ,-1 , 0
       0     .12       0  712.46     .04       0  724.84    .045       0
   802.2     .12       0  882.81     .06       0 1110.24     .12       0
Bank Sta=724.84,802.2
XS Rating Curve= 0 ,0
Exp/Cntr=0.3,0.1

Type RM Length L Ch R = 1 ,115575.2,449.5,450.1,450.5
XS GIS Cut Line= 3
     2364764.297      354298.412     2365408.178      353655.547
     2366028.516      352988.726
#Sta/Elev= 30
       0  544.28   107.8  527.79   191.6     521   239.4  515.14   371.1  486.41
  474.33475.3069   610.6  466.09  782.65467.3765     830  467.59     870  463.94
   881.9  465.58  894.88457.8787   897.9  456.95   925.8  456.77  1001.7  457.14
 1004.18459.9858  1009.7  465.48  1025.7  468.32 1055.25467.5174 1302.23465.9358
  1449.1  465.18  1461.1  476.17  1477.1  482.97    1541  493.16  1608.9  511.93
  1632.9  522.47  1684.8  550.11  1744.7  574.55  1788.7  585.06  1820.6  588.85
#Mann= 9 ,-1 , 0
       0     .12       0  474.33     .06       0  782.65     .12       0
  894.88     .04       0   897.9    .045       0  1001.7     .04       0
 1004.18     .12       0 1055.25     .06       0 1302.23     .12       0
Bank Sta=897.9,1001.7
XS Rating Curve= 0 ,0
Exp/Cntr=0.3,0.1

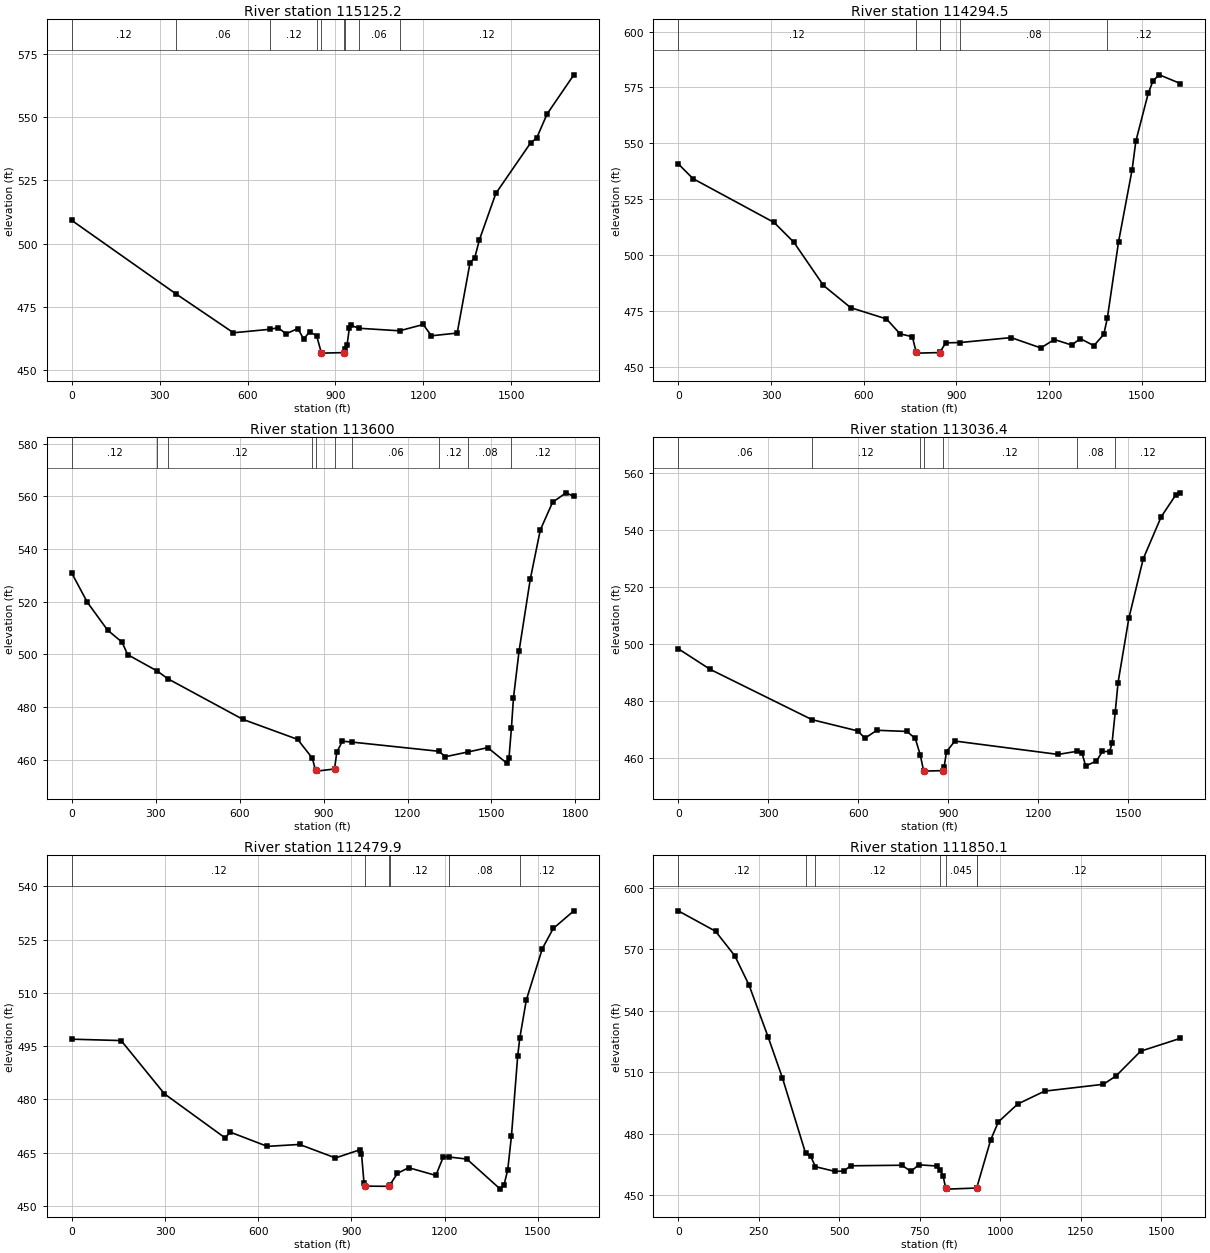
Type RM Length L Ch R = 1 ,115125.2,831,830.6,830.2
XS GIS Cut Line= 3
     2365159.227      354535.597     2366184.542      353485.415
     2366123.778        353246.7
#Sta/Elev= 30
       0   509.2  356.23480.1437   551.9  464.81  677.25466.1934   703.9  466.82
   731.8  464.41   771.8  466.49   791.8   462.3   811.8  465.22  836.03463.6202
   851.8  456.95   855.8  456.77   927.8  456.98  933.81458.3568   939.8  459.97
   947.8  466.86   951.8  467.82  979.63466.5989 1119.02465.5885  1199.8  468.08
  1227.8  463.62  1315.7   464.7  1359.7  492.52  1375.7  494.44  1391.7  501.57
  1447.7  519.86    1567  539.92  1586.9  541.68  1622.6  551.22    1714  566.71
#Mann= 9 ,-1 , 0
       0     .12       0  356.23     .06       0  677.25     .12       0
  836.03     .04       0   851.8    .045       0   927.8     .04       0
  933.81     .12       0  979.63     .06       0 1119.02     .12       0
Bank Sta=851.8,927.8
XS Rating Curve= 0 ,0
Exp/Cntr=0.3,0.1

Type RM Length L Ch R = 1 ,114294.5,696.1,694.5,692.9
XS GIS Cut Line= 3
     2365650.688      355182.464     2365793.917      354987.151
     2366757.285      353996.724
#Sta/Elev= 30
       0  540.87    47.6  534.27   310.1  514.66     374  505.82   469.8   486.5
   557.7  476.58   673.5  471.54   717.4  464.88   757.3   463.6   769.3   456.8
   773.3  456.26   845.2  456.51  846.48456.6732   865.2  460.87  909.87460.9712
  1076.8   463.2  1172.6  458.58  1216.6  462.35  1272.5  459.87  1300.4  462.74
  1344.4  459.59  1376.3  464.62 1387.98472.0259  1424.2  506.04  1468.1  538.34
  1480.1  551.01    1520  572.33    1536  578.09    1556  580.66  1623.9  576.78
#Mann= 6 ,-1 , 0
       0     .12       0   769.3    .045       0   845.2     .04       0
  846.48     .12       0  909.87     .08       0 1387.98     .12       0
Bank Sta=769.3,845.2
XS Rating Curve= 0 ,0
Exp/Cntr=0.3,0.1

Type RM Length L Ch R = 1 ,113600  ,568.6,563.7,558.7
XS GIS Cut Line= 2
     2366058.603      355765.698      2367239.23      354414.234
#Sta/Elev= 30
       0  530.84      56  519.71   127.9  509.22   179.8  504.63   199.8   499.9
  305.67493.6683  343.32490.7599   611.5  475.35   807.3  467.74  859.93460.6055
   871.3  455.95   875.3   455.7   939.2  456.52   947.2  462.85   967.2  467.07
 1001.75 466.717 1312.62463.2224  1334.9  461.16 1417.78463.0098  1486.8  464.61
  1554.7  458.74  1562.7  460.62 1571.41472.1236  1578.7   483.5  1598.7  501.27
  1638.7  528.49  1674.6  547.21  1718.6  557.75  1766.6  561.31  1794.5  559.96
#Mann= 10 ,-1 , 0
       0     .12       0  305.67     .06       0  343.32     .12       0
  859.93     .04       0   871.3    .045       0   939.2     .12       0
 1001.75     .06       0 1312.62     .12       0 1417.78     .08       0
 1571.41     .12       0
Bank Sta=871.3,939.2
XS Rating Curve= 0 ,0
Exp/Cntr=0.3,0.1

Type RM Length L Ch R = 1 ,113036.4,577.3,556.4,535.5
XS GIS Cut Line= 4
     2366655.999      356056.041     2366731.417      355981.075
     2367531.387      354775.379     2367512.667       354657.29
#Sta/Elev= 30
       0   498.3   106.3  491.06  445.73473.4229     598  469.48     622  466.93
   661.9   469.7   761.9  469.29   789.8  466.82  806.52461.0046  817.32455.5768
   817.8  455.38   881.8  455.56   885.8  456.76   893.8   462.2   921.7  465.93
  1265.5  461.24 1329.24462.3356  1345.4  461.67  1357.4  457.18  1393.4  458.93
  1413.4  462.27  1437.4  462.26  1445.4   465.2 1456.11476.2526  1465.4  486.45
  1501.3  508.96  1549.3  529.84  1609.1  544.55  1656.9  552.09  1672.8  552.95
#Mann= 7 ,-1 , 0
       0     .06       0  445.73     .12       0  806.52     .04       0
  817.32    .045       0   881.8     .12       0 1329.24     .08       0
 1456.11     .12       0
#XS Ineff= 2 , 0
       0     650                       0
Permanent Ineff=
       F       F
Bank Sta=817.32,881.8
XS Rating Curve= 0 ,0
Exp/Cntr=0.3,0.1

Type RM Length L Ch R = 1 ,112479.9,634.8,629.9,624.3
XS GIS Cut Line= 4
     2367742.702      356432.464     2367677.598       356219.79
     2367693.451      354943.676     2367687.249      354826.875
#Sta/Elev= 30
       0  496.93   158.9  496.54   298.2  481.53   493.6   469.1   509.6  470.75
   629.2  466.73   732.9  467.27   848.6  463.47   928.3   465.8   932.3  464.67
   940.3   456.5   944.3  455.52    1020  455.47 1022.92455.7766    1048  459.12
  1083.9  460.72  1171.6  458.54  1195.5  463.75 1215.02463.7216  1271.3  463.15
    1379  454.68    1391  455.89  1402.9  460.14  1414.9  469.73  1434.8  492.08
 1441.55497.2088  1462.7  507.98  1514.2  522.45  1549.3  528.13  1615.6   533.1
#Mann= 6 ,-1 , 0
       0     .12       0   944.3    .045       0    1020     .04       0
 1022.92     .12       0 1215.02     .08       0 1441.55     .12       0
#XS Ineff= 2 , 0
       0     500                       0
Permanent Ineff=
       F       F
Bank Sta=944.3,1020
XS Rating Curve= 0 ,0
Exp/Cntr=0.3,0.1

Type RM Length L Ch R = 1 ,111850.1,333.4,322.8,312.1
XS GIS Cut Line= 3
     2368424.125      356211.109     2368211.452      355195.484
     2367801.832       354873.75
#Sta/Elev= 30
       0  588.74   115.7  578.78   175.6  566.79   219.5  552.59   279.4     527
   323.3  507.25  395.34470.4118   411.1   468.9  426.03463.8497   486.9  461.55
   514.8  461.76   534.8   464.3   694.4  464.57   722.4  461.54   746.3  464.78
   802.2   464.2  813.33462.2006   822.1  459.35   830.1  453.55   834.1  452.91
   925.9  453.44  926.68 453.596   969.8  476.92   993.8  485.74  1053.6  494.43
  1137.1  500.73    1320  504.08  1359.7  508.26  1435.3  520.23  1558.5   526.5
#Mann= 7 ,-1 , 0
       0     .12       0  395.34    .016       0  426.03     .12       0
  813.33     .04       0   830.1    .045       0   925.9     .04       0
  926.68     .12       0
Bank Sta=830.1,925.9
XS Rating Curve= 0 ,0
Exp/Cntr=0.3,0.1

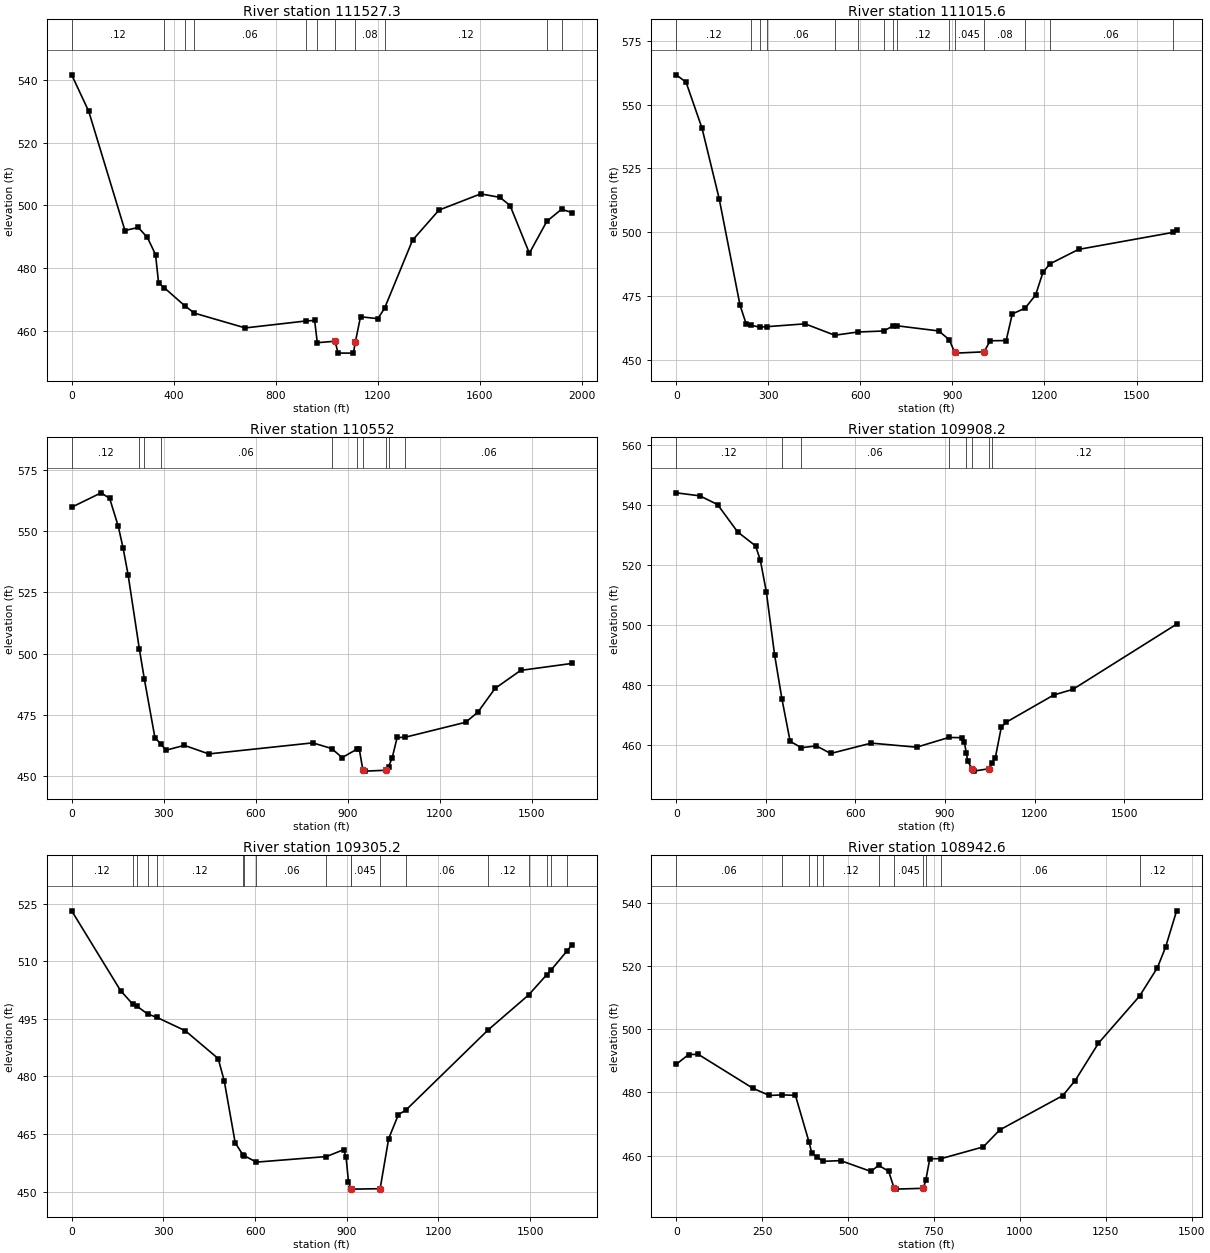
Type RM Length L Ch R = 1 ,111527.3,505.5,511.6,517.3
XS GIS Cut Line= 4
     2369079.507      356007.116     2368871.174      356020.137
     2368419.785       354969.79     2368046.624      354488.333
#Sta/Elev= 30
       0  541.57      67   529.9   208.7  491.97   260.7  492.95   296.7  489.76
   328.7   484.3   340.6  475.26  362.18473.7921   442.8468.0195  481.25465.6414
   680.4  460.94  917.85463.1468   952.2  463.33  962.65456.2311  1032.2   456.7
  1044.1  452.93  1104.1  452.91  1112.1  456.58  1132.1   464.5  1200.1  463.88
  1226.4467.2248    1336   488.9  1439.6  498.48  1602.8  503.64  1678.4  502.54
  1718.2  499.94  1793.9  484.74 1862.28494.9046 1919.84498.7336  1961.1  497.68
#Mann= 11 ,-1 , 0
       0     .12       0  362.18     .06       0   442.8    .016       0
  481.25     .06       0  917.85     .12       0  962.65     .04       0
  1032.2    .045       0  1112.1     .08       0  1226.4     .12       0
 1862.28     .06       0 1919.84     .12       0
Bank Sta=1032.2,1112.1
XS Rating Curve= 0 ,0
Exp/Cntr=0.3,0.1

Type RM Length L Ch R = 1 ,111015.6,461.3,463.6,466.4
XS GIS Cut Line= 2
     2369255.956      356002.179     2368849.473      354422.915
#Sta/Elev= 30
       0  561.66      32  558.75    83.9  540.74   139.9  513.07   207.8  471.29
   227.8  463.99  243.35463.4523  271.49462.6884  295.81462.8799   419.7  463.99
   516.6  459.52  591.53  460.78  675.61461.1799  706.24463.1403  719.01463.2322
   855.3   461.2  889.89457.7501   907.3  452.78   911.3   452.5  1003.2  453.01
  1023.2  457.35  1075.2  457.43  1095.2  467.89 1136.86470.1148  1171.1   475.3
  1195.1  484.16 1217.32487.4731    1311  493.18 1617.74499.8315  1630.7  500.72
#Mann= 15 ,-1 , 0
       0     .12       0  243.35     .06       0  271.49    .016       0
  295.81     .06       0   516.6     .08       0  591.53     .06       0
  675.61     .12       0  706.24     .06       0  719.01     .12       0
  889.89     .04       0   907.3    .045       0  1003.2     .08       0
 1136.86     .12       0 1217.32     .06       0 1617.74     .12       0
Bank Sta=907.3,1003.2
XS Rating Curve= 0 ,0
Exp/Cntr=0.3,0.1

Type RM Length L Ch R = 1 ,110552  ,640.7,643.8,647
XS GIS Cut Line= 3
     2369609.021      355972.394     2369626.382      355833.505
     2369352.945      354366.491
#Sta/Elev= 30
       0  559.65      96  565.52     124  563.21   151.9   551.9   167.9   542.9
   183.9  532.22  220.59501.9763  236.99489.6428   271.6  465.69  291.27463.1027
   307.6  460.61   367.4   462.6   447.2   459.1   786.4  463.61  847.96461.3044
   882.1  457.61  931.42461.0927     938  461.19     950  452.45   957.9  452.09
  1025.8  452.45 1033.94453.8964  1045.7  457.61  1061.7   465.8 1086.67465.8655
  1285.1     472    1325  476.11  1380.9  485.78  1464.7  493.15  1632.2  495.99
#Mann= 10 ,-1 , 0
       0     .12       0  220.59    .016       0  236.99     .12       0
  291.27     .06       0  847.96     .08       0  931.42     .04       0
     950    .045       0  1025.8     .04       0 1033.94     .12       0
 1086.67     .06       0
Bank Sta=950,1025.8
XS Rating Curve= 0 ,0
Exp/Cntr=0.3,0.1

Type RM Length L Ch R = 1 ,109908.2,587.4,602.9,618.5
XS GIS Cut Line= 3
     2370030.028      355820.484     2370177.598      355677.255
     2370030.028      354214.582
#Sta/Elev= 30
       0  544.12    79.1  543.11   138.4  540.21   205.6  531.08   265.6  526.43
   281.6  521.64   301.5  511.22   329.5     490  354.13475.2827   381.4  461.27
  419.21459.1262   469.3  459.75   517.2  457.21   653.1  460.67   804.9  459.31
  913.12462.5605   956.7  462.48   964.7  461.11  971.37457.4112   976.6   454.6
  991.05451.9946   996.6  451.33  1048.6  452.15  1056.7454.1454  1068.5  455.71
  1088.5  465.91  1104.5   467.6  1264.3  476.72  1328.2  478.58  1675.8  500.33
#Mann= 8 ,-1 , 0
       0     .12       0  354.13    .016       0  419.21     .06       0
  913.12     .12       0  971.37     .04       0  991.05    .045       0
  1048.6     .04       0  1056.7     .12       0
Bank Sta=991.05,1048.6
XS Rating Curve= 0 ,0
Exp/Cntr=0.3,0.1

Type RM Length L Ch R = 1 ,109305.2,369.3,362.6,356
XS GIS Cut Line= 4
     2370221.082      355773.704     2370503.119      355490.623
     2370754.855      354709.373     2370754.855      354292.707
#Sta/Elev= 30
       0  523.13   159.8  502.37  199.92498.8134  213.65  498.28  248.35496.2845
  279.46495.3544   371.6  491.91   479.3  484.66   499.2  478.82   535.1  462.69
   560.5 459.555  565.38459.3383  604.08457.6888  833.72459.1423   889.7  460.93
   897.7  459.02   905.6  452.64  912.55450.7666  912.84450.7427   917.6  450.66
  1009.2  450.77  1037.1  463.79    1069  470.07 1093.18471.2161 1362.17492.0896
 1494.67501.1964 1553.82506.4496 1568.41507.6948 1620.35512.6565  1637.1   514.3
#Mann= 18 ,-1 , 0
       0     .12       0  199.92     .06       0  213.65     .12       0
  248.35     .06       0  279.46     .12       0   560.5     .06       0
  565.38    .016       0  604.08     .06       0  833.72     .12       0
  912.55     .04       0  912.84    .045       0  1009.2     .12       0
 1093.18     .06       0 1362.17     .12       0 1494.67     .06       0
 1553.82     .12       0 1568.41     .06       0 1620.35     .12       0
Bank Sta=912.84,1009.2
XS Rating Curve= 0 ,0
Exp/Cntr=0.3,0.1

Type RM Length L Ch R = 1 ,108942.6,510.5,528.6,546.6
XS GIS Cut Line= 3
     2370776.556      355720.658     2370924.125       355599.13
     2371119.438       354349.13
#Sta/Elev= 30
       0  488.89    35.8  491.96    63.7  492.06   223.1   481.3     271  479.02
  308.18479.2056   346.8  479.06  386.58464.2394   394.7   460.7   410.2459.6088
  426.41  458.18   478.5  458.41   566.3     455  589.25456.9065   618.2  455.04
   634.2  449.62   638.2  449.39  718.97449.6494  726.12452.1423   737.9     459
  770.43459.0266   893.6  462.75   941.5  468.12  1125.1  478.99    1161  483.74
  1228.8  495.56 1348.37510.4538  1400.5  519.46  1424.4  526.02  1456.3  537.44
#Mann= 11 ,-1 , 0
       0     .06       0  308.18     .12       0  386.58    .016       0
   410.2     .06       0  426.41     .12       0  589.25     .04       0
   634.2    .045       0  718.97     .04       0  726.12     .12       0
  770.43     .06       0 1348.37     .12       0
Bank Sta=634.2,718.97
XS Rating Curve= 0 ,0
Exp/Cntr=0.3,0.1