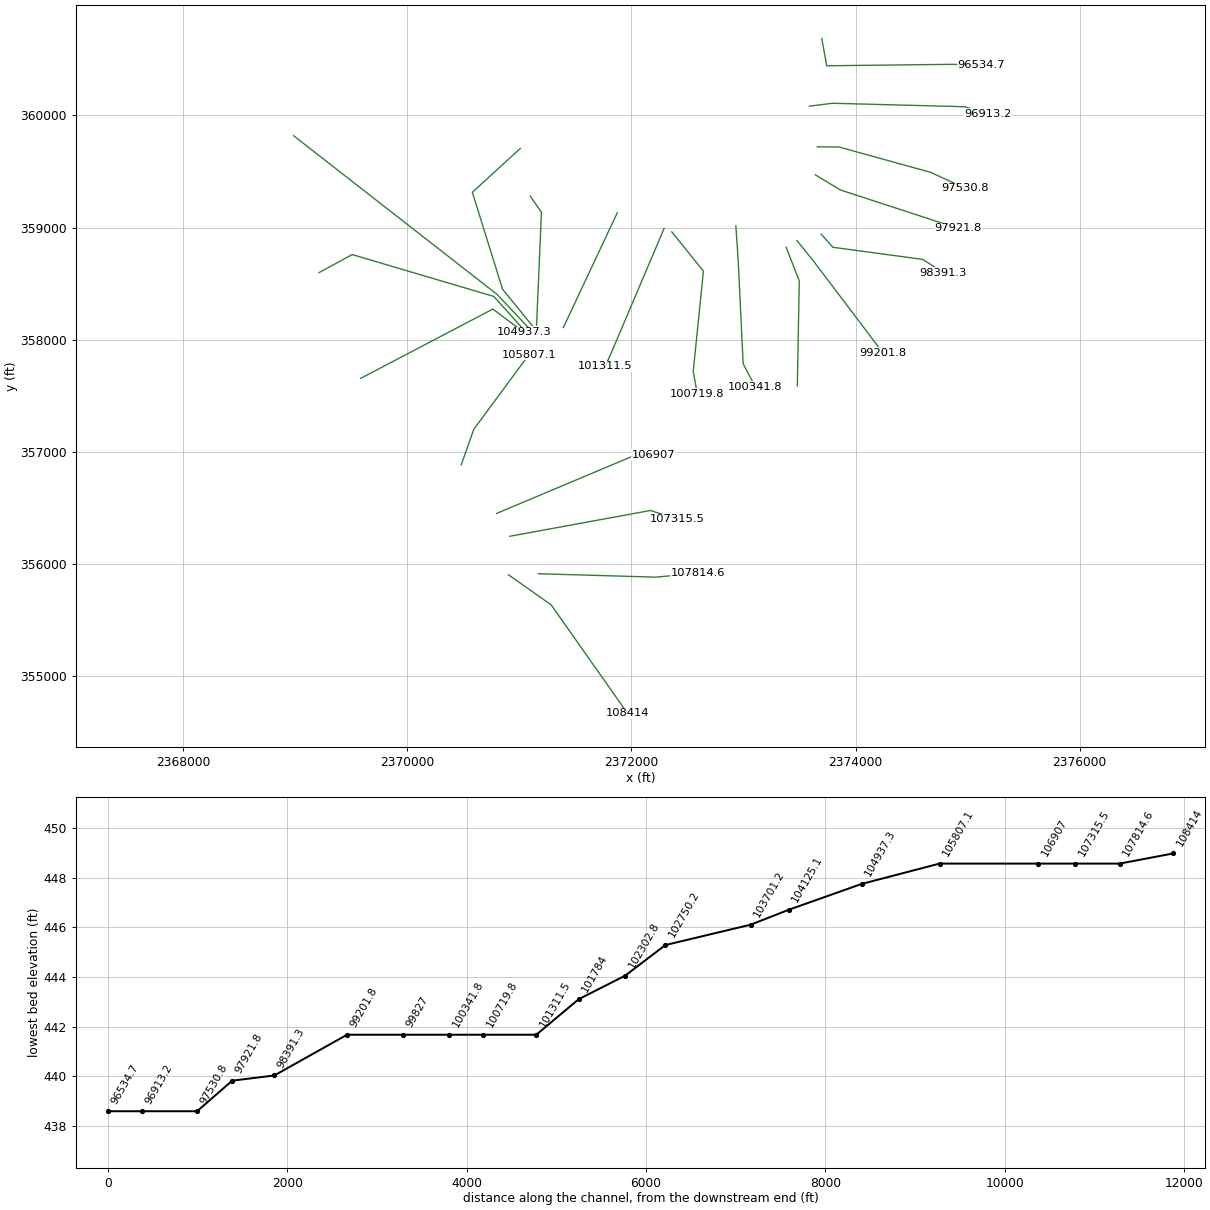
HEC-RAS study BACKCREEK.prj: BACKCREEK

--- BACKCREEK.g01 (geometry) --- (continued)

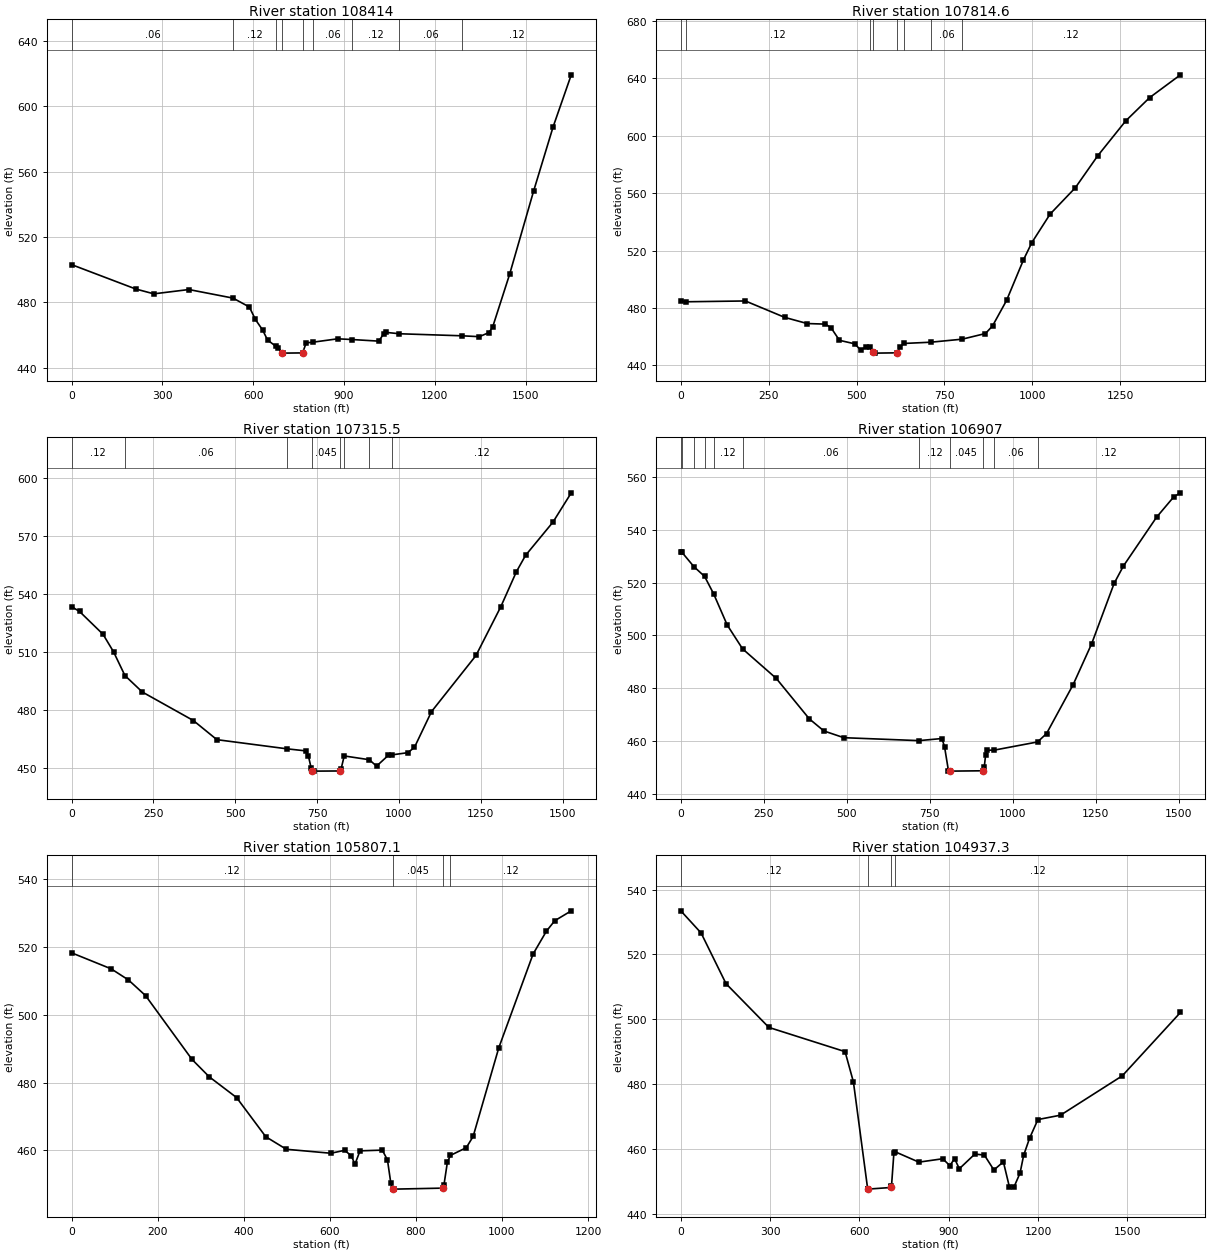
Type RM Length L Ch R = 1 ,108414  ,564.4,599.4,634.4
XS GIS Cut Line= 3
     2370902.424       355902.95     2371284.369      355633.853
     2371965.792      354665.971
#Sta/Elev= 30
       0  503.06   211.6  488.19   271.6  485.22   387.4  487.85  533.24482.6121
   587.2  477.18   607.2  469.54   631.2  463.07   647.2  457.03  675.28453.0662
   683.2  452.41   694.1 449.231   699.2  448.98   763.1  449.12   775.1  455.26
   797.1 455.665   879.1  457.73  925.83457.2973  1015.1  456.31  1031.1  460.84
  1039.1  461.66 1083.29460.8191 1288.65459.5818    1347  459.04    1379  461.54
    1391  464.86    1447  497.05    1527  548.37  1590.9  587.28  1650.9   619.1
#Mann= 9 ,-1 , 0
       0     .06       0  533.24     .12       0  675.28     .04       0
   694.1    .045       0   763.1     .12       0   797.1     .06       0
  925.83     .12       0 1083.29     .06       0 1288.65     .12       0
Bank Sta=694.1,763.1
XS Rating Curve= 0 ,0
Exp/Cntr=0.3,0.1

Type RM Length L Ch R = 1 ,107814.6,491.2,499.1,507
XS GIS Cut Line= 3
     2371171.521       355911.63     2372217.528      355881.248
     2372590.792      355915.971
#Sta/Elev= 30
       0   484.8   14.91484.3454   183.7  484.91   295.6  473.47   359.5  469.18
   411.4  468.78   427.4  466.23   451.3  457.49   495.3  455.02   511.2  450.72
   527.2  452.99   538.2 452.655   547.2  449.17   551.2  448.57   615.1  448.77
   623.1  452.87   634.8455.3105  710.71456.1702  800.49458.2936   866.7  462.24
   886.7  467.51   926.6  485.26   974.6  513.47   998.5  525.54  1050.4  545.38
  1122.2  563.77    1186  586.05  1265.8  610.41  1333.6  626.57  1421.3  642.46
#Mann= 8 ,-1 , 0
       0     .06       0   14.91     .12       0   538.2     .04       0
   547.2    .045       0   615.1     .04       0   634.8     .12       0
  710.71     .06       0  800.49     .12       0
Bank Sta=547.2,615.1
XS Rating Curve= 0 ,0
Exp/Cntr=0.3,0.1

Type RM Length L Ch R = 1 ,107315.5,400.4,408.6,416.8
XS GIS Cut Line= 3
     2370915.445      356245.832     2372169.785      356475.866
       2372408.5      356397.741
#Sta/Elev= 30
       0  533.45      24     531    95.9   519.2   127.9  510.19   162.8 497.901
   215.9  489.41   371.8  474.69   443.7  464.81  658.17460.0764   715.6  459.02
   723.6  456.16   731.6  450.27   735.6  448.84   739.6  448.57  819.58448.6556
   823.5  449.91   832.8456.4095  909.49454.4566   931.5  451.14   967.4  456.71
  978.09456.9469  1027.4  458.11  1047.4  460.87  1099.4  479.29  1235.3  508.26
  1311.1  533.42    1359  551.58  1386.9  559.98  1470.6  577.13  1526.4  592.23
#Mann= 8 ,-1 , 0
       0     .12       0   162.8     .06       0  658.17     .12       0
   735.6    .045       0  819.58     .04       0   832.8     .12       0
  909.49     .08       0  978.09     .12       0
Bank Sta=735.6,819.58
XS Rating Curve= 0 ,0
Exp/Cntr=0.3,0.1

Type RM Length L Ch R = 1 ,106907  ,1079.7,1099.8,1120
XS GIS Cut Line= 3
     2370798.257      356449.825     2372004.855      356957.637
     2372200.167      356970.658
#Sta/Elev= 30
       0  531.71     3.6 531.458   39.35526.0464    71.6522.3495   99.04 515.699
   139.7  503.94  185.98494.9025   287.4  483.71   387.1  468.36     431  463.79
   490.9  461.24  717.32460.1273   786.3  460.92   794.2   457.9   806.2  448.63
   810.2  448.57     910   448.7     914  450.21     918  454.68     922  456.52
   942.4  456.49 1074.66459.6316  1101.6  462.82  1181.4  481.28  1237.3   496.8
  1305.1  519.71  1333.1   526.3  1432.9  544.78  1484.9  552.52  1504.8  554.02
#Mann= 11 ,-1 , 0
       0     .12       0     3.6     .06       0   39.35     .12       0
    71.6     .06       0   99.04     .12       0  185.98     .06       0
  717.32     .12       0   810.2    .045       0     910     .04       0
   942.4     .06       0 1074.66     .12       0
Bank Sta=810.2,910
XS Rating Curve= 0 ,0
Exp/Cntr=0.3,0.1

Type RM Length L Ch R = 1 ,105807.1,887.9,869.8,851.4
XS GIS Cut Line= 4
     2370482.369      356884.237     2370594.264      357200.693
     2371036.973      357799.651     2371084.716      357864.755
#Sta/Elev= 30
       0  518.24    91.9  513.52   131.9  510.26   171.8  505.63   279.7  486.82
   319.7   481.7   383.4  475.56   451.2  464.02     499  460.32   602.5  459.15
   634.4  460.01   650.3  458.38   658.3  455.86   670.2  459.86     722  460.07
     734  457.19   741.9  450.27   745.9  448.74   749.9  448.57  862.26448.8652
   865.4  449.87   873.4   456.6  880.48458.5214   917.2  460.79   933.1  464.09
   992.8  490.26  1072.5   517.9  1103.5  524.64  1122.8  527.71  1161.2  530.63
#Mann= 4 ,-1 , 0
       0     .12       0   745.9    .045       0  862.26     .04       0
  880.48     .12       0
Bank Sta=745.9,862.26
XS Rating Curve= 0 ,0
Exp/Cntr=0.3,0.1

Type RM Length L Ch R = 1 ,104937.3,842.6,812.3,782
XS GIS Cut Line= 3
     2369585.149      357654.584     2370764.255      358272.726
     2371041.698      358064.625
#Sta/Elev= 30
       0  533.44      68  526.63   151.9     511   295.8  497.54   551.7  490.08
   579.7  480.76  627.59447.8132   627.7  447.75  705.83 448.255   707.6  448.64
   715.6   458.8  719.02459.2874   799.6  456.06   879.6   457.1   903.5     455
   919.5  457.12   935.5  454.03   987.5  458.54  1019.5  458.24  1051.5  453.65
  1083.4  456.15  1103.4  448.52  1119.4  448.49  1139.4  452.69  1151.4  458.14
  1171.4  463.43  1199.4  469.17  1275.3  470.52  1482.8  482.64  1678.1  502.14
#Mann= 4 ,-1 , 0
       0     .12       0  627.59    .045       0  705.83     .04       0
  719.02     .12       0
Bank Sta=627.59,705.83
XS Rating Curve= 0 ,0
Exp/Cntr=0.3,0.1

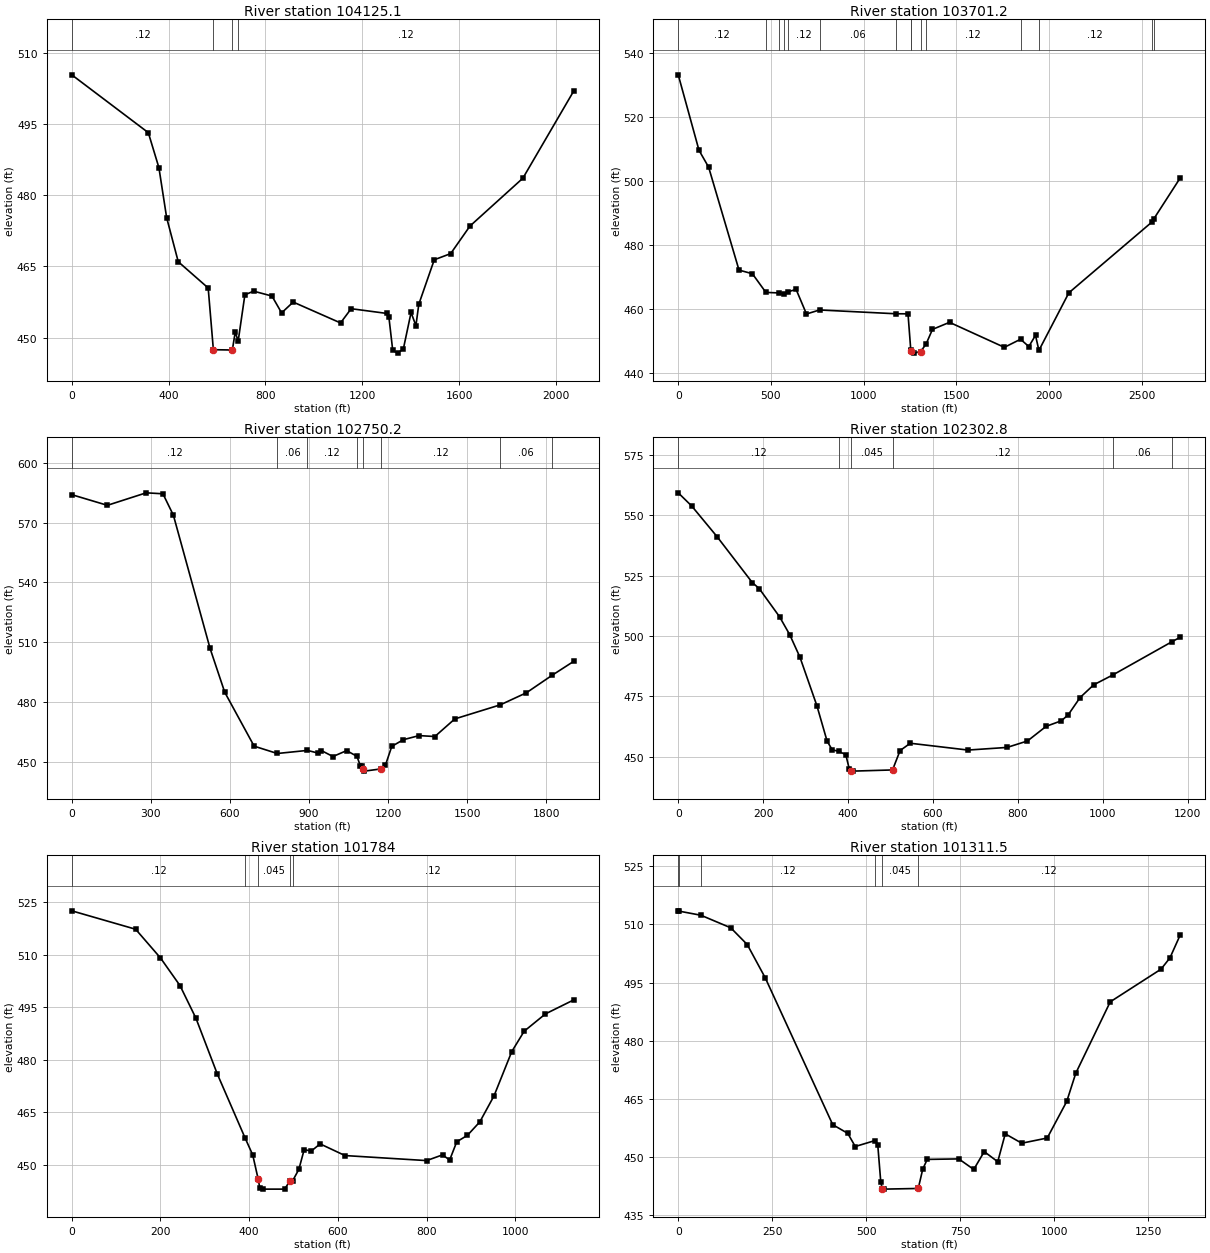
Type RM Length L Ch R = 1 ,104125.1,435.8,423.8,411.8
XS GIS Cut Line= 4
     2369214.056      358598.262     2369509.195      358758.853
     2370772.216      358385.589     2371054.334      358073.089
#Sta/Elev= 30
       0  505.41   316.2  493.21     360  485.82   391.9  475.29   439.8  465.99
   563.5  460.45  584.92447.4322   663.3  447.37   675.2  451.15   687.4449.2515
   715.1  459.01   751.1  459.78   826.9  458.75   866.8   455.2   914.7  457.48
  1110.2  453.08  1154.2  456.08  1301.8  455.08  1309.8  454.39  1325.8  447.31
  1345.7  446.71  1369.7  447.59  1401.6  455.28  1421.6   452.5  1433.5  457.01
  1497.4   466.4  1565.2   467.7    1645  473.52  1863.5  483.61    2074  502.04
#Mann= 4 ,-1 , 0
       0     .12       0  584.92    .045       0   663.3     .04       0
   687.4     .12       0
Bank Sta=584.92,663.3
XS Rating Curve= 0 ,0
Exp/Cntr=0.3,0.1

Type RM Length L Ch R = 1 ,103701.2,975.1,951,926.9
XS GIS Cut Line= 3
     2368986.858       359818.86     2370802.598       358402.95
     2371080.375      358107.811
#Sta/Elev= 30
       0  533.13   111.9  509.54   163.9  504.26   327.8  472.07   399.8  470.94
  472.69465.1003  543.95464.9274  572.06  464.55     593465.2858   635.6  466.05
   691.6  458.35  762.19 459.606 1172.36458.4209  1239.2   458.4 1254.28446.9661
  1255.2  446.72  1271.2  446.11  1307.2  446.61 1336.37448.9063  1371.1  453.53
  1463.1  455.74  1758.9  447.92 1846.05  450.45  1890.8  448.17  1926.8  451.67
  1945.2 446.964  2106.7  464.97 2553.52487.0399 2565.56488.1508  2707.8  500.94
#Mann= 15 ,-1 , 0
       0     .12       0  472.69     .04       0  543.95     .08       0
  572.06     .04       0     593     .12       0  762.19     .06       0
 1172.36     .12       0 1254.28     .04       0  1255.2    .045       0
  1307.2     .04       0 1336.37     .12       0 1846.05     .04       0
  1945.2     .12       0 2553.52     .06       0 2565.56     .12       0
#XS Ineff= 2 , 0
       0     800                       0
Permanent Ineff=
       F       F
Bank Sta=1255.2,1307.2
XS Rating Curve= 0 ,0
Exp/Cntr=0.3,0.1

Type RM Length L Ch R = 1 ,102750.2,460.4,447.4,434.5
XS GIS Cut Line= 4
     2371009.428      359706.013     2370581.244      359314.408
     2370850.341      358450.693     2371115.098      358125.172
#Sta/Elev= 30
       0  584.05   135.1  578.71   282.2  584.98   345.8   584.5   385.5  573.72
   524.6  506.88   580.2  484.89   691.8  457.82  779.52  454.14  893.99455.6905
     935  454.32   946.9  455.61   990.7  452.62  1042.6  455.58 1081.59452.7482
  1094.4  448.08  1102.3     448  1106.3  446.22  1110.3  445.29  1174.1  446.43
    1190  448.36  1213.9  457.73  1257.8  461.07  1317.5  463.12  1377.3  462.66
    1453   471.5 1625.76478.5728  1724.7  484.63 1821.61493.3596  1904.5  500.44
#Mann= 8 ,-1 , 0
       0     .12       0  779.52     .06       0  893.99     .12       0
 1081.59     .04       0  1106.3    .045       0  1174.1     .12       0
 1625.76     .06       0 1821.61     .12       0
Bank Sta=1106.3,1174.1
XS Rating Curve= 0 ,0
Exp/Cntr=0.3,0.1

Type RM Length L Ch R = 1 ,102302.8,533.7,518.8,503.8
XS GIS Cut Line= 3
     2371097.737      359279.686     2371197.563      359136.457
      2371154.16      358129.512
#Sta/Elev= 30
       0  559.25    31.7   553.8    91.3  541.14   174.6  522.07   190.6  519.65
   238.6  507.96   262.6  500.53   286.6  491.24   326.6  471.12   350.6  456.47
   362.6  452.91  378.07452.2281   394.6  450.89   402.6  445.14  405.92444.2685
   410.6  444.06  504.74444.5508   522.5  452.57   546.5   455.6   682.5  452.78
   774.5  453.87   822.5  456.54   866.5   462.6   902.5  464.91   918.5  467.38
   946.5  474.53   978.5  479.78 1023.97483.9082 1163.16497.6575  1182.5  499.49
#Mann= 6 ,-1 , 0
       0     .12       0  378.07     .04       0  405.92    .045       0
  504.74     .12       0 1023.97     .06       0 1163.16     .12       0
Bank Sta=405.92,504.74
XS Rating Curve= 0 ,0
Exp/Cntr=0.3,0.1

Type RM Length L Ch R = 1 ,101784  ,470.4,472.5,474.7
XS GIS Cut Line= 2
     2371874.646      359132.116     2371392.875      358107.811
#Sta/Elev= 30
       0  522.61     144  517.35     200  509.15     244  501.26     280  491.92
     328  476.04  390.83 457.703     408  452.88     420  446.12     424  443.44
     432  443.11     480  443.11     492  445.51  497.79 445.441     512  448.76
     524   454.4     540  453.99     560  456.03     616   452.7     800  451.26
     836   452.9     852  451.42     868  456.64     892  458.47     920  462.32
     952  469.75     992  482.39    1020  488.22    1068  493.17    1132  497.18
#Mann= 5 ,-1 , 0
       0     .12       0  390.83     .04       0     420    .045       0
     492     .04       0  497.79     .12       0
Bank Sta=420,492
XS Rating Curve= 0 ,0
Exp/Cntr=0.3,0.1

Type RM Length L Ch R = 1 ,101311.5,581.1,591.7,602.4
XS GIS Cut Line= 3
     2372292.181      358992.359      2371814.75      357868.228
     2371767.007      357764.061
#Sta/Elev= 30
       0   513.5    3.36513.3992   60.34512.3599   139.7  509.12   183.6   504.8
   231.5  496.21   411.1  458.31     451  456.08     471  452.68  523.65454.2151
   530.8  453.19   538.8  443.64  542.76441.7392   546.8  441.68   638.6  441.85
   650.6  446.85   662.5  449.35   746.4  449.48   786.3  446.76   814.2  451.36
   850.1  448.75   870.1  455.95     914  453.53   981.8  454.87  1033.7  464.31
  1057.7  471.58  1149.5  490.02  1284.5  498.44  1308.2  501.34  1335.9  507.33
#Mann= 6 ,-1 , 0
       0     .12       0    3.36     .06       0   60.34     .12       0
  523.65     .04       0  542.76    .045       0   638.6     .12       0
Bank Sta=542.76,638.6
XS Rating Curve= 0 ,0
Exp/Cntr=0.3,0.1

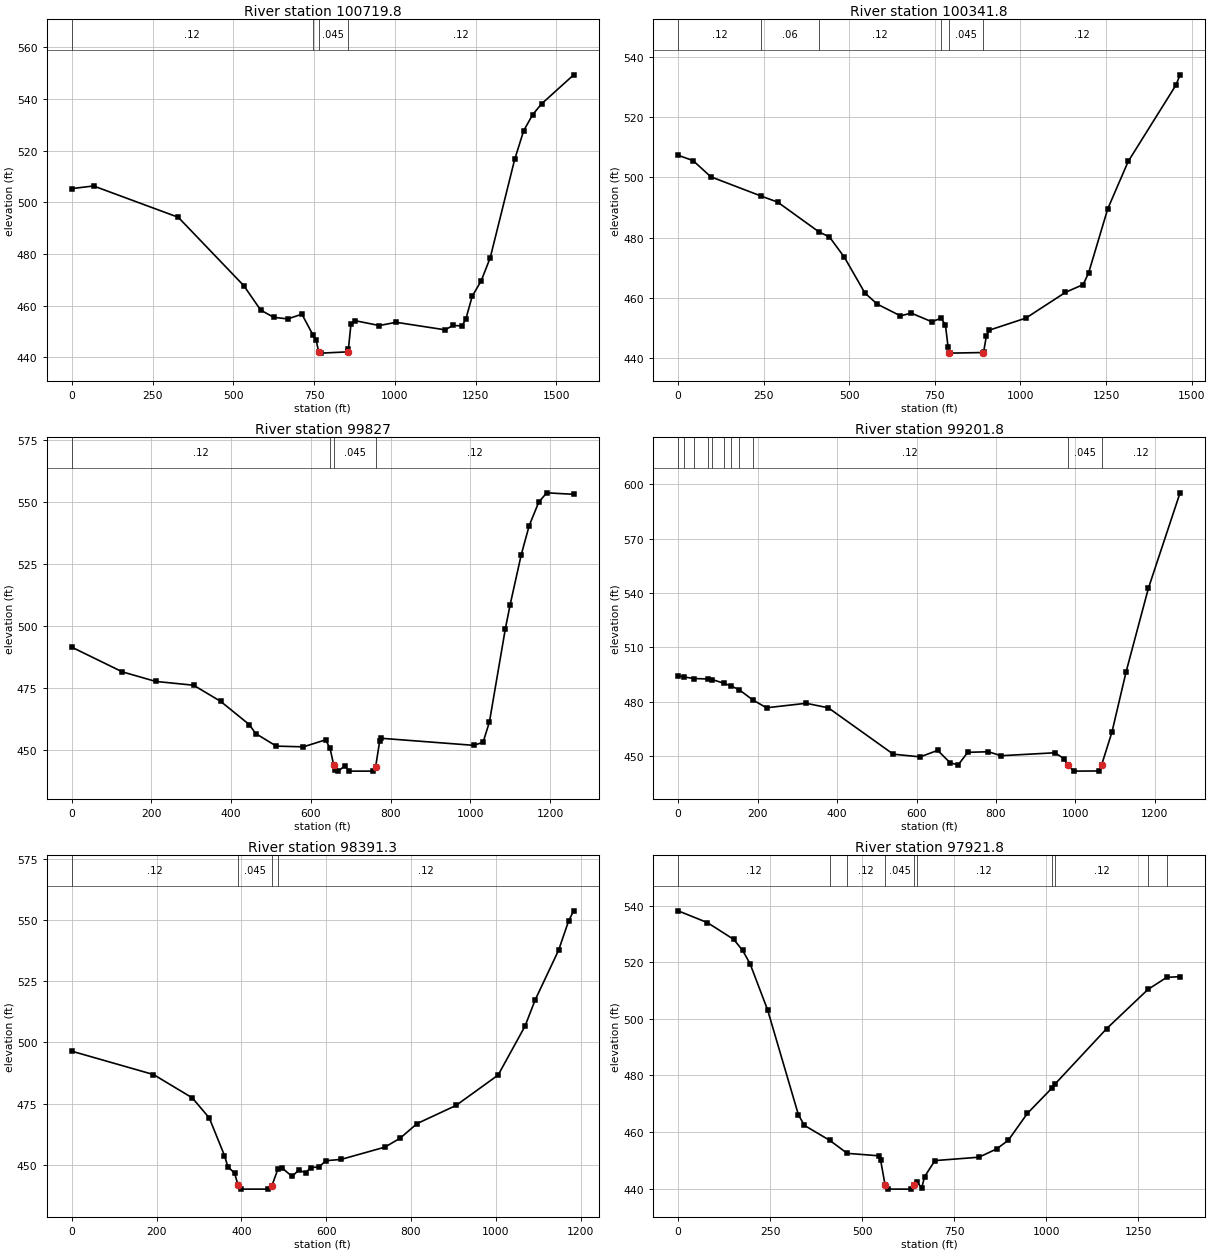
Type RM Length L Ch R = 1 ,100719.8,372.2,378,383.7
XS GIS Cut Line= 4
      2372360.86      358960.555     2372642.875      358611.283
     2372551.832        357717.5     2372588.291      357514.375
#Sta/Elev= 30
       0   505.3    67.5  506.32   329.7  494.21   532.8  467.72   584.7  458.33
   624.6  455.55   668.5   454.9   712.4  456.74  746.19448.7799   756.4  446.67
   764.4  442.13   772.3  441.68  853.55 442.166   856.2  443.12   864.2  452.91
   876.2  454.25     952  452.35  1003.9   453.6  1155.7  450.69  1179.6  452.38
  1207.6   452.2  1219.6  454.79  1239.5  463.68  1267.5  469.69  1295.4  478.63
  1371.1  516.67  1398.9  527.72  1426.7  533.92  1454.5  538.11  1553.7   549.3
#Mann= 4 ,-1 , 0
       0     .12       0  746.19     .04       0   764.4    .045       0
  853.55     .12       0
Bank Sta=764.4,853.55
XS Rating Curve= 0 ,0
Exp/Cntr=0.3,0.1

Type RM Length L Ch R = 1 ,100341.8,517.4,514.8,512.2
XS GIS Cut Line= 4
     2372932.041      359014.375     2372952.874      358712.291
     2372997.145      357785.208      2373106.52      357576.875
#Sta/Elev= 30
       0  507.27    43.8  505.49    95.6  500.13   242.5493.7437   290.8  491.74
  411.34 481.876   442.2  480.18     486   473.4   545.8  461.58   581.6  457.94
   649.4  454.03   681.2  454.94     741  452.08  767.89453.2492   780.8  451.03
   788.8  443.57  792.58441.7839   792.8  441.68  890.21441.8791   892.4  442.12
   900.3  447.21   908.3  449.27  1015.8  453.29  1131.4  461.82  1183.1   464.4
  1199.1  468.27  1254.9  489.49  1314.7  505.22  1454.3  530.55  1466.2  533.93
#Mann= 6 ,-1 , 0
       0     .12       0   242.5     .06       0  411.34     .12       0
  767.89     .04       0  792.58    .045       0  890.21     .12       0
Bank Sta=792.58,890.21
XS Rating Curve= 0 ,0
Exp/Cntr=0.3,0.1

Type RM Length L Ch R = 1 ,99827   ,599.9,625.2,650.6
XS GIS Cut Line= 3
     2373380.723      358823.957      2373497.91      358524.478
     2373480.549      357586.978
#Sta/Elev= 30
       0  491.65     127  481.69   210.4  477.85   305.7  476.31   373.5   469.8
   445.3  460.44   461.2  456.85   513.1  451.76   580.9  451.47   636.8  454.29
  647.93450.8633   656.8  444.33   660.7  442.29   668.7  441.68   684.7  443.76
   696.7  441.68   756.5  441.68  762.05443.1845   772.5  453.84   776.5  454.92
  1007.9  452.08  1031.8  453.28  1047.8  461.57  1087.7  499.08  1099.6   508.7
  1127.6  528.96  1147.5  540.65  1171.5  550.13  1191.4  553.88  1259.2  553.28
#Mann= 4 ,-1 , 0
       0     .12       0  647.93     .04       0   656.8    .045       0
  762.05     .12       0
Bank Sta=656.8,762.05
XS Rating Curve= 0 ,0
Exp/Cntr=0.3,0.1

Type RM Length L Ch R = 1 ,99201.8 ,780.2,810.5,840.8
XS GIS Cut Line= 3
     2373476.209      358884.721     2373623.778      358702.429
     2374244.438      357882.116
#Sta/Elev= 30
       0  494.32    14.3  493.68   39.97492.7843   75.88492.5267   85.94492.1999
  114.37490.2407  131.91488.7866  152.87 486.723  187.92480.9672   222.6  476.64
   322.2  479.12   378.1  476.61   541.5  451.03   609.3  449.54   653.2  453.14
   685.1  446.17     705  445.16   728.9  452.06   780.8  452.37   812.7  450.19
   948.2   451.8   972.1  448.42   980.1  445.06   996.1  441.68  1059.8  441.77
 1065.93445.1908  1091.8  463.22  1127.6  496.64  1183.4  542.51  1263.2  595.26
#Mann= 11 ,-1 , 0
       0     .12       0    14.3     .06       0   39.97     .12       0
   75.88     .06       0   85.94    .016       0  114.37     .06       0
  131.91    .016       0  152.87     .06       0  187.92     .12       0
   980.1    .045       0 1065.93     .12       0
Bank Sta=980.1,1065.93
XS Rating Curve= 0 ,0
Exp/Cntr=0.3,0.1

Type RM Length L Ch R = 1 ,98391.3 ,476.1,469.5,462.9
XS GIS Cut Line= 4
     2373693.223      358941.144     2373797.389      358823.957
     2374599.218      358715.803     2374782.632      358598.262
#Sta/Elev= 30
       0  496.39   192.7  486.85   284.3  477.31   324.2  469.14   360.1  453.77
     368  449.23     384  446.53     392  441.75   399.9  440.04   463.7  440.04
   471.7  441.32  485.95448.1514   495.6  448.72   519.5  445.24   535.4  447.82
   551.4  446.69   563.3  448.83   583.3  449.11   599.2  451.65   635.1  452.18
   738.7  457.21   774.6  460.88   814.4  466.82   906.1  474.22  1005.5  486.65
  1068.9  506.64  1092.6  517.26  1148.1  537.66  1171.8  549.68  1183.7  553.73
#Mann= 4 ,-1 , 0
       0     .12       0     392    .045       0   471.7     .04       0
  485.95     .12       0
Bank Sta=392,471.7
XS Rating Curve= 0 ,0
Exp/Cntr=0.3,0.1

Type RM Length L Ch R = 1 ,97921.8 ,389.5,391.1,392.7
XS GIS Cut Line= 3
     2373641.139      359470.658     2373862.494      359336.109
     2374912.841      358993.228
#Sta/Elev= 30
       0  538.18    79.7  534.01   151.4  528.06   175.4  524.17   195.3  519.56
   243.1  503.21   326.8  466.15   342.8  462.39  412.46457.0266   459.5452.4775
   546.2   451.6   550.2  450.11   562.2  441.44   570.2  439.83     634  439.83
     642  441.27  648.84442.3792   661.9  440.29   669.9  444.26   697.8  449.91
   817.5  451.11   865.3  454.03   897.2  457.09   949.1   466.6 1015.27 475.467
 1023.94476.9312  1164.5  496.55 1276.78510.4009 1327.65514.6642  1363.9  514.92
#Mann= 10 ,-1 , 0
       0     .12       0  412.46     .06       0   459.5     .12       0
   562.2    .045       0     642     .04       0  648.84     .12       0
 1015.27     .06       0 1023.94     .12       0 1276.78     .06       0
 1327.65     .12       0
Bank Sta=562.2,642
XS Rating Curve= 0 ,0
Exp/Cntr=0.3,0.1

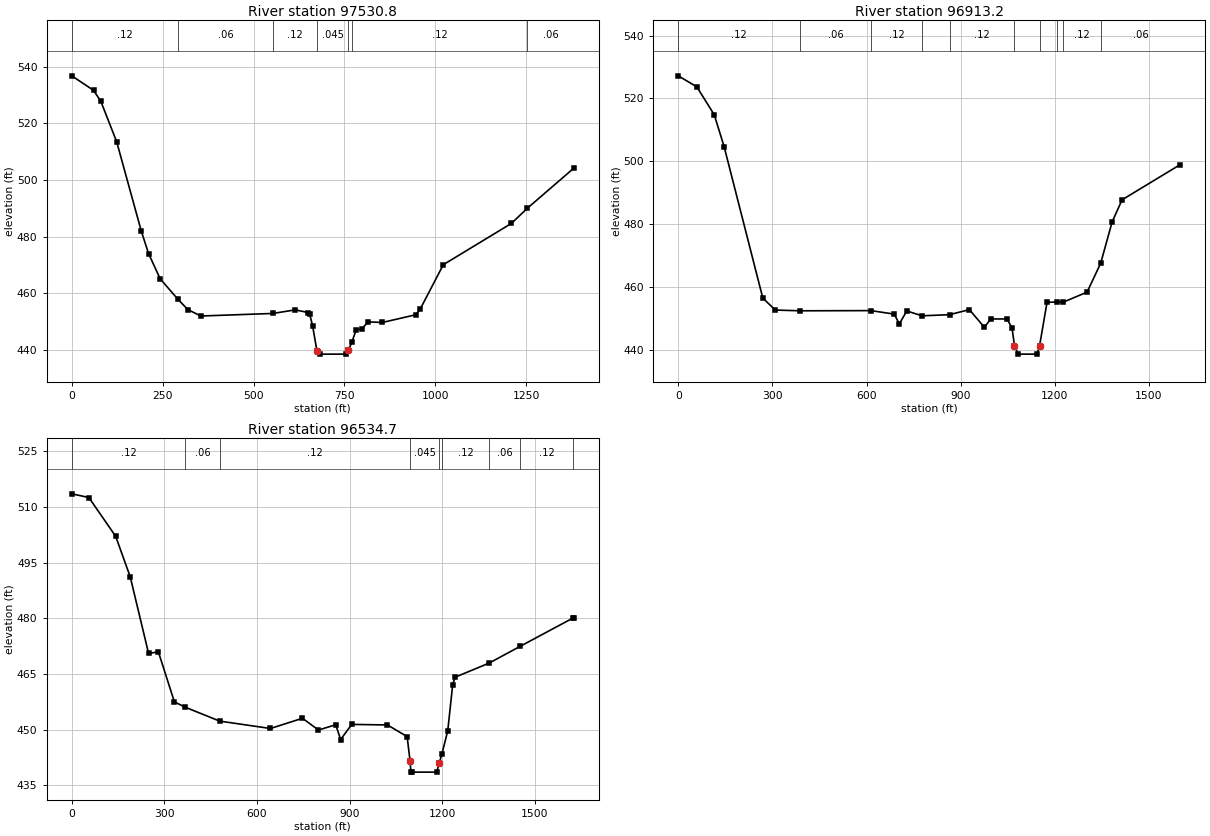
Type RM Length L Ch R = 1 ,97530.8 ,608.3,617.6,626.8
XS GIS Cut Line= 4
     2373658.603      359720.104     2373853.813      359718.054
     2374669.785      359492.359     2374978.048       359351.18
#Sta/Elev= 30
       0  536.73    59.8  531.63    79.7  527.81   123.5  513.49   191.2  481.98
   211.2  474.07   243.1  465.16  291.74457.9752     319  454.32     355  452.04
  552.93  452.94   614.5   454.2   650.5  453.27   654.5  452.64   662.4  448.56
   674.4  439.64   682.4   438.6   754.3   438.6  760.95 439.883  770.35442.8435
   782.3  447.17   798.2  447.48   814.2  449.98   854.1  449.76     946  452.48
     958   454.4  1021.9  470.14  1209.4  484.71 1253.26 490.066  1380.9  504.18
#Mann= 7 ,-1 , 0
       0     .12       0  291.74     .06       0  552.93     .12       0
   674.4    .045       0  760.95     .04       0  770.35     .12       0
 1253.26     .06       0
Bank Sta=674.4,760.95
XS Rating Curve= 0 ,0
Exp/Cntr=0.3,0.1

Type RM Length L Ch R = 1 ,96913.2 ,377.6,378.4,379.2
XS GIS Cut Line= 4
     2373589.056      360082.637     2373793.049      360108.679
     2374973.817      360077.708       2375177.7      360015.243
#Sta/Elev= 30
       0  527.21    59.3   523.7   114.7  514.83   146.3  504.64   269.5  456.45
   309.4  452.63  388.61452.3938  613.93452.4569   688.5  451.34   704.5  448.22
   728.4  452.34  776.99 450.801  864.68451.1629   927.9  452.77   975.8  447.12
   995.8   449.8  1047.6   449.8  1063.6  447.01  1071.6  441.31  1083.6   438.6
  1143.4   438.6  1151.4  441.16  1175.3  455.08 1208.47455.2137 1227.54455.1591
    1303  458.35 1346.47467.5749  1382.8   480.7  1414.5  487.74  1600.1  498.96
#Mann= 10 ,-1 , 0
       0     .12       0  388.61     .06       0  613.93     .12       0
  776.99     .06       0  864.68     .12       0  1071.6    .045       0
  1151.4     .12       0 1208.47     .06       0 1227.54     .12       0
 1346.47     .06       0
#XS Ineff= 2 , 0
       0                    1232       0
Permanent Ineff=
       F       F
Bank Sta=1071.6,1151.4
XS Rating Curve= 0 ,0
Exp/Cntr=0.3,0.1

Type RM Length L Ch R = 1 ,96534.7 ,550.5,556.7,563.6
XS GIS Cut Line= 4
     2373698.592      360687.783     2373742.862      360442.992
     2374867.862      360456.013     2375120.467      360445.596
#Sta/Elev= 30
       0  513.53    55.3  512.54   142.2   502.1   189.5  491.15   248.8  470.58
   280.7  470.96   332.5  457.52  367.63456.0817  479.15452.3358   643.7  450.35
   747.5   453.1   799.3  449.93   855.2  451.36   871.1  447.37     907  451.45
  1022.8   451.3  1086.6  448.17  1096.1441.5475  1098.6  438.76  1102.5   438.6
  1182.3   438.6  1190.3  440.96 1198.81443.3673  1218.2  449.75  1234.2  462.17
  1242.2  464.17 1351.78467.9381 1452.86472.4721 1624.22480.1022  1626.7  480.22
#Mann= 9 ,-1 , 0
       0     .12       0  367.63     .06       0  479.15     .12       0
  1096.1    .045       0  1190.3     .04       0 1198.81     .12       0
 1351.78     .06       0 1452.86     .12       0 1624.22     .06       0
Bank Sta=1096.1,1190.3
XS Rating Curve= 0 ,0
Exp/Cntr=0.3,0.1