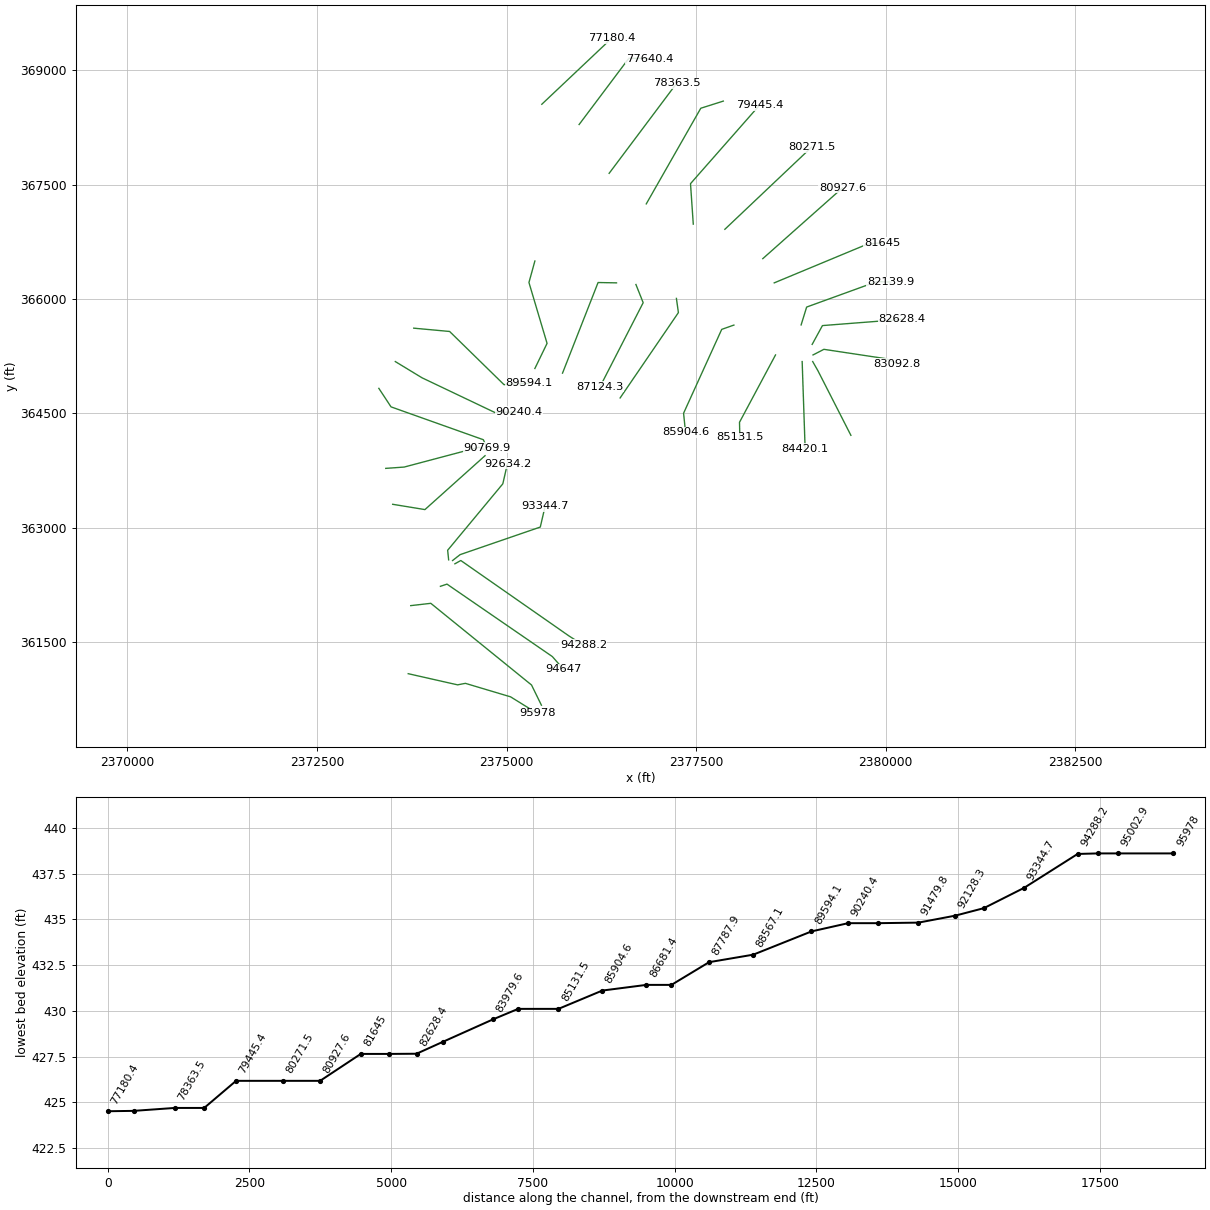
HEC-RAS study BACKCREEK.prj: BACKCREEK

--- BACKCREEK.g01 (geometry) --- (continued)

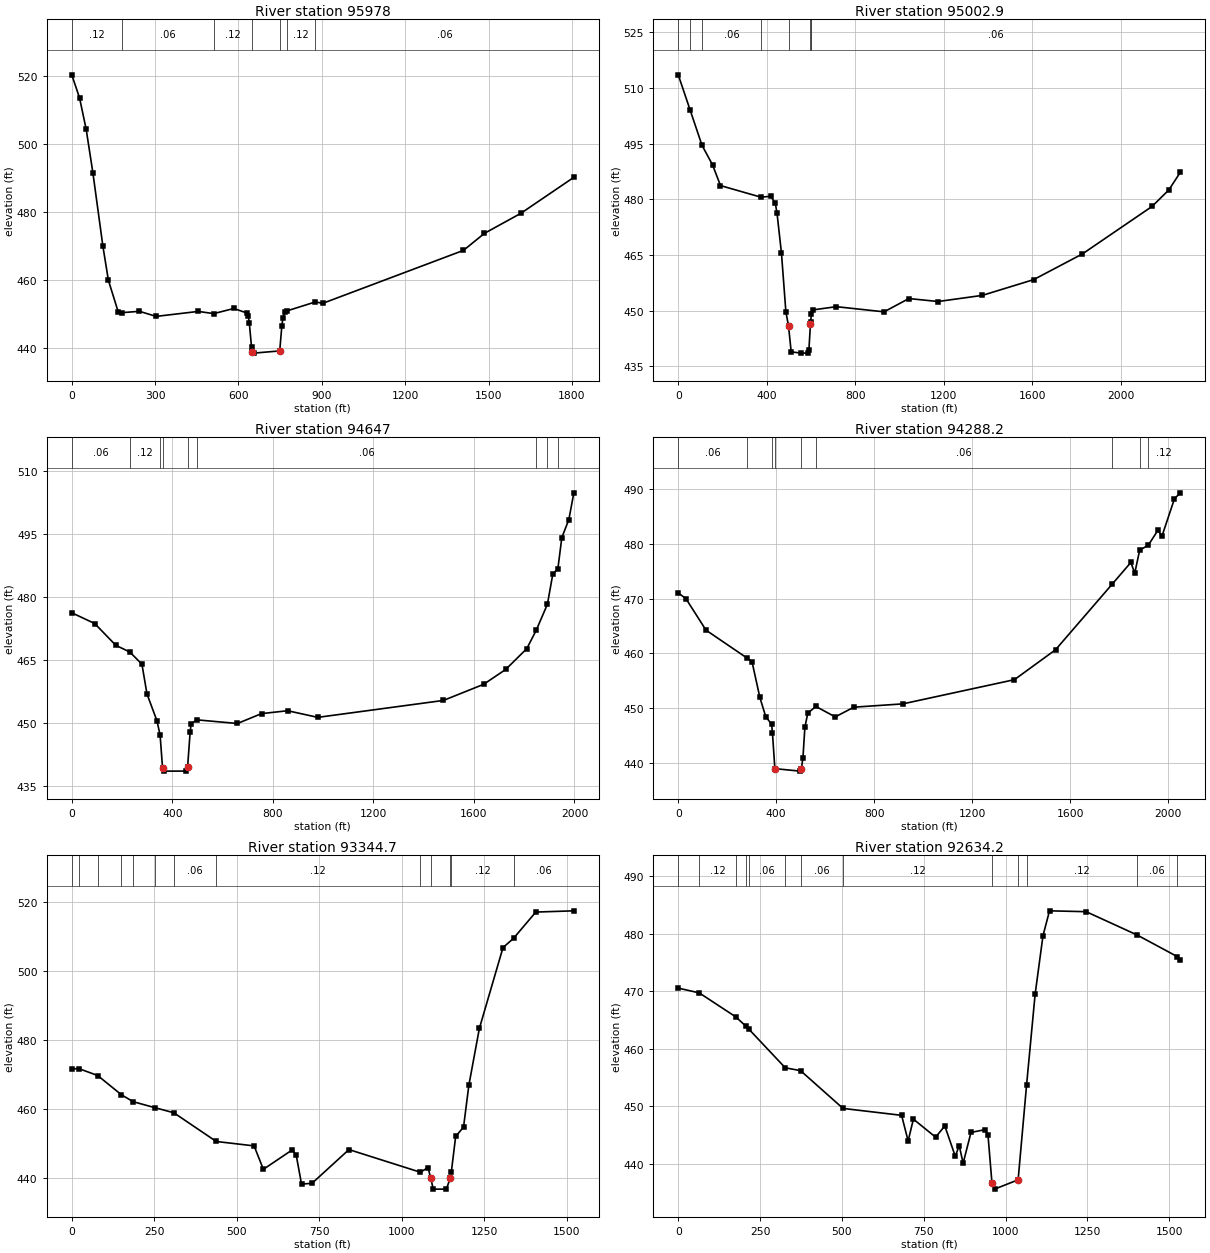
Type RM Length L Ch R = 1 ,95978   ,1007.1,975.2,942.6
XS GIS Cut Line= 5
     2373702.932      361081.881     2374353.658      360935.415
     2374456.404      360955.145     2375052.758      360778.061
     2375404.321      360561.047
#Sta/Elev= 30
       0  520.21      28  513.45    51.9   504.2    75.9  491.55   111.8  470.07
   131.8  459.95   167.8  450.52  180.02 450.468   243.6  450.86   303.6  449.37
   455.3  450.83  511.01450.1857   583.1  451.69   631.1  450.34     635  449.57
     639  447.42     647   440.3  650.34439.0558     655   438.6   748.4  439.25
   756.1  446.66     760  448.96   767.8  450.76  774.87450.9973   876.9 453.616
   903.2   453.2  1409.6  468.73  1485.1  473.72  1616.2   479.6  1806.9  490.15
#Mann= 7 ,-1 , 0
       0     .12       0  180.02     .06       0  511.01     .12       0
  650.34    .045       0   748.4     .04       0  774.87     .12       0
   876.9     .06       0
Bank Sta=650.34,748.4
XS Rating Curve= 0 ,0
Exp/Cntr=0.3,0.1

Type RM Length L Ch R = 1 ,95002.9 ,352.8,355.9,358.9
XS GIS Cut Line= 4
     2373735.918       361975.11     2374000.675      362005.492
       2375328.8      360933.443     2375459.008      360668.686
#Sta/Elev= 30
       0  513.55   53.02 504.191  107.37 494.567   155.1   489.3   190.9  483.72
  373.96480.5955   418.4  480.85   438.4  479.02   446.4  476.25   466.4  465.52
   486.3  449.74   498.3   445.9   510.3  438.94   555.6   438.6   586.3  438.62
   590.3  439.46  597.52446.4849   598.1 447.091  601.84449.1054   610.3  450.26
   714.2  451.11     930  449.72    1042   453.3  1173.9   452.5  1373.7  454.15
  1605.6  458.39  1825.4  465.29  2140.8  478.11  2216.5  482.55  2268.4  487.29
#Mann= 8 ,-1 , 0
       0     .06       0   53.02     .12       0  107.37     .06       0
  373.96     .12       0   498.3    .045       0  597.52     .04       0
   598.1     .12       0  601.84     .06       0
Bank Sta=498.3,597.52
XS Rating Curve= 0 ,0
Exp/Cntr=0.3,0.1

Type RM Length L Ch R = 1 ,94647   ,359.2,358.8,358.6
XS GIS Cut Line= 4
     2374127.353      362228.785     2374214.056      362257.406
     2375602.945      361306.885     2375750.617      361139.375
#Sta/Elev= 30
       0   476.3    91.3  473.74   175.3  468.55  230.98466.9609   279.2  464.05
   299.2  456.98   339.2  450.54  351.47447.1568  361.14439.3838   367.1   438.6
   455.1  438.61  460.89439.6163   471.1  447.99   475.1  449.92  497.92450.8059
     659  449.94   754.9  452.29   858.8  452.98   978.8   451.4  1478.5  455.43
  1638.4  459.26  1726.3   462.8  1810.2  467.75 1847.78472.1178 1892.46478.3341
  1913.9  485.51 1933.99486.7498  1949.8  494.22  1977.7  498.48  1997.6  504.86
#Mann= 9 ,-1 , 0
       0     .06       0  230.98     .12       0  351.47     .04       0
  361.14    .045       0  460.89     .12       0  497.92     .06       0
 1847.78     .12       0 1892.46    .016       0 1933.99     .12       0
Bank Sta=361.14,460.89
XS Rating Curve= 0 ,0
Exp/Cntr=0.3,0.1

Type RM Length L Ch R = 1 ,94288.2 ,907.2,943.6,979.7
XS GIS Cut Line= 4
     2374318.325      362523.923      2374396.45      362567.326
     2375824.299      361575.982     2376011.799      361457.927
#Sta/Elev= 30
       0  471.03    31.1  470.01   113.4  464.25  279.65459.2041   301.2  458.49
   333.1     452   357.1   448.5   381.1   447.1  384.56445.5084  394.38439.0216
     497  438.57  502.23438.8706     509     441   516.9  446.56   528.9  449.15
  561.97450.3499   640.8  448.45   716.7  450.22   916.5  450.82  1372.1  455.23
  1539.9  460.68  1771.4472.6465  1847.4  476.59  1863.2  474.62  1883.2 478.815
 1918.75479.7395  1958.2  482.48    1974  481.34  2025.4   488.2  2049.2  489.27
#Mann= 9 ,-1 , 0
       0     .06       0  279.65     .12       0  384.56     .04       0
  394.38    .045       0  502.23     .12       0  561.97     .06       0
  1771.4     .12       0  1883.2    .016       0 1918.75     .12       0
Bank Sta=394.38,502.23
XS Rating Curve= 0 ,0
Exp/Cntr=0.3,0.1

Type RM Length L Ch R = 1 ,93344.7 ,689.8,710.5,731.1
XS GIS Cut Line= 4
     2374287.943      362567.326      2374386.96      362644.381
     2375444.251       363006.36     2375507.459      363277.371
#Sta/Elev= 30
       0  471.65   22.19471.7033   78.42469.7288  149.85464.1806  185.67462.1289
  251.99460.3772  309.15458.9078  437.81450.5624   552.5  449.28   580.5  442.47
   668.3  448.14   680.2  446.53   696.2  438.17   728.1  438.42   839.9  448.21
 1056.24441.6294  1079.4  442.98  1087.7439.9031  1095.3  436.72  1135.2  436.72
  1147.2  440.09 1150.06441.6988  1163.2  452.01  1187.1  454.75  1203.1  466.86
    1235  483.39  1306.6  506.89 1338.45509.5632    1406  517.21  1521.3  517.57
#Mann= 13 ,-1 , 0
       0     .06       0   22.19     .12       0   78.42     .06       0
  149.85     .12       0  185.67     .06       0  251.99    .016       0
  309.15     .06       0  437.81     .12       0 1056.24     .04       0
  1087.7    .045       0  1147.2     .04       0 1150.06     .12       0
 1338.45     .06       0
Bank Sta=1087.7,1147.2
XS Rating Curve= 0 ,0
Exp/Cntr=0.3,0.1

Type RM Length L Ch R = 1 ,92634.2 ,512.7,505.9,499
XS GIS Cut Line= 4
      2374235.86      362576.007     2374222.839      362701.875
     2374950.328      363574.068     2375011.092      363838.825
#Sta/Elev= 30
       0  470.56   64.14469.7335  175.63465.5674  207.63463.8978   214.7 463.487
  326.97 456.706  373.66 456.211  503.45449.6434   682.4  448.44   702.4  443.98
   718.4  447.78   786.4  444.64   814.4   446.6   846.4  441.32   858.4  443.18
   870.4  440.11   894.4  445.47   938.4  445.96   946.4  444.97   958.4  436.71
   966.4  435.61  1038.4  437.23 1064.22453.7226  1090.3  469.48  1114.3  479.66
  1134.3     484  1246.3  483.85  1401.9479.7985 1524.86476.0355  1533.9  475.38
#Mann= 13 ,-1 , 0
       0     .06       0   64.14     .12       0  175.63     .06       0
  207.63     .12       0   214.7     .06       0  326.97    .016       0
  373.66     .06       0  503.45     .12       0   958.4    .045       0
  1038.4     .04       0 1064.22     .12       0  1401.9     .06       0
 1524.86     .12       0
Bank Sta=958.4,1038.4
XS Rating Curve= 0 ,0
Exp/Cntr=0.3,0.1

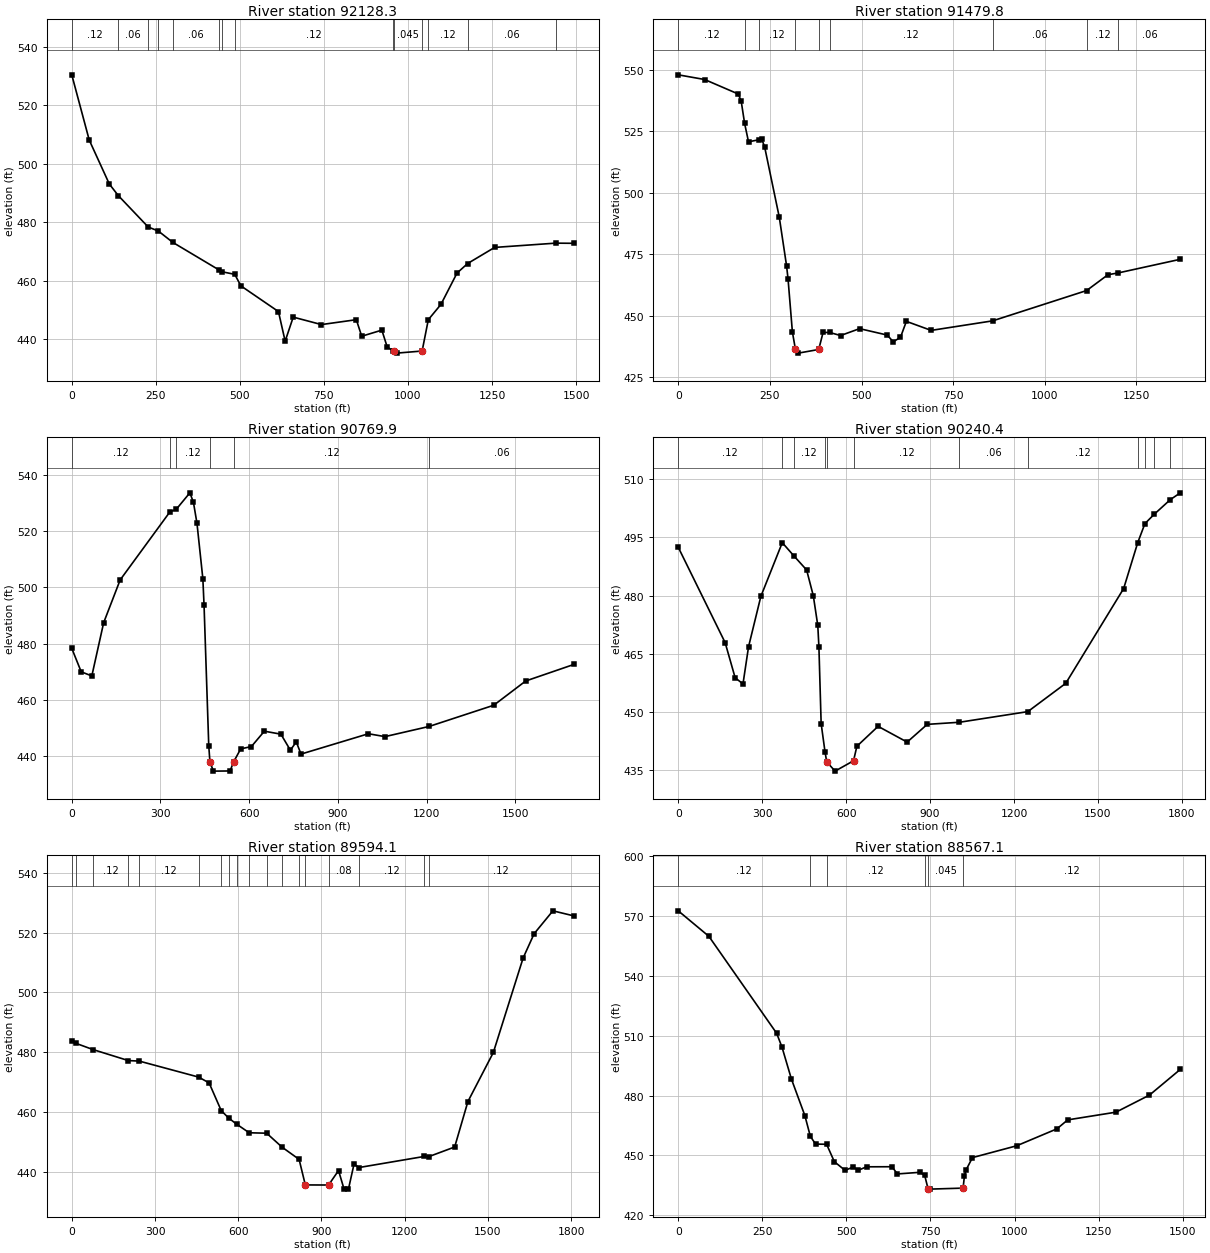
Type RM Length L Ch R = 1 ,92128.3 ,665.8,648.5,631.2
XS GIS Cut Line= 3
     2373498.013      363305.173      2373923.36      363235.729
     2374715.953      363942.992
#Sta/Elev= 30
       0  530.43    51.9  508.12   111.7  493.06  138.41 489.098  227.37478.3443
   257.1477.0092  300.37473.1023  437.83463.6712  447.44463.0281  484.75 462.159
   502.9  458.22   614.7  449.42   634.6  439.28   658.6  447.52   742.5  444.97
   846.3  446.64   862.3  440.98   922.2  443.07   938.2  437.27  956.78435.9487
   958.1  435.82   966.1   435.2    1042  435.92 1060.38446.6436  1097.9  451.87
  1145.8   462.6 1177.39465.8664  1257.6  471.37 1439.03 472.833  1493.2  472.78
#Mann= 14 ,-1 , 0
       0     .12       0  138.41     .06       0  227.37     .12       0
   257.1     .08       0  300.37     .06       0  437.83     .12       0
  447.44    .016       0  484.75     .12       0  956.78     .04       0
   958.1    .045       0    1042     .04       0 1060.38     .12       0
 1177.39     .06       0 1439.03     .12       0
Bank Sta=958.1,1042
XS Rating Curve= 0 ,0
Exp/Cntr=0.3,0.1

Type RM Length L Ch R = 1 ,91479.8 ,732.1,709.9,687.7
XS GIS Cut Line= 4
     2373406.764      363776.503      2373649.82      363793.864
      2374636.23      364054.201     2374733.314      364012.436
#Sta/Elev= 30
       0  547.93    71.9  546.03   163.8  540.13   171.8  537.18  181.06528.1829
   191.7  520.71  220.23521.5417   227.7  521.85   235.7  518.62   275.6   490.1
   295.5  470.33   299.5  465.04   311.4  443.44   319.4  436.58   327.4  434.82
   383.2   436.3   395.1  443.22  412.89443.2189   442.9  441.97   494.7  444.77
   570.4  442.15   586.4  439.41   606.3  441.25   622.3  447.73     690  444.06
  857.82 447.941 1114.14460.2618  1172.2  466.69 1200.54467.4264  1369.6  472.96
#Mann= 9 ,-1 , 0
       0     .12       0  181.06    .016       0  220.23     .12       0
   319.4    .045       0   383.2     .04       0  412.89     .12       0
  857.82     .06       0 1114.14     .12       0 1200.54     .06       0
Bank Sta=319.4,383.2
XS Rating Curve= 0 ,0
Exp/Cntr=0.3,0.1

Type RM Length L Ch R = 1 ,90769.9 ,532.4,529.5,526.6
XS GIS Cut Line= 4
     2373315.619       364826.85     2373476.209      364583.795
     2374693.528      364152.661     2374739.332      364047.361
#Sta/Elev= 30
       0  478.38    31.9  470.05    67.8  468.58   107.8  487.48   163.6  502.67
  331.55526.7888  353.17  527.73   399.3  533.59   411.3  530.26   423.3   522.8
   443.2  503.13   447.2  493.87   463.2  443.75   467.2  437.94   479.2  434.79
   535.2  434.85   547.2  438.06   571.2  442.69   607.2   443.5   651.2  448.97
   707.1  447.91   739.1  442.23   759.1  445.17   775.1  440.84    1003  448.06
    1059  447.04 1208.55450.6613  1426.8  458.18  1534.8  466.79  1697.6  472.66
#Mann= 6 ,-1 , 0
       0     .12       0  331.55    .016       0  353.17     .12       0
   467.2    .045       0   547.2     .12       0 1208.55     .06       0
Bank Sta=467.2,547.2
XS Rating Curve= 0 ,0
Exp/Cntr=0.3,0.1

Type RM Length L Ch R = 1 ,90240.4 ,659.5,646.3,633.1
XS GIS Cut Line= 4
     2373532.632      365178.413     2373884.195      364965.739
     2374847.086       364509.11     2375164.577      364518.691
#Sta/Elev= 30
       0  492.42   167.6  467.87   203.4  458.82   231.4  457.24   251.3  466.82
   295.2  479.76  371.77493.6019  412.26490.2808   458.8  486.57   482.7  479.93
   498.7  472.28   502.7  466.79   510.7  447.03  524.42439.8004   530.6  437.19
   560.4  434.79   626.4  437.45   638.4  441.19   714.2  446.32     818  442.26
   889.8  446.83 1004.98447.3693 1249.23450.1057  1384.8  457.39  1591.7  481.79
 1642.13493.6245  1667.7 498.502 1701.24500.9277 1758.49504.6792  1794.2  506.43
#Mann= 12 ,-1 , 0
       0     .12       0  371.77    .016       0  412.26     .12       0
  524.42     .04       0   530.6    .045       0   626.4     .12       0
 1004.98     .06       0 1249.23     .12       0 1642.13     .06       0
  1667.7     .12       0 1701.24     .06       0 1758.49     .12       0
#XS Ineff= 2 , 0
       0     375                       0
Permanent Ineff=
       F       F
Bank Sta=530.6,626.4
XS Rating Curve= 0 ,0
Exp/Cntr=0.3,0.1

Type RM Length L Ch R = 1 ,89594.1 ,1046.5,1027,1007.8
XS GIS Cut Line= 4
     2373775.688      365616.781     2374248.778      365573.378
     2374965.792      364875.366     2375299.228      364893.715
#Sta/Elev= 30
       0   483.8   15.22483.0003   76.34480.9325     204477.2503  243.26477.0806
  457.43471.7342     495   469.8  538.67460.5553  565.26458.0887  593.93456.0397
  639.59453.1555  702.42 453.007  758.28448.3316   819.4444.2712   841.8  435.74
   925.6  435.71   961.5  440.54   981.4  434.36   997.3  434.34  1017.3  442.69
 1035.58441.5557 1270.16445.2444 1286.34445.1697  1380.1   448.4  1427.9  463.59
  1519.5  479.95  1626.8  511.48  1666.6  519.61  1734.2  527.24  1809.7  525.55
#Mann= 18 ,-1 , 0
       0     .06       0   15.22    .016       0   76.34     .12       0
     204     .08       0  243.26     .12       0  457.43     .06       0
  538.67     .12       0  565.26     .06       0  593.93    .016       0
  639.59     .08       0  702.42     .06       0  758.28     .12       0
   819.4     .04       0   841.8    .045       0   925.6     .08       0
 1035.58     .12       0 1270.16     .06       0 1286.34     .12       0
Bank Sta=841.8,925.6
XS Rating Curve= 0 ,0
Exp/Cntr=0.3,0.1

Type RM Length L Ch R = 1 ,88567.1 ,805.2,779.2,752.9
XS GIS Cut Line= 4
      2375372.91      366497.857     2375294.785      366215.739
       2375533.5      365417.128      2375372.91      365087.267
#Sta/Elev= 30
       0  572.73      91  559.96   292.7  511.27   308.7  504.25   336.6   488.3
   376.5  470.01  392.85459.5778   408.4  455.68  441.25455.5746   464.2  446.85
   496.1  442.49   520.1  444.16     536  442.57   559.9  444.27   635.7  444.31
   651.7  440.69   719.5  441.52  732.98 439.932  742.91433.2589   747.4  433.07
   847.1  433.58   851.1  439.67   855.1  442.43     875  448.89  1006.6  454.83
  1126.3  463.33  1158.2  467.82  1301.7  471.69  1401.4  480.26  1493.1  493.16
#Mann= 6 ,-1 , 0
       0     .12       0  392.85    .016       0  441.25     .12       0
  732.98     .04       0  742.91    .045       0   847.1     .12       0
Bank Sta=742.91,847.1
XS Rating Curve= 0 ,0
Exp/Cntr=0.3,0.1

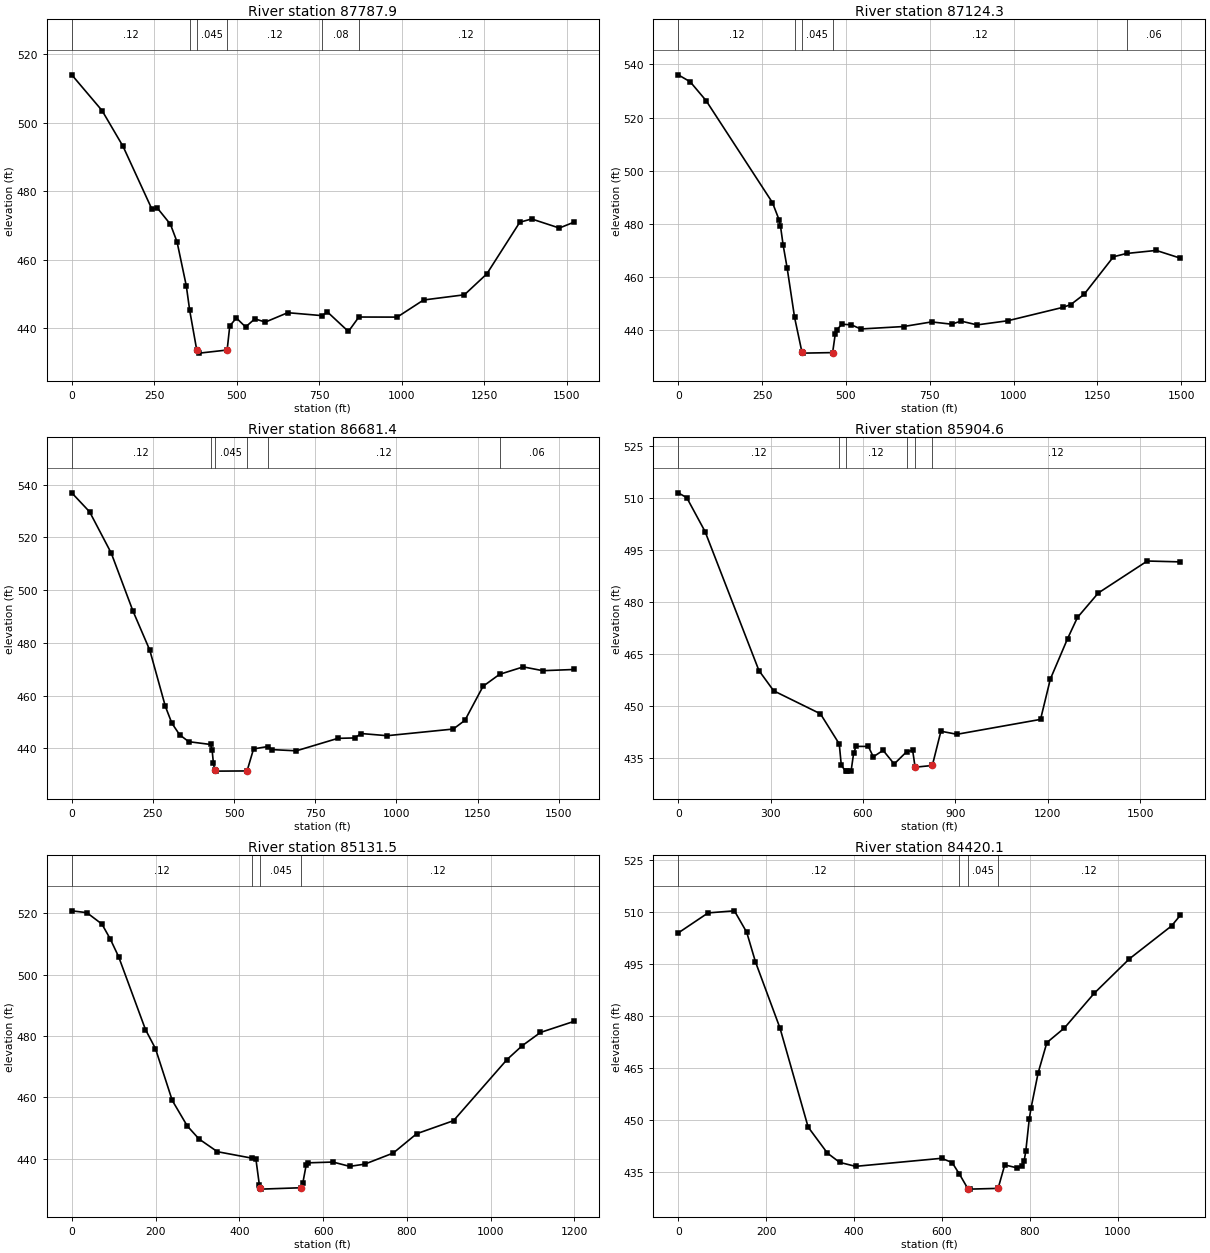
Type RM Length L Ch R = 1 ,87787.9 ,666.6,663.5,660.6
XS GIS Cut Line= 3
     2376449.299      366211.399     2376206.244      366215.739
     2375737.494      365026.503
#Sta/Elev= 30
       0  513.95    91.7  503.52   155.4  493.05   243.1  474.66   259.1  475.06
     299  470.29     319  465.16     347  452.34  357.38 445.117   378.9  433.45
   386.9  432.66   470.8  433.57   478.8  440.61   498.8  442.92   526.7   440.3
   554.7  442.67   586.6  441.73   654.5  444.47   758.9443.6075   774.4  444.71
   838.3  438.98  869.95443.2054   986.1  443.18    1066  448.18  1189.8   449.7
  1257.7  455.81  1357.6  470.89  1393.6  471.85  1477.4   469.2  1521.4  470.89
#Mann= 6 ,-1 , 0
       0     .12       0  357.38     .04       0   378.9    .045       0
   470.8     .12       0   758.9     .08       0  869.95     .12       0
Bank Sta=378.9,470.8
XS Rating Curve= 0 ,0
Exp/Cntr=0.3,0.1

Type RM Length L Ch R = 1 ,87124.3 ,447.3,442.9,438.2
XS GIS Cut Line= 3
     2376705.375      366189.697     2376800.862      365950.982
     2376232.285      364848.552
#Sta/Elev= 30
       0  536.09    35.6  533.48    83.1  526.38     281  488.03     301  481.49
     305  479.18   312.9  472.06   324.9  463.39  347.04444.8332   368.8  431.89
   372.8  431.42   460.5  431.62   468.5  438.77   472.5  440.15   488.4  442.29
   516.4  442.07   544.3   440.5   671.9  441.42   755.7  443.16   815.5   442.3
   843.4  443.47   891.3  442.04     983   443.6  1146.5  448.61  1170.5  449.65
  1210.4  453.51  1298.1  467.66 1337.01468.8981  1425.7  470.05  1497.5  467.14
#Mann= 5 ,-1 , 0
       0     .12       0  347.04     .04       0   368.8    .045       0
   460.5     .12       0 1337.01     .06       0
Bank Sta=368.8,460.5
XS Rating Curve= 0 ,0
Exp/Cntr=0.3,0.1

Type RM Length L Ch R = 1 ,86681.4 ,770,776.9,784
XS GIS Cut Line= 3
      2377239.23      366007.406     2377265.271      365820.774
     2376497.042      364700.982
#Sta/Elev= 30
       0   536.9      55  529.69   121.7  514.02   188.4  492.12   240.4  477.23
   288.3  455.94   308.3  449.59   332.2   445.2   360.2  442.58  427.45441.5269
   432.1  439.59   436.1  434.64   440.1  431.69   444.1  431.42   539.9  431.49
   559.9  439.83  604.25440.7525   615.8  439.58   691.7  439.12   819.5  443.84
   871.4     444   891.4  445.67   971.3  444.85    1175  447.37  1210.9  450.67
  1266.8  463.58 1317.47468.0967  1390.6  470.93  1450.6  469.49  1546.4  469.94
#Mann= 6 ,-1 , 0
       0     .12       0  427.45     .04       0   440.1    .045       0
   539.9     .08       0  604.25     .12       0 1317.47     .06       0
Bank Sta=440.1,539.9
XS Rating Curve= 0 ,0
Exp/Cntr=0.3,0.1

Type RM Length L Ch R = 1 ,85904.6 ,775.4,773.1,770.7
XS GIS Cut Line= 4
     2377997.203      365657.401     2377836.612      365600.978
     2377333.651      364500.194     2377359.182      364251.151
#Sta/Elev= 30
       0  511.43    27.7  510.03    87.1  500.26   262.1  460.14     310  454.29
   461.8  447.66  523.01438.9549   529.7  432.75  543.72  431.12   549.7  431.11
   561.6  431.21   569.6  436.24   577.6  438.25   617.6  438.24   633.5  435.24
   665.5  437.11   701.4  433.16  741.66436.6953   761.4  437.12  769.37432.2434
   825.3  432.74   853.2  442.63   905.2  441.74  1176.8  446.04  1208.7  457.69
  1264.6  469.34  1296.6  475.45  1364.5  482.53  1523.5  491.75  1630.8   491.5
#Mann= 6 ,-1 , 0
       0     .12       0  523.01     .04       0  543.72     .12       0
  741.66     .04       0  769.37    .045       0   825.3     .12       0
Bank Sta=769.37,825.3
XS Rating Curve= 0 ,0
Exp/Cntr=0.3,0.1

Type RM Length L Ch R = 1 ,85131.5 ,691.6,711.4,731.2
XS GIS Cut Line= 3
     2378545.653      365265.218     2378070.987       364381.36
     2378075.328      364186.047
#Sta/Elev= 30
       0  520.84      36  520.24      72  516.52    91.9  511.66   111.9  505.87
   175.9  482.15   199.8  475.92   239.8  459.04   275.8  450.69   303.8  446.45
   347.7  442.31  430.24440.2045   439.7  439.79   447.7  431.61  450.46 430.575
   451.7  430.11   547.6  430.56   551.6  432.12   559.6  437.98   563.6  438.68
   623.5  438.94   663.5  437.53   699.5  438.26   767.4  441.87   823.4  448.17
   911.3  452.42  1039.1  472.36    1075  476.83  1118.9  481.19  1198.6  484.78
#Mann= 4 ,-1 , 0
       0     .12       0  430.24     .04       0  450.46    .045       0
   547.6     .12       0
Bank Sta=450.46,547.6
XS Rating Curve= 0 ,0
Exp/Cntr=0.3,0.1

Type RM Length L Ch R = 1 ,84420.1 ,423.9,440.5,457.1
XS GIS Cut Line= 2
     2378897.216      365178.413     2378936.278       364036.92
#Sta/Elev= 30
       0     504    67.9  509.78   127.8  510.38   155.8  504.19   175.7  495.65
   231.6  476.52   295.5  448.01   339.4  440.49   367.4  437.82   403.4  436.68
     599     439     623  437.79  639.67434.4424   658.9  430.24   662.9  430.11
  727.69 430.328   742.8   437.1   770.8  436.24   782.7  436.71   786.7   438.1
   790.7   441.1   798.7  450.48   802.7  453.54   818.7  463.61   838.6  472.37
   878.6   476.6   946.5  486.62  1026.4  496.54  1122.2  506.02  1142.2  509.09
#Mann= 4 ,-1 , 0
       0     .12       0  639.67     .04       0   658.9    .045       0
  727.69     .12       0
Bank Sta=658.9,727.69
XS Rating Curve= 0 ,0
Exp/Cntr=0.3,0.1

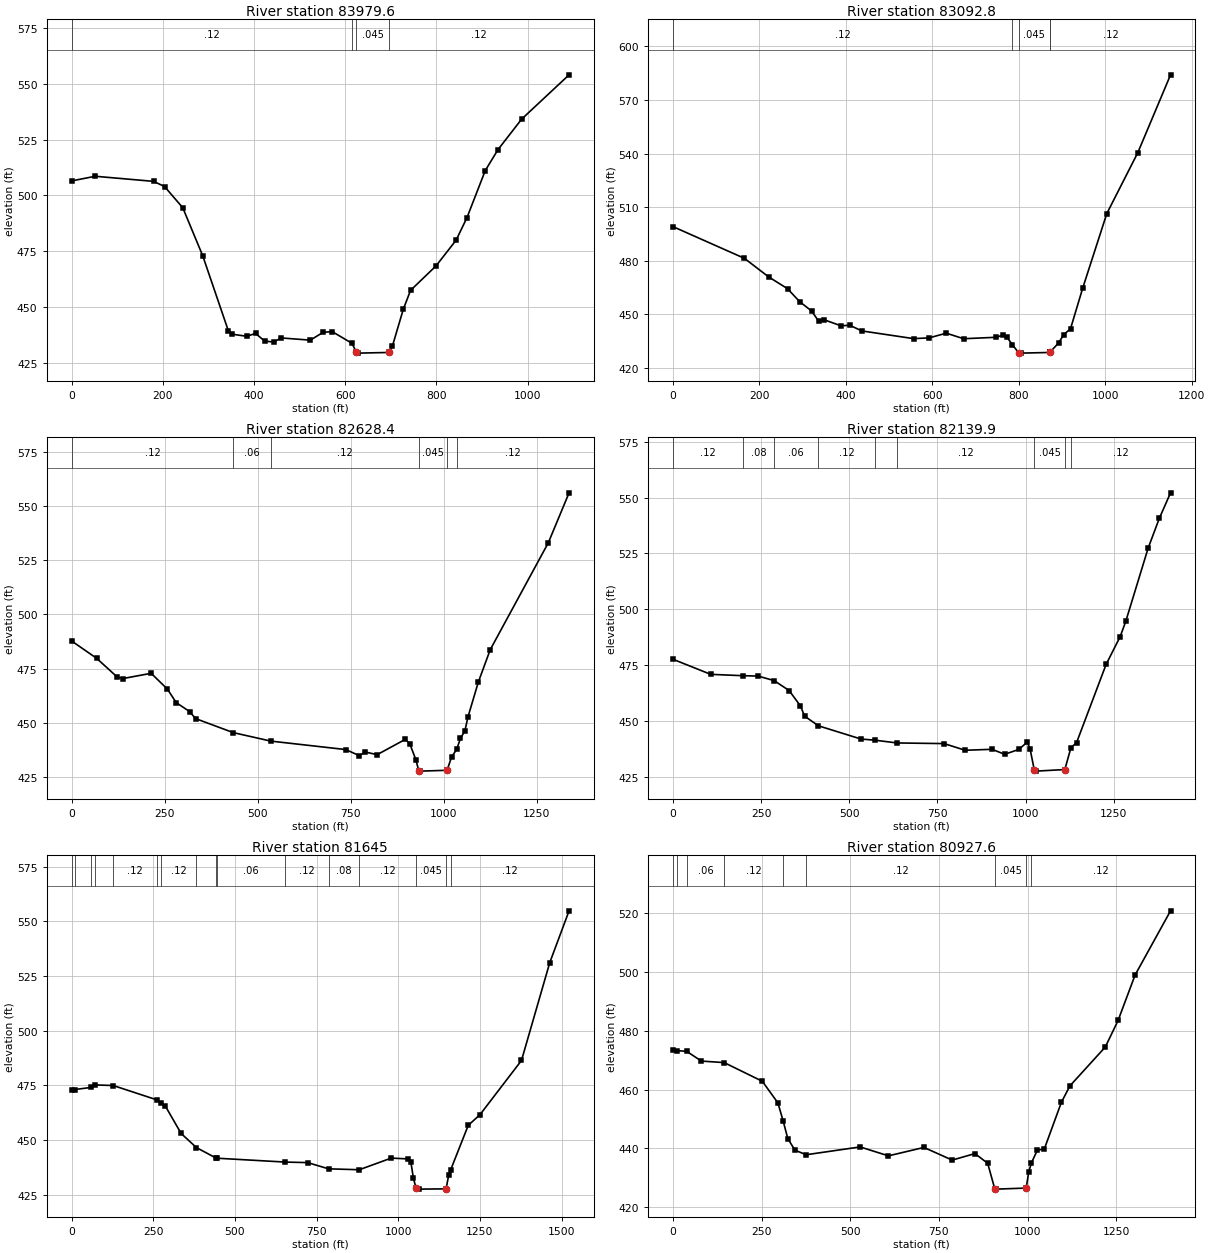
Type RM Length L Ch R = 1 ,83979.6 ,850.8,886.8,922.8
XS GIS Cut Line= 3
     2379036.105      365178.413     2379105.549      365056.885
     2379539.577      364210.531
#Sta/Elev= 30
       0  506.51      52  508.59   179.9  506.31   203.9  504.01   243.9  494.53
   287.8     473   343.8  439.57   351.8  438.01   383.8  437.08   403.7  438.32
   423.7  434.89   443.7  434.53   459.7  436.33   523.6  435.34   551.6  438.83
   571.6  439.16  614.95 433.931  624.85 429.858   627.5  429.54  697.01429.8407
   703.5  432.56   727.4  449.05   743.4  457.58   799.4  468.55   843.3  480.01
   867.3  490.15   907.3  511.14   935.3  520.53   987.2  534.15  1091.1  553.93
#Mann= 4 ,-1 , 0
       0     .12       0  614.95     .04       0  624.85    .045       0
  697.01     .12       0
Bank Sta=624.85,697.01
XS Rating Curve= 0 ,0
Exp/Cntr=0.3,0.1

Type RM Length L Ch R = 1 ,83092.8 ,455.9,464.5,473
XS GIS Cut Line= 4
     2379040.445      365265.218     2379183.674      365339.003
      2380004.93      365215.669     2380149.981      365149.589
#Sta/Elev= 30
       0  499.09   165.1  481.37     221  471.01   264.9  464.37   292.9  457.12
   320.8  451.85   336.8   446.2   348.8  447.06   388.7  443.58   408.7  443.94
   436.6  440.74   556.4  436.43   592.3  436.83   632.2  439.48   672.2  436.37
     748  437.18     764   438.5     772  437.38  784.91433.1119   799.9  428.38
   803.9  428.31   871.8  428.68  873.16429.1288   891.8  433.93   903.7  438.55
   919.7  442.04   947.7   464.6  1003.5  506.38  1075.3  540.52    1151  584.05
#Mann= 5 ,-1 , 0
       0     .12       0  784.91     .04       0   799.9    .045       0
   871.8     .04       0  873.16     .12       0
Bank Sta=799.9,871.8
XS Rating Curve= 0 ,0
Exp/Cntr=0.3,0.1

Type RM Length L Ch R = 1 ,82628.4 ,478.3,488.5,498.7
XS GIS Cut Line= 3
      2379029.16      365404.107     2379164.577      365650.635
      2380216.66      365732.232
#Sta/Elev= 30
       0  487.74    67.4  479.72   122.8  471.06   138.6   470.4   213.9   472.8
   257.5   465.5   281.3  459.26   317.2  455.13   333.2   451.9  434.34445.4346
  535.06441.5208   736.9   437.6   772.9   434.8   788.9  436.48   820.9  435.25
   896.8  442.34   908.8  440.19   924.8  432.97   932.8   427.8   936.8  427.66
  1008.8  428.05  1020.7  434.12 1034.42437.6538  1044.7  442.76  1056.7  446.27
  1064.7  452.54  1092.7  468.74  1124.7   483.7  1280.6  532.99  1336.5  556.08
#Mann= 6 ,-1 , 0
       0     .12       0  434.34     .06       0  535.06     .12       0
   932.8    .045       0  1008.8     .04       0 1034.42     .12       0
Bank Sta=932.8,1008.8
XS Rating Curve= 0 ,0
Exp/Cntr=0.3,0.1

Type RM Length L Ch R = 1 ,82139.9 ,493.2,494.9,496.6
XS GIS Cut Line= 4
     2378883.327      365659.316     2378956.244      365893.691
     2379884.505      366228.971     2380063.175      366221.638
#Sta/Elev= 30
       0  477.67   106.9  470.93  199.31470.3132   241.5  470.16  286.96468.1174
   329.4  463.68   361.3  456.83   373.3  452.23  412.35447.9226   533.2     442
  573.06441.4811  635.31440.2507   768.9  439.96   828.8  436.98   904.8  437.41
   940.7  435.18   980.7  437.34  1004.6   440.6  1012.6  437.74  1024.6  428.24
  1028.6  427.65 1111.32428.3509 1128.76438.1767  1144.5  440.33  1228.4  475.36
  1268.2  487.76  1284.1  494.58  1347.6  527.34  1379.4  540.72  1411.2   552.1
#Mann= 9 ,-1 , 0
       0     .12       0  199.31     .08       0  286.96     .06       0
  412.35     .12       0  573.06     .06       0  635.31     .12       0
  1024.6    .045       0 1111.32     .04       0 1128.76     .12       0
Bank Sta=1024.6,1111.32
XS Rating Curve= 0 ,0
Exp/Cntr=0.3,0.1

Type RM Length L Ch R = 1 ,81645   ,704.9,717.4,729.8
XS GIS Cut Line= 3
      2378529.16      366211.399     2379754.444      366718.613
     2379950.328      366738.131
#Sta/Elev= 30
       0  472.86    9.45473.1226   58.38474.0766    72.5475.2425  127.54474.9691
  263.11468.3268   272.6 467.185   287.6  465.47   335.5  453.06  382.05446.6534
  441.67441.8922  444.16441.7796  654.32440.0059     723  439.76  786.63436.9221
  880.73436.5059   978.6  441.82  1030.5  441.45  1038.5  440.22  1046.5  432.66
  1054.5  428.09  1062.5  427.65 1146.49427.7657  1154.4  433.98 1160.92436.5957
  1214.3  456.77  1250.2  461.65  1377.3  486.41  1463.9  531.12    1523  554.76
#Mann= 16 ,-1 , 0
       0     .12       0    9.45    .016       0   58.38     .08       0
    72.5     .06       0  127.54     .12       0  263.11     .06       0
   272.6     .12       0  382.05     .06       0  441.67     .12       0
  444.16     .06       0  654.32     .12       0  786.63     .08       0
  880.73     .12       0  1054.5    .045       0 1146.49     .04       0
 1160.92     .12       0
Bank Sta=1054.5,1146.49
XS Rating Curve= 0 ,0
Exp/Cntr=0.3,0.1

Type RM Length L Ch R = 1 ,80927.6 ,654.9,656.2,657.5
XS GIS Cut Line= 2
     2378378.119      366529.107     2379429.494      367458.617
#Sta/Elev= 30
       0  473.31   10.73473.2041    38.3473.0025      80  469.67  144.38469.1544
   251.9  462.81   295.9  455.46  310.89449.2243   323.8  443.34   343.8  439.43
  375.42437.8552   527.8  440.51   607.7  437.48   707.7  440.34   787.6  436.04
   851.6  438.25   887.6  434.96   907.6  426.26   911.6  426.18  996.17426.5401
  1003.5  432.11 1011.15435.1501  1027.5  439.36  1047.5  439.87  1095.5  455.67
  1119.5  461.24  1219.4  474.45  1255.4  483.46  1303.4   498.9  1403.4   520.7
#Mann= 9 ,-1 , 0
       0     .12       0   10.73     .08       0    38.3     .06       0
  144.38     .12       0  310.89     .08       0  375.42     .12       0
   907.6    .045       0  996.17     .04       0 1011.15     .12       0
Bank Sta=907.6,996.17
XS Rating Curve= 0 ,0
Exp/Cntr=0.3,0.1

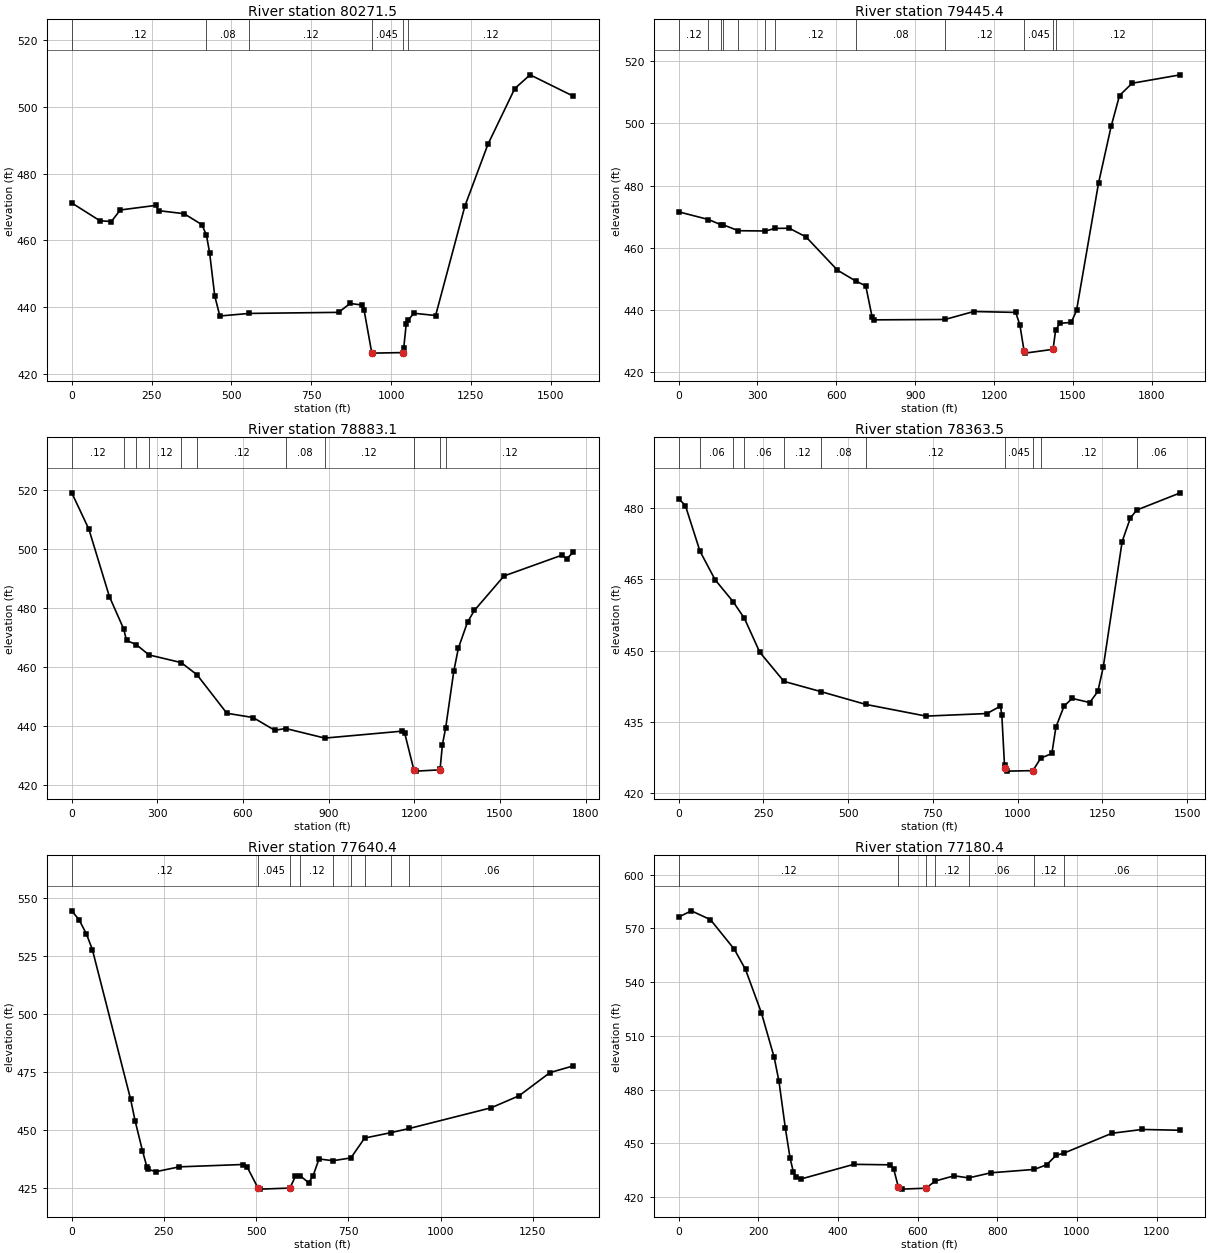
Type RM Length L Ch R = 1 ,80271.5 ,822.7,826.1,829.5
XS GIS Cut Line= 2
     2377878.119      366914.524     2379021.508      367992.471
#Sta/Elev= 30
       0  471.19      88  465.87     124  465.61   151.9  469.08   263.9  470.47
   271.9  468.88   351.9  467.97   407.8  464.67  421.92461.4903   431.8  456.24
   447.8  443.34   463.8  437.31  555.32438.0776   835.7   438.4   871.7  441.06
   907.7  440.62   915.6  439.04   939.6  426.28   943.6  426.18 1036.01426.3445
  1039.6  427.61  1047.6  434.98 1053.11436.0178  1071.6  438.13  1139.6  437.45
  1231.5  470.33  1303.5  488.78  1387.5  505.47  1435.5  509.59  1571.4  503.16
#Mann= 6 ,-1 , 0
       0     .12       0  421.92     .08       0  555.32     .12       0
   939.6    .045       0 1036.01     .04       0 1053.11     .12       0
Bank Sta=939.6,1036.01
XS Rating Curve= 0 ,0
Exp/Cntr=0.3,0.1

Type RM Length L Ch R = 1 ,79445.4 ,555.2,562.2,569.4
XS GIS Cut Line= 3
     2377461.452      366982.232     2377424.994      367513.482
     2378336.452      368544.732
#Sta/Elev= 30
       0  471.58  113.64 469.104  159.82467.4832  167.56467.4724  227.56465.5029
  330.36465.4263  367.28466.2546   421.2   466.3   484.8  463.52   604.3  452.84
  674.13449.3342     712  447.79     736   437.9   743.9  436.87 1013.54436.9908
  1122.9  439.55  1282.5  439.26  1298.4  435.23  1314.4  426.83  1318.4  426.18
 1424.65 427.404 1434.24433.4822    1450  435.76  1493.9  436.04  1513.9  439.88
  1597.6  480.79  1645.5     499  1677.4  508.94  1725.3  512.88  1908.8  515.59
#Mann= 12 ,-1 , 0
       0     .12       0  113.64    .016       0  159.82     .12       0
  167.56     .06       0  227.56     .12       0  330.36     .06       0
  367.28     .12       0  674.13     .08       0 1013.54     .12       0
  1314.4    .045       0 1424.65     .04       0 1434.24     .12       0
Bank Sta=1314.4,1424.65
XS Rating Curve= 0 ,0
Exp/Cntr=0.3,0.1

Type RM Length L Ch R = 1 ,78883.1 ,523.9,519.7,515.3
XS GIS Cut Line= 3
      2376841.66      367247.857      2377560.41      368503.066
     2377857.285      368596.816
#Sta/Elev= 30
       0  518.88    59.9   506.6   131.9  483.76  182.13472.7672   191.8  468.92
  225.89467.5372  270.43464.0308  383.56461.4262  438.94457.3008   543.4  444.28
   635.3  442.84   711.2  438.52  749.59439.1206  886.59  435.88  1158.7  438.24
  1166.7  437.46  1198.7  425.06  1206.7   424.7 1288.57425.1295  1290.6   425.5
  1298.6  433.68 1310.08439.3859  1338.5  458.56  1354.5  466.32  1386.5  475.12
  1410.5  479.07  1514.3  490.74  1717.8   497.8  1733.8  496.54  1757.8  498.85
#Mann= 11 ,-1 , 0
       0     .12       0  182.13    .016       0  225.89     .06       0
  270.43     .12       0  383.56     .06       0  438.94     .12       0
  749.59     .08       0  886.59     .12       0  1198.7    .045       0
 1288.57     .04       0 1310.08     .12       0
Bank Sta=1198.7,1288.57
XS Rating Curve= 0 ,0
Exp/Cntr=0.3,0.1

Type RM Length L Ch R = 1 ,78363.5 ,722.9,723.1,722.7
XS GIS Cut Line= 2
     2376352.077      367648.899     2377242.702      368831.191
#Sta/Elev= 30
       0  481.95      20   480.5   63.09470.9078   107.7  464.91     161  460.29
  194.21456.7948   239.4  449.69  310.71443.5596   420.2441.3975  552.71438.7094
   730.1  436.26   909.7   436.8   949.6  438.36   953.6  436.45   961.5  425.94
  963.63425.2903   969.5   424.7 1045.36424.8063 1068.06427.4034  1101.2  428.41
  1113.2  433.96  1137.1  438.34    1161  439.98  1212.9  439.11  1236.8  441.44
  1252.8  446.55  1308.6  472.94  1332.6  477.85 1351.31479.5393  1480.2  483.17
#Mann= 11 ,-1 , 0
       0     .12       0   63.09     .06       0     161     .12       0
  194.21     .06       0  310.71     .12       0   420.2     .08       0
  552.71     .12       0  963.63    .045       0 1045.36     .04       0
 1068.06     .12       0 1351.31     .06       0
Bank Sta=963.63,1045.36
XS Rating Curve= 0 ,0
Exp/Cntr=0.3,0.1

Type RM Length L Ch R = 1 ,77640.4 ,466.5,460,454
XS GIS Cut Line= 3
     2375956.244      368289.524     2376612.494      369159.316
     2376883.327      369154.107
#Sta/Elev= 30
       0   544.6      20   540.7    39.9  534.58    55.9  527.87   159.6  463.31
   171.6  454.14   191.6  441.18   203.6  434.23   207.5  433.12   227.5  432.04
   291.4  434.15     463  435.16     475  434.27  505.14424.9724   510.9  424.54
  591.52424.9922   606.7  430.14   618.5 430.396   642.6  427.29   654.6  430.41
   670.5  437.55   708.4   436.8  756.96438.0061  794.18446.5673  866.49448.9398
  915.32450.7062  1137.4  459.64  1213.1  464.83  1296.7  474.81  1360.5  477.73
#Mann= 9 ,-1 , 0
       0     .12       0  505.14    .045       0  591.52     .04       0
   618.5     .12       0   708.4     .06       0  756.96     .12       0
  794.18     .06       0  866.49     .12       0  915.32     .06       0
Bank Sta=505.14,591.52
XS Rating Curve= 0 ,0
Exp/Cntr=0.3,0.1

Type RM Length L Ch R = 1 ,77180.4 ,507.5,489.5,471.3
XS GIS Cut Line= 3
     2375464.441       368555.55     2376294.785      369336.399
     2376379.957      369420.625
#Sta/Elev= 30
       0  576.31      32   579.8      80  574.87     140  558.33     168  547.07
     208  522.82     240     498     252  484.67     268  458.54     280  441.69
     288  434.24     296  431.01     308  430.22   439.9  438.35   531.9  438.08
   539.9  435.82   551.9  425.49   559.9  424.52   620.8 425.031  644.62429.0562
   691.9  431.96   728.2430.7758   783.9  433.63  892.67  435.51   923.9  438.09
   947.8  443.37  967.02444.5676  1087.8  455.69  1163.8  457.81  1259.6  457.36
#Mann= 7 ,-1 , 0
       0     .12       0   551.9    .045       0   620.8     .04       0
  644.62     .12       0   728.2     .06       0  892.67     .12       0
  967.02     .06       0
Bank Sta=551.9,620.8
XS Rating Curve= 0 ,0
Exp/Cntr=0.3,0.1