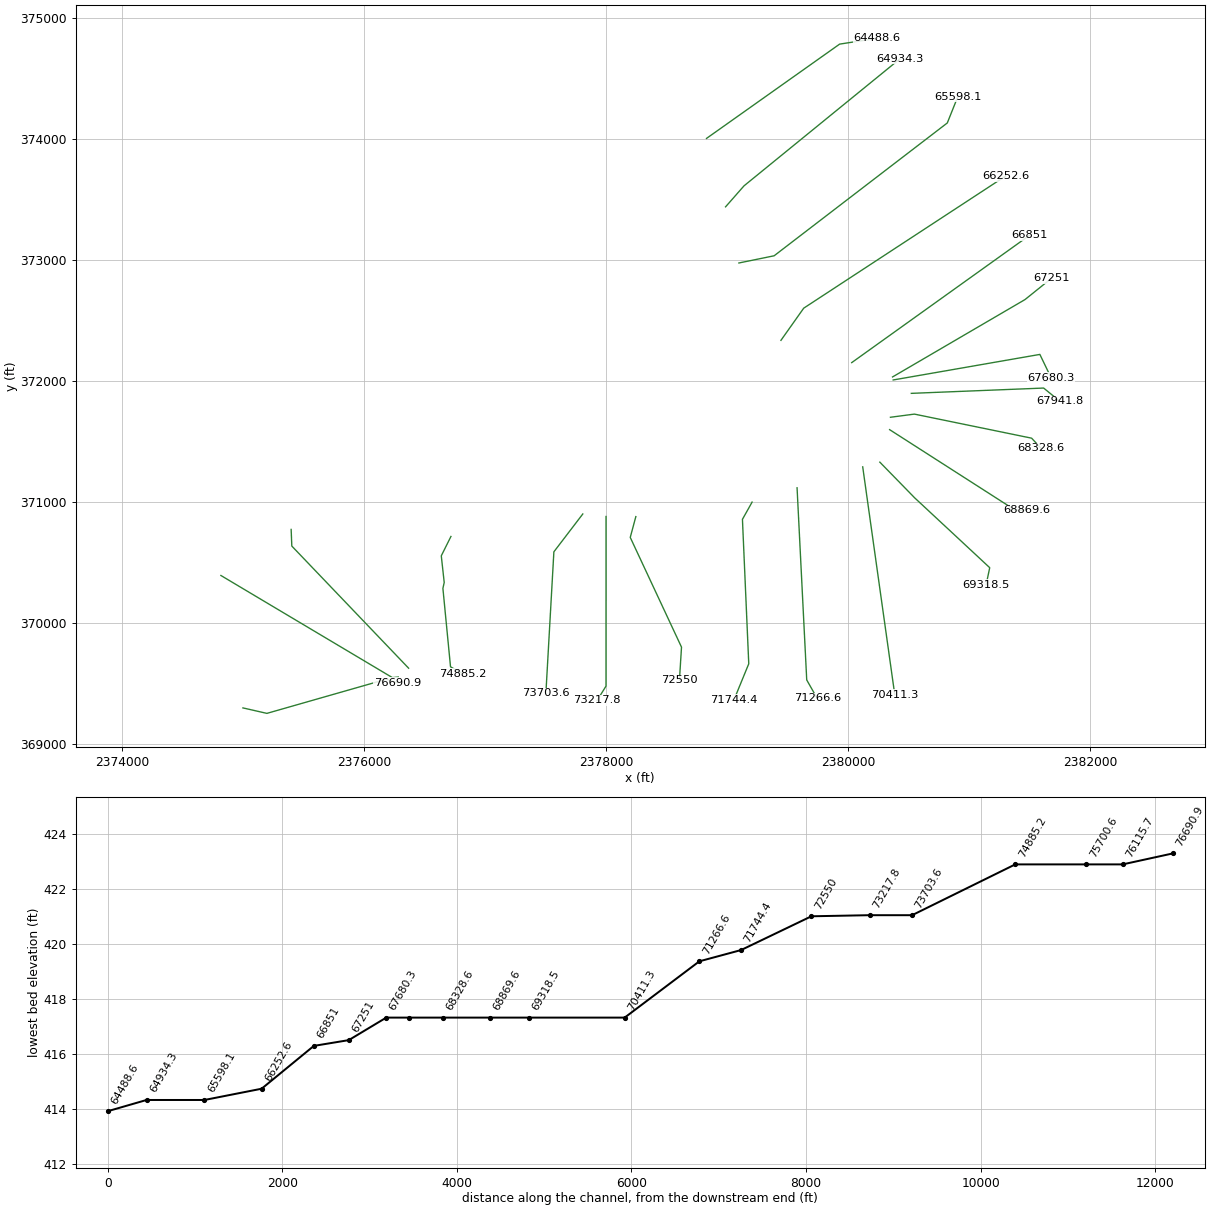
HEC-RAS study BACKCREEK.prj: BACKCREEK

--- BACKCREEK.g01 (geometry) --- (continued)

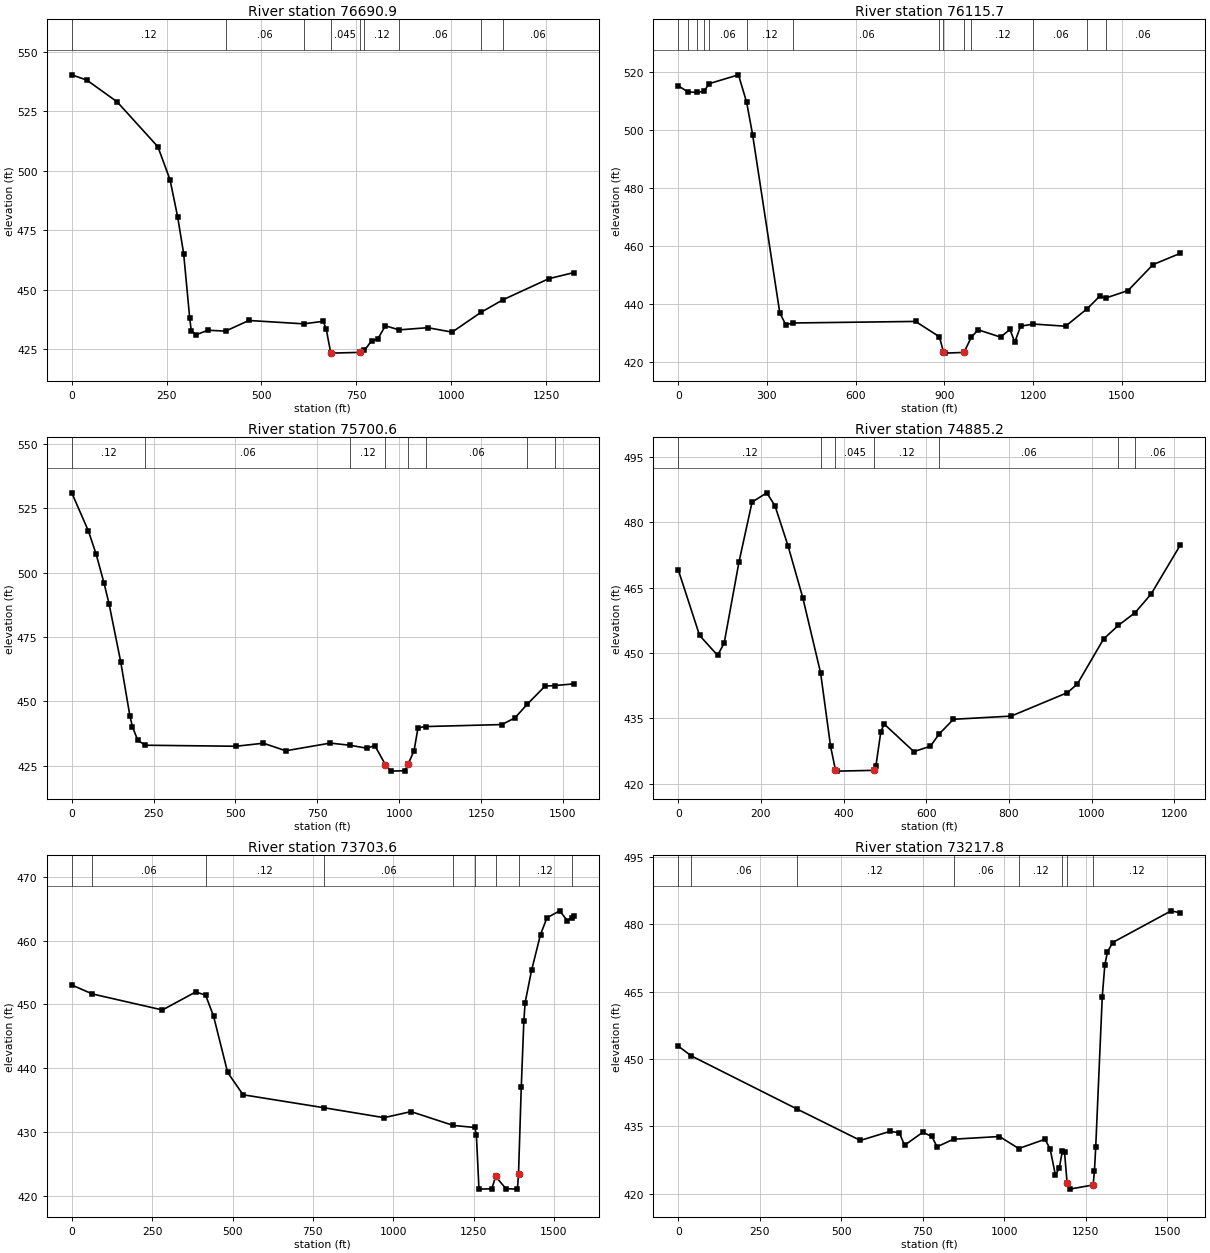
Type RM Length L Ch R = 1 ,76690.9 ,606.4,575.3,544.2
XS GIS Cut Line= 4
      2374997.91      369299.072     2375195.827      369253.934
     2376183.674      369536.052     2376272.216      369507.406
#Sta/Elev= 30
       0  540.26    39.8  538.03   119.4  528.93     227  510.03     259  496.15
     279  480.62   294.9  465.16   310.9  437.95   314.9  432.79   326.9  430.98
   358.9  432.91  405.45  432.56   466.8  437.02  611.08435.6105   662.7  436.67
   670.7  433.39  682.64423.3424   682.7   423.3   758.6  423.61  771.47424.4357
   790.6  428.58   806.6  429.24   826.6  434.78  863.01433.0823   938.5  433.99
  1002.5  432.12 1077.96440.3793 1136.04445.6805  1257.5  454.59  1323.4  457.15
#Mann= 9 ,-1 , 0
       0     .12       0  405.45     .06       0  611.08     .12       0
  682.64    .045       0   758.6     .04       0  771.47     .12       0
  863.01     .06       0 1077.96     .12       0 1136.04     .06       0
Bank Sta=682.64,758.6
XS Rating Curve= 0 ,0
Exp/Cntr=0.3,0.1

Type RM Length L Ch R = 1 ,76115.7 ,424.1,415.1,405.9
XS GIS Cut Line= 3
     2374815.779      370392.645     2376233.153      369549.072
     2376281.764      369554.281
#Sta/Elev= 30
       0  515.18    32.7513.0585   64.61512.8771   86.85513.3059  105.73515.9437
   203.7  518.96  231.22509.5576   251.6  498.29   343.5  436.78   363.4  432.76
  389.65433.3056   802.7  433.84  883.33428.5415  897.14423.3488   902.6   422.9
   966.5  423.15  991.71428.4417  1014.4  430.96  1090.3  428.43  1122.2  431.09
  1138.2  426.65  1158.2   432.2 1201.45  432.94    1310  432.19 1383.71438.2631
  1425.8  442.55 1445.39441.8969  1521.6   444.5  1605.5  453.42  1698.3  457.36
#Mann= 14 ,-1 , 0
       0     .08       0    32.7     .12       0   64.61     .08       0
   86.85     .12       0  105.73     .06       0  231.22     .12       0
  389.65     .06       0  883.33     .12       0  897.14    .045       0
   966.5     .04       0  991.71     .12       0 1201.45     .06       0
 1383.71     .12       0 1445.39     .06       0
Bank Sta=897.14,966.5
XS Rating Curve= 0 ,0
Exp/Cntr=0.3,0.1

Type RM Length L Ch R = 1 ,75700.6 ,846.9,815.4,784.5
XS GIS Cut Line= 3
     2375396.348      370773.031     2375401.717        370635.7
     2376366.834      369627.197
#Sta/Elev= 30
       0     531      51   516.1    74.6   507.1    98.2  496.09   113.9  487.84
   149.4   465.4   177.4  444.42   185.4  440.07   201.4  434.94  224.02  432.96
   501.4  432.56   585.4  433.74   653.4   430.8   789.4  433.79     851 432.922
   901.4  431.79   925.4  432.82  957.73425.4542   973.4   422.9  1017.4  423.06
 1027.74425.7235  1045.4  430.88  1057.4  439.75 1080.98440.2148  1313.4  440.99
  1353.4  443.57 1391.15 448.913  1445.3  455.91 1474.44456.1385  1533.3  456.79
#Mann= 8 ,-1 , 0
       0     .12       0  224.02     .06       0     851     .12       0
  957.73    .045       0 1027.74     .12       0 1080.98     .06       0
 1391.15     .12       0 1474.44     .06       0
Bank Sta=957.73,1027.74
XS Rating Curve= 0 ,0
Exp/Cntr=0.3,0.1

Type RM Length L Ch R = 1 ,74885.2 ,1180.9,1181.6,1181.4
XS GIS Cut Line= 6
     2376716.763      370714.896     2376636.902      370555.173
     2376661.135      370334.889     2376650.284      370286.061
     2376713.291      369638.507      2376811.97      369582.022
#Sta/Elev= 30
       0  469.07    51.6  454.03    95.2  449.45   111.1  452.26   146.8  470.79
   178.6   484.6   214.2  486.72     234  483.76   265.6  474.56   301.2   462.7
  344.38445.4258   368.5   428.6   380.4  423.12   384.4   422.9   474.2  423.08
   478.2  424.13   490.1  431.94   498.1   433.7     570  427.37   609.9  428.61
  631.54431.4545   665.8  434.79   805.4  435.52   941.2  440.89   965.1  442.83
    1029  453.22 1064.35 456.297 1105.28459.2506    1144  463.53  1214.5  474.74
#Mann= 7 ,-1 , 0
       0     .12       0  344.38     .04       0   380.4    .045       0
   474.2     .12       0  631.54     .06       0 1064.35     .12       0
 1105.28     .06       0
Bank Sta=380.4,474.2
XS Rating Curve= 0 ,0
Exp/Cntr=0.3,0.1

Type RM Length L Ch R = 1 ,73703.6 ,483.8,485.9,488
XS GIS Cut Line= 3
     2377806.231      370900.457     2377567.355      370588.135
     2377501.382      369421.468
#Sta/Elev= 30
       0  453.04   64.08451.6414     282  449.13   385.3  451.95  416.24451.4645
   441.1  448.15   484.9  439.33   532.8  435.84  785.36433.7996   971.5  432.25
  1055.2   433.2 1186.75  431.03 1253.91 430.711  1258.6  429.47  1266.6  421.05
  1306.5   421.1  1318.4  423.04  1350.4  421.12  1386.2  421.05 1389.57423.4174
  1398.2  437.09  1406.2  447.44  1410.2  450.29  1430.1  455.33    1458  460.95
    1478  463.58  1517.9  464.67  1541.8   463.1 1554.92463.5973  1561.7   463.9
#Mann= 9 ,-1 , 0
       0     .12       0   64.08     .06       0  416.24     .12       0
  785.36     .06       0 1186.75     .12       0 1253.91     .04       0
  1318.4    .045       0 1389.57     .12       0 1554.92     .06       0
Bank Sta=1318.4,1389.57
XS Rating Curve= 0 ,0
Exp/Cntr=0.3,0.1

Type RM Length L Ch R = 1 ,73217.8 ,651.4,667.8,684.2
XS GIS Cut Line= 3
      2377998.36      370879.826     2377998.054      369479.102
     2377924.442      369360.306
#Sta/Elev= 30
       0  452.88   39.94450.7085  364.46438.8803   558.7  431.89   650.5  433.92
   678.4  433.58   694.4  430.81   750.2   433.7   778.2  432.77   794.1  430.47
  844.61 432.163   985.7  432.76  1044.7430.0818  1125.4  432.15  1141.3  429.93
  1157.3  424.16  1169.3   425.8 1178.94429.6319  1185.2  429.31  1193.2   422.4
  1201.2  421.05    1273  421.98    1277  425.04    1281  430.48    1301  463.87
  1308.9  470.94  1316.9  473.81  1332.9  475.94  1512.5  482.99  1540.5  482.53
#Mann= 8 ,-1 , 0
       0     .12       0   39.94     .06       0  364.46     .12       0
  844.61     .06       0  1044.7     .12       0 1178.94     .04       0
  1193.2    .045       0    1273     .12       0
Bank Sta=1193.2,1273
XS Rating Curve= 0 ,0
Exp/Cntr=0.3,0.1

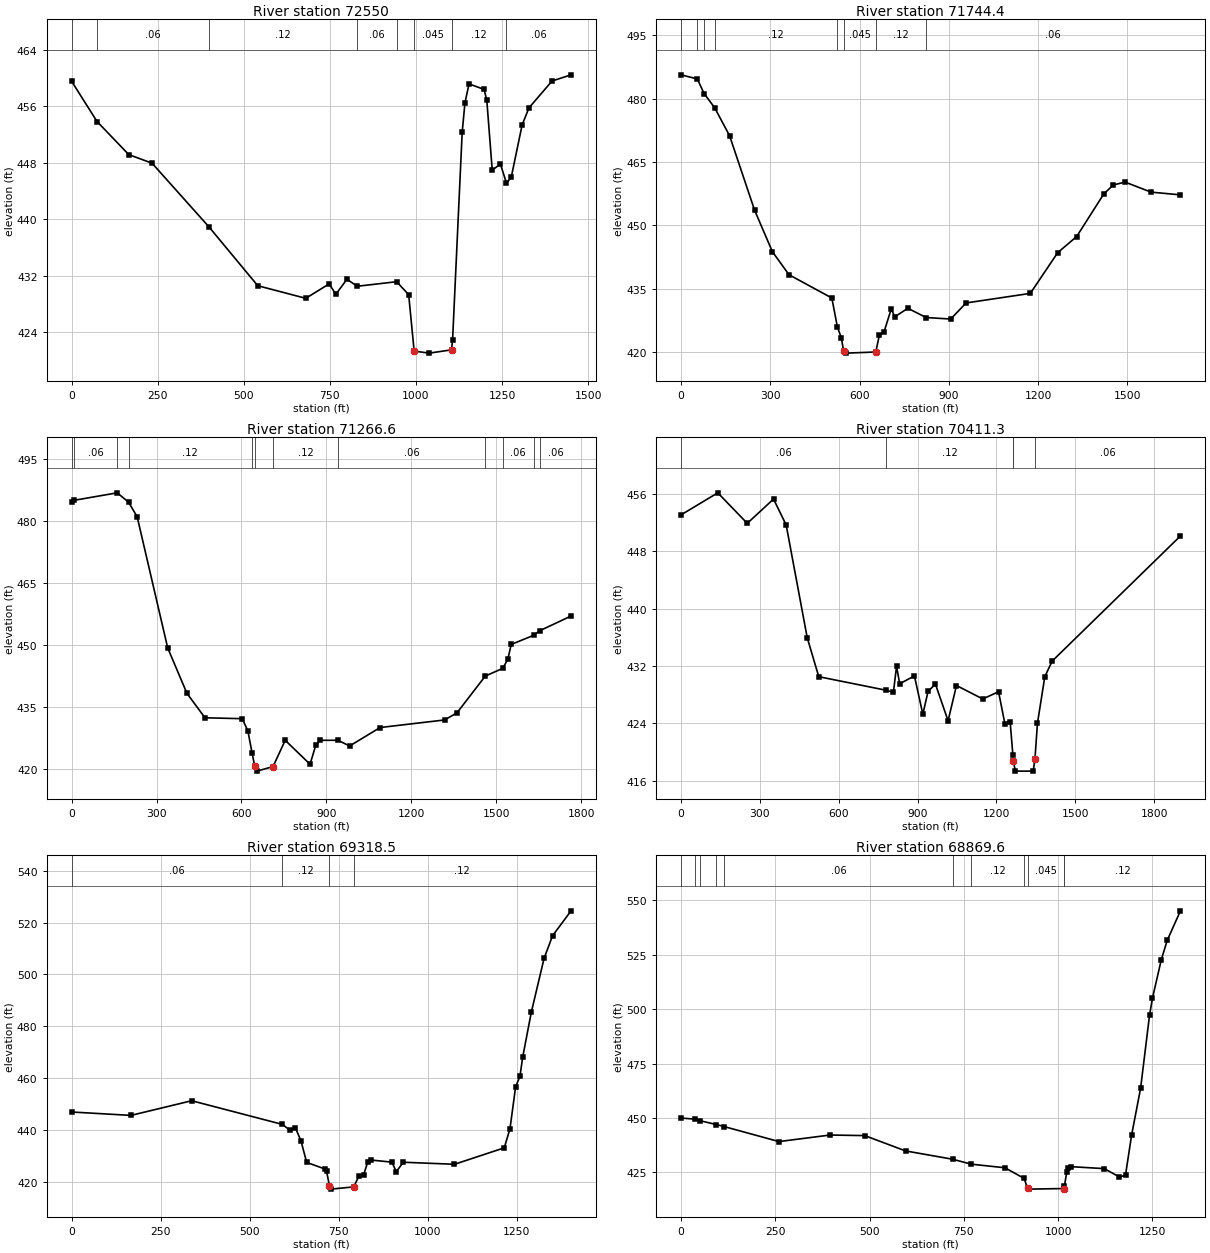
Type RM Length L Ch R = 1 ,72550   ,820.7,805.5,790.4
XS GIS Cut Line= 4
     2378244.599      370878.756     2378198.431      370707.059
     2378622.042      369800.809     2378604.842      369528.929
#Sta/Elev= 30
       0  459.55   73.79 453.849   165.9  449.16   233.6  447.94   399.1438.8943
   540.5  430.57     680  428.78   747.7  430.82   767.6  429.36   799.5  431.48
  829.58430.4918  943.92431.1372   978.9   429.3   994.8   421.3  1038.7  421.01
 1103.36421.4768  1106.4  422.86  1134.3   452.3  1142.3  456.48  1154.2  459.19
  1197.9   458.4  1205.8  456.88  1221.6  446.95  1245.3  447.82 1262.99445.1112
  1276.9  445.96  1308.4  453.36  1328.2  455.78  1395.3  459.59  1450.6  460.47
#Mann= 8 ,-1 , 0
       0     .12       0   73.79     .06       0   399.1     .12       0
  829.58     .06       0  943.92     .12       0   994.8    .045       0
 1103.36     .12       0 1262.99     .06       0
Bank Sta=994.8,1103.36
XS Rating Curve= 0 ,0
Exp/Cntr=0.3,0.1

Type RM Length L Ch R = 1 ,71744.4 ,476.2,477.8,479.4
XS GIS Cut Line= 4
     2379205.375      370998.725     2379125.514      370856.364
     2379177.758      369663.478      2379056.07      369366.781
#Sta/Elev= 30
       0   485.6   54.81484.6291   77.64481.1672  113.05477.8173   163.2   471.2
   247.1   453.6     307  443.77   362.9  438.32   506.7  432.82  525.39425.9602
   538.6  423.39   546.6  420.19   554.6  419.78   654.4  420.05   666.4  424.04
   682.4  424.88   706.3  430.21   718.3  428.37   762.2  430.39  823.33428.1992
     906  427.84   957.9  431.65  1173.6  433.91  1265.4  443.53  1329.3  447.36
  1420.6  457.45  1452.3  459.55  1491.9  460.23    1579  457.86  1677.9  457.21
#Mann= 8 ,-1 , 0
       0     .06       0   54.81     .12       0   77.64     .06       0
  113.05     .12       0  525.39     .04       0   546.6    .045       0
   654.4     .12       0  823.33     .06       0
Bank Sta=546.6,654.4
XS Rating Curve= 0 ,0
Exp/Cntr=0.3,0.1

Type RM Length L Ch R = 1 ,71266.6 ,853,855.4,857.4
XS GIS Cut Line= 3
     2379576.903      371116.781     2379656.764      369529.975
      2379743.57      369377.197
#Sta/Elev= 30
       0  484.49    8.09484.8952  160.99486.7142  200.99484.4653   231.5  480.92
   339.3   449.2   407.2  438.21   471.1  432.28   602.8  432.06   622.8  429.06
  637.58423.7064   646.7  420.66   654.7  419.37   711.6420.4725   754.5  426.83
   842.3  421.04   862.3  425.58   878.2  426.83  941.08426.8323     982  425.45
  1089.8  429.92  1317.4  431.75  1361.3  433.46 1461.41 442.374  1522.7444.2223
  1540.9  446.39  1552.9  450.02 1632.82452.2509 1653.35453.3335  1764.5   456.9
#Mann= 12 ,-1 , 0
       0     .12       0    8.09     .06       0  160.99     .08       0
  200.99     .12       0  637.58     .04       0   646.7    .045       0
   711.6     .12       0  941.08     .06       0 1461.41     .08       0
  1522.7     .06       0 1632.82     .12       0 1653.35     .06       0
Bank Sta=646.7,711.6
XS Rating Curve= 0 ,0
Exp/Cntr=0.3,0.1

Type RM Length L Ch R = 1 ,70411.3 ,1066.8,1092.8,1118.2
XS GIS Cut Line= 2
     2380119.373      371289.708     2380384.195      369408.447
#Sta/Elev= 30
       0  453.08     140  456.16     252   451.9     352  455.29     400  451.68
     480  435.96     524   430.5  781.64428.5974   807.9  428.31   819.9  431.94
   831.9  429.51   887.9  430.61   919.9  425.26   939.9  428.47   967.9  429.46
  1015.9  424.35  1047.9  429.27  1147.9  427.39  1207.9   428.4  1231.9  423.95
  1251.9  424.24 1262.54419.5048  1263.9  418.75  1271.9  417.32  1339.9  417.32
 1346.39419.0435  1355.9     424  1383.9   430.5  1411.9  432.68  1899.8  450.14
#Mann= 5 ,-1 , 0
       0     .06       0  781.64     .12       0 1262.54     .04       0
  1263.9    .045       0 1346.39     .06       0
Bank Sta=1263.9,1346.39
XS Rating Curve= 0 ,0
Exp/Cntr=0.3,0.1

Type RM Length L Ch R = 1 ,69318.5 ,442.1,448.9,455.7
XS GIS Cut Line= 4
     2380260.931      371328.586     2380549.125      371033.447
     2381168.917      370457.059     2381139.403      370316.434
#Sta/Elev= 30
       0  447.03   166.6  445.72   337.2  451.37  591.62442.2578   612.1  440.12
   628.1  441.03   644.1  435.91     660  427.62   711.9  425.05   715.9  424.25
   723.9  418.65   727.9  417.32   791.8  418.17   807.8  422.55   819.7  422.73
   831.7  427.82   839.7  428.54   899.6  427.71   911.6  424.03   931.5  427.68
  1075.2  426.89    1215  433.23    1231  440.56  1246.9   456.8  1258.9  460.71
  1266.9  468.29  1290.8  485.38  1326.8  506.23  1350.7  514.95  1402.6  524.52
#Mann= 4 ,-1 , 0
       0     .06       0  591.62     .12       0   723.9    .045       0
   791.8     .12       0
Bank Sta=723.9,791.8
XS Rating Curve= 0 ,0
Exp/Cntr=0.3,0.1

Type RM Length L Ch R = 1 ,68869.6 ,527.3,541,554.8
XS GIS Cut Line= 3
     2380341.834      371596.902     2381378.292       370932.84
     2381472.042      370930.236
#Sta/Elev= 30
       0  449.98   37.56449.4449   49.97448.7673    93.7 446.993     115446.0225
   259.8  439.16   395.7  442.17   487.6   441.9   595.5  434.87  720.42431.0522
  769.84428.7828   859.3  427.13  909.91422.2606   919.2  417.73   923.2  417.32
  1015.1  417.59 1017.16418.9856  1023.1  425.02  1027.1  426.98  1035.1  427.63
    1123  426.73    1163  422.87    1179  423.77    1195  441.98    1219  463.62
  1242.7  497.17  1250.5  505.04  1273.9  522.68  1289.6  531.56  1324.7  545.14
#Mann= 11 ,-1 , 0
       0     .12       0   37.56     .08       0   49.97     .06       0
    93.7     .08       0     115     .06       0  720.42    .016       0
  769.84     .12       0  909.91     .04       0   919.2    .045       0
  1015.1     .04       0 1017.16     .12       0
#XS Ineff= 2 , 0
       0     435                       0
Permanent Ineff=
       F       F
Bank Sta=919.2,1015.1
XS Rating Curve= 0 ,0
Exp/Cntr=0.3,0.1

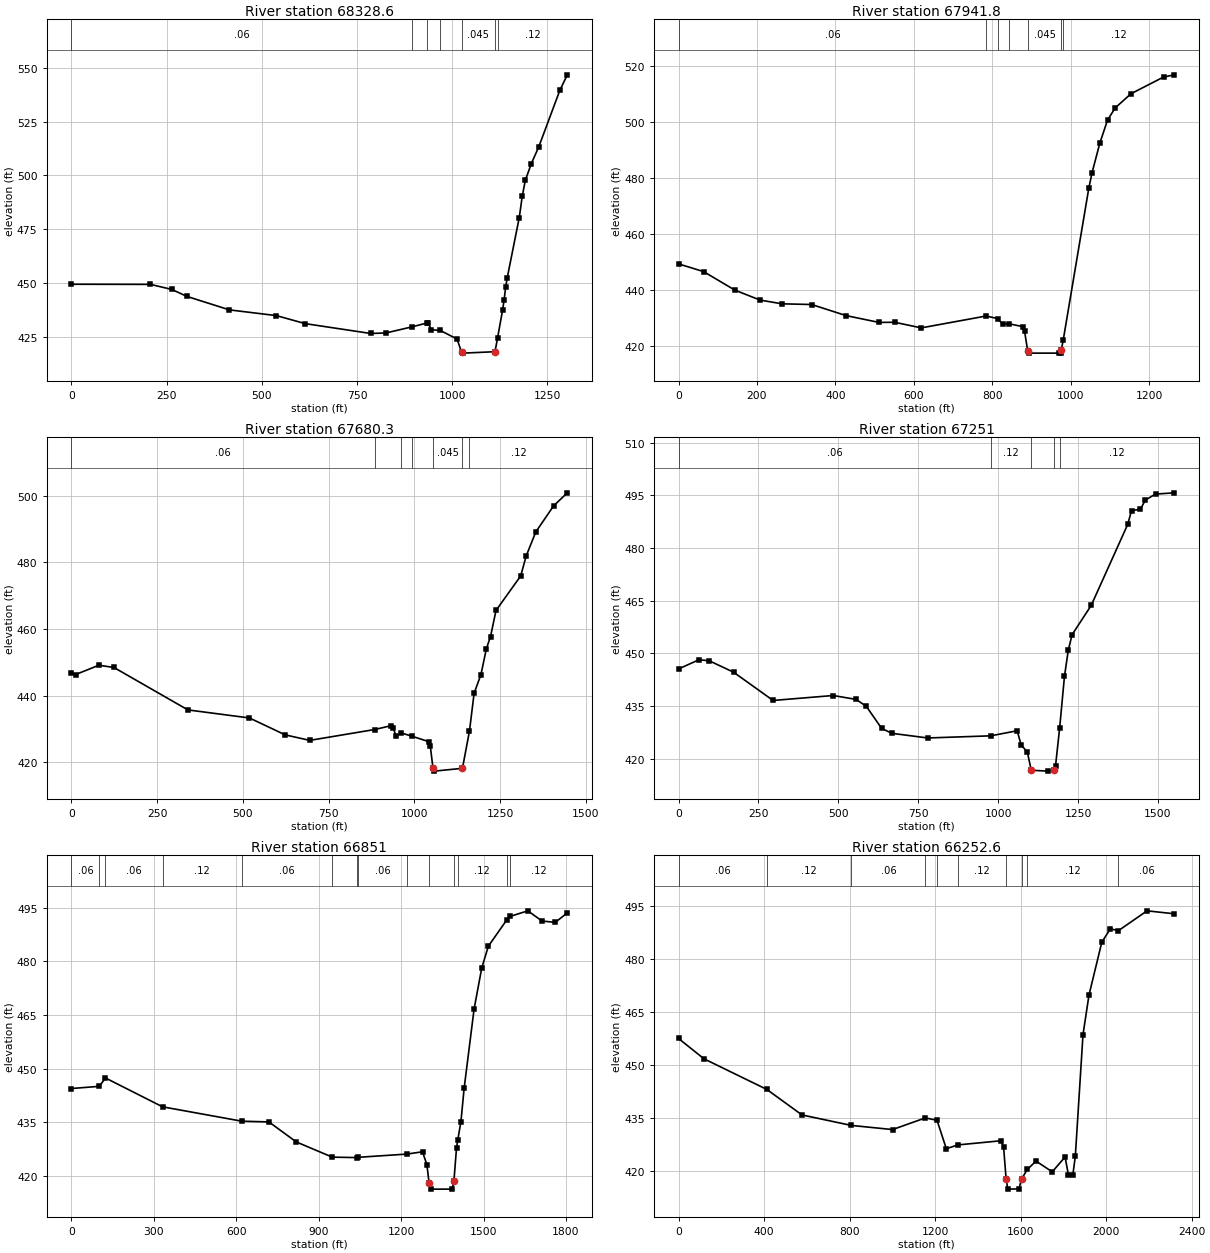
Type RM Length L Ch R = 1 ,68328.6 ,377.7,386.9,396
XS GIS Cut Line= 4
     2380348.605      371699.246     2380546.521      371725.288
     2381515.011       371526.59     2381593.136      371443.256
#Sta/Elev= 30
       0  449.35   207.6  449.28   263.4  446.94   303.3  443.69   414.9  437.43
   538.5  434.76   614.2  431.03   785.6  426.47   825.5  426.68  895.14429.5556
  934.68431.3772   937.1  431.34   945.1  428.19  968.52427.8752  1012.9  423.88
  1024.8   417.7  1028.8  417.32  1112.5  417.98 1119.12424.1942  1132.5  437.39
  1136.5  442.02  1140.4  447.88  1144.4  452.09  1176.3  480.37  1184.3  490.49
  1192.2  497.65    1208  505.46  1227.7  513.31  1282.8  539.48  1302.5  546.72
#Mann= 7 ,-1 , 0
       0     .06       0  895.14     .12       0  934.68    .016       0
  968.52     .12       0  1024.8    .045       0  1112.5     .04       0
 1119.12     .12       0
Bank Sta=1024.8,1112.5
XS Rating Curve= 0 ,0
Exp/Cntr=0.3,0.1

Type RM Length L Ch R = 1 ,67941.8 ,256.5,261.4,266.4
XS GIS Cut Line= 3
     2380521.127       371896.64      2381614.56      371940.401
     2381746.504      371832.762
#Sta/Elev= 30
       0  449.28    63.9  446.52   143.8  439.87   207.7  436.33   263.6  434.98
   339.5  434.73   427.3  430.76   511.2  428.32   551.2  428.37     619  426.36
  784.43  430.61  813.99429.6891   826.7  427.68  842.16427.8568   878.6  426.79
   882.6   425.1   890.6  417.98   894.6  417.32   970.5  417.32   974.5  417.51
  976.05418.4284  980.91421.8502  1046.4  476.46  1054.4   481.8  1074.3  492.47
  1094.3  500.87  1114.1   505.2  1153.7   510.2  1236.9   516.2  1264.6  516.99
#Mann= 7 ,-1 , 0
       0     .06       0  784.43     .12       0  813.99    .016       0
  842.16     .12       0   890.6    .045       0  976.05     .04       0
  980.91     .12       0
Bank Sta=890.6,976.05
XS Rating Curve= 0 ,0
Exp/Cntr=0.3,0.1

Type RM Length L Ch R = 1 ,67680.3 ,415.9,429.4,442.8
XS GIS Cut Line= 3
     2380371.335      372007.228      2381583.31      372218.178
      2381677.06      372023.734
#Sta/Elev= 30
       0  446.76      12  446.31    79.9  449.11   123.8  448.44   339.5   435.7
   519.2  433.28   623.1  428.21     695  426.55  883.99429.8058   930.6  430.92
   938.6   430.2   946.6  427.82   961.2428.8015  992.55  427.82  1042.5  426.15
  1046.5  424.84  1054.4  418.18  1058.4  417.32  1140.3  418.17 1160.83429.3951
  1174.3   440.7  1194.2   446.3  1210.2  454.12  1222.2  457.73  1238.2  465.57
  1310.2  475.92  1326.1   481.9  1354.1  489.11  1406.1  496.95  1446.1  500.87
#Mann= 7 ,-1 , 0
       0     .06       0  883.99     .12       0   961.2    .016       0
  992.55     .12       0  1054.4    .045       0  1140.3     .04       0
 1160.83     .12       0
Bank Sta=1054.4,1140.3
XS Rating Curve= 0 ,0
Exp/Cntr=0.3,0.1

Type RM Length L Ch R = 1 ,67251   ,396.5,400,403.4
XS GIS Cut Line= 3
     2380366.012      372032.183     2381460.744       372671.29
     2381682.099      372849.242
#Sta/Elev= 30
       0  445.59      64  448.22      96  447.92     172  444.68   295.9  436.62
   483.9  438.03   555.8  436.92   587.8  434.92   635.8  428.64   667.8  427.26
   779.8  425.94  977.12426.5507  1059.7     428  1071.7  424.05  1091.7  421.84
  1103.7  416.75  1155.7   416.5 1175.85416.7014  1179.7  418.02  1192.7428.9008
  1207.6  443.47  1219.6  450.94  1231.6  455.37  1291.3  463.68  1405.7  486.78
  1417.5   490.7  1445.1  491.03  1460.9   493.7  1492.5  495.38  1551.6  495.74
#Mann= 5 ,-1 , 0
       0     .06       0  977.12     .12       0  1103.7    .045       0
 1175.85     .04       0  1192.7     .12       0
Bank Sta=1103.7,1175.85
XS Rating Curve= 0 ,0
Exp/Cntr=0.3,0.1

Type RM Length L Ch R = 1 ,66851   ,600.4,598.4,596.3
XS GIS Cut Line= 2
     2380028.453      372150.457     2381496.504      373200.817
#Sta/Elev= 30
       0  444.45  101.73445.0599  123.57447.4126  331.67439.3257  620.22435.3022
   718.8   435.1   818.7  429.49  949.53425.2409 1037.76425.1182 1042.08425.1862
 1221.23426.0992    1278  426.74  1293.9  423.13  1301.9  418.04  1309.9  416.29
  1385.8  416.29 1392.21418.4512  1401.8  427.86    1406429.9171  1417.7  435.11
  1429.7  444.64  1465.7  466.68  1493.6  478.18  1517.6  484.27 1583.98491.5685
 1596.22492.6007  1661.3  494.18  1713.3  491.32  1761.2  490.95  1805.1   493.6
#Mann= 14 ,-1 , 0
       0     .06       0  101.73     .12       0  123.57     .06       0
  331.67     .12       0  620.22     .06       0  949.53     .07       0
 1037.76     .08       0 1042.08     .06       0 1221.23     .12       0
  1301.9    .045       0 1392.21     .04       0    1406     .12       0
 1583.98     .06       0 1596.22     .12       0
Bank Sta=1301.9,1392.21
XS Rating Curve= 0 ,0
Exp/Cntr=0.3,0.1

Type RM Length L Ch R = 1 ,66252.6 ,651.8,654.5,657.2
XS GIS Cut Line= 3
     2379443.673      372334.398     2379631.921      372600.123
     2381300.154      373691.256
#Sta/Elev= 30
       0  457.37   119.1  451.62   412.9442.9505   577.3  435.73  808.52 432.759
  1000.8  431.59 1154.37434.8935 1208.87434.2144  1252.4  426.16 1305.69427.2432
  1508.1  428.42  1520.1  426.73  1532.1  417.55    1540  414.73    1592   414.8
    1604  417.54 1630.76420.2871  1671.9  422.66  1747.8  419.63  1807.7  423.83
  1823.7  418.68  1843.7  418.59  1855.6  423.98  1891.6  458.47  1919.6  469.67
  1979.5  484.63  2019.4  488.41 2057.09487.8931  2191.2  493.51    2319  492.67
#Mann= 10 ,-1 , 0
       0     .06       0   412.9     .12       0  808.52     .06       0
 1154.37     .12       0 1208.87     .08       0 1305.69     .12       0
  1532.1    .045       0    1604     .04       0 1630.76     .12       0
 2057.09     .06       0
Bank Sta=1532.1,1604
XS Rating Curve= 0 ,0
Exp/Cntr=0.3,0.1

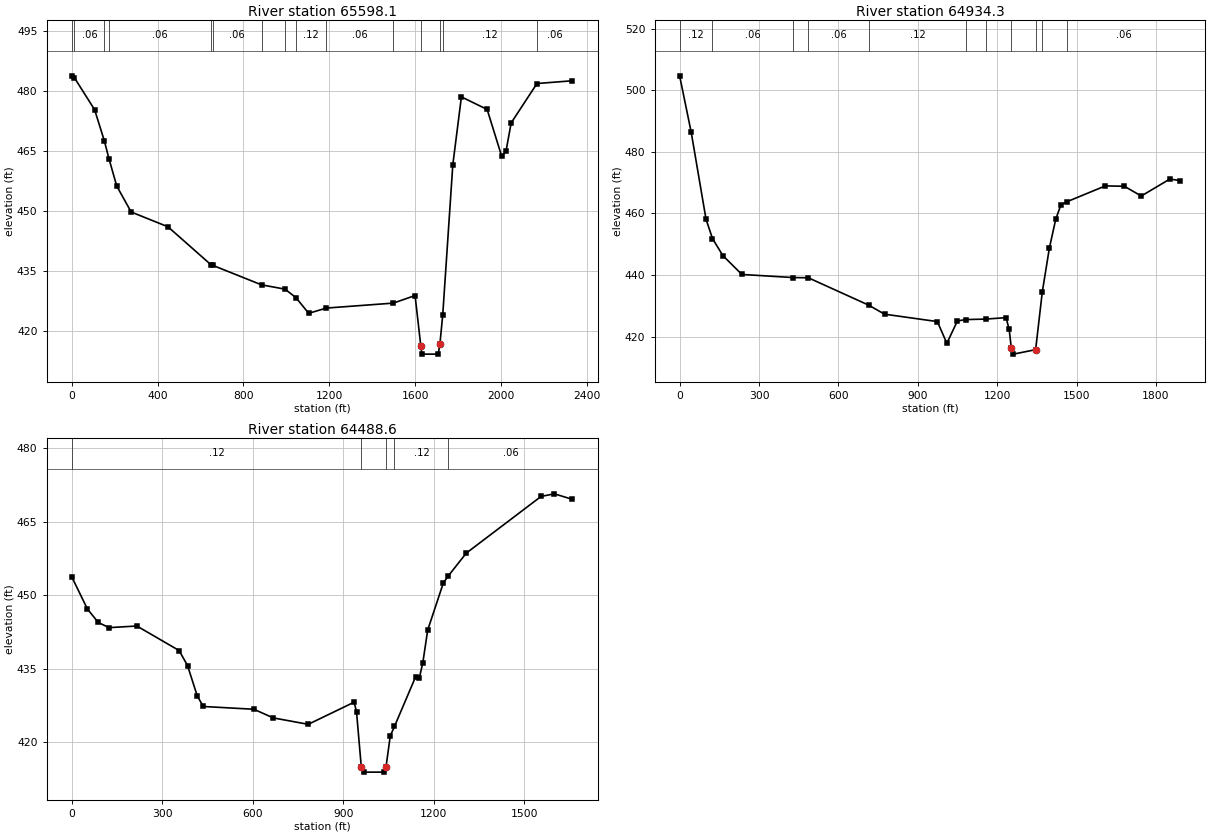
Type RM Length L Ch R = 1 ,65598.1 ,663.1,663.8,664.4
XS GIS Cut Line= 4
      2379096.45      372973.287     2379387.295      373032.663
     2380818.383      374129.624     2380905.189      374346.638
#Sta/Elev= 30
       0  483.79   12.29483.3417   106.9  475.32  151.93467.5862  174.05 463.022
   209.8  456.29     277   449.8   448.8   446.1  650.07436.5821  657.04436.4893
  884.84431.6106  993.81430.5459 1044.85428.4386  1104.5  424.51 1187.11425.8197
 1499.04427.0546  1600.2  428.95 1626.87416.3865  1632.2  414.32  1708.2  414.32
  1716.2  416.96  1729.2  424.18  1776.1   461.6  1816.1  478.53  1936.1   475.4
    2004  463.68    2024  464.98    2048  472.04  2168.3481.8675  2333.7  482.56
#Mann= 15 ,-1 , 0
       0     .08       0   12.29     .06       0  151.93     .12       0
  174.05     .06       0  650.07     .12       0  657.04     .06       0
  884.84     .12       0  993.81     .06       0 1044.85     .12       0
 1187.11     .06       0 1499.04     .12       0 1626.87    .045       0
  1716.2     .04       0  1729.2     .12       0  2168.3     .06       0
Bank Sta=1626.87,1716.2
XS Rating Curve= 0 ,0
Exp/Cntr=0.3,0.1

Type RM Length L Ch R = 1 ,64934.3 ,447.9,445.7,443.5
XS GIS Cut Line= 3
     2378986.087      373436.928     2379138.865      373610.539
      2380427.06      374659.151
#Sta/Elev= 30
       0  504.72    43.9  486.33    99.7  458.18  124.14451.8619   163.5  446.33
   235.2   440.2  429.26439.1918  486.52439.1158  714.65430.2222   774.3   427.3
   973.9  424.89  1009.9  417.84  1049.8  425.12 1082.49425.5448 1157.07 425.704
  1233.5  426.17  1245.4  422.34  1253.4  416.26  1261.4  414.32  1345.3  415.77
 1370.45434.4912  1397.2  448.74  1421.1  458.06  1441.1  462.88 1464.06463.8386
  1608.8  468.97  1680.7  468.84  1744.6  465.68  1852.4  471.19  1892.3  470.67
#Mann= 11 ,-1 , 0
       0     .12       0  124.14     .06       0  429.26     .12       0
  486.52     .06       0  714.65     .12       0 1082.49     .06       0
 1157.07     .12       0  1253.4    .045       0  1345.3     .04       0
 1370.45     .12       0 1464.06     .06       0
Bank Sta=1253.4,1345.3
XS Rating Curve= 0 ,0
Exp/Cntr=0.3,0.1

Type RM Length L Ch R = 1 ,64488.6 ,515,504.5,494
XS GIS Cut Line= 3
     2378828.476      374001.836     2379928.626      374780.665
     2380236.786      374828.408
#Sta/Elev= 30
       0  453.76      52  447.19      88  444.43     124  443.38     216  443.71
     356  438.71     384  435.63     416  429.48     436   427.3     604  426.73
     668  424.97     784  423.66     936  428.17     944  426.24     960  414.86
     968  413.91  1035.9  413.91 1041.81414.9573  1055.9   421.3 1069.83 423.226
  1139.9  433.35  1151.9  433.04  1163.9  436.25  1179.9  442.87  1231.9  452.51
  1248.8453.9715  1307.9  458.58  1555.8  470.14  1599.8  470.67  1659.8  469.54
#Mann= 5 ,-1 , 0
       0     .12       0     960    .045       0 1041.81     .04       0
 1069.83     .12       0  1248.8     .06       0
Bank Sta=960,1041.81
XS Rating Curve= 0 ,0
Exp/Cntr=0.3,0.1