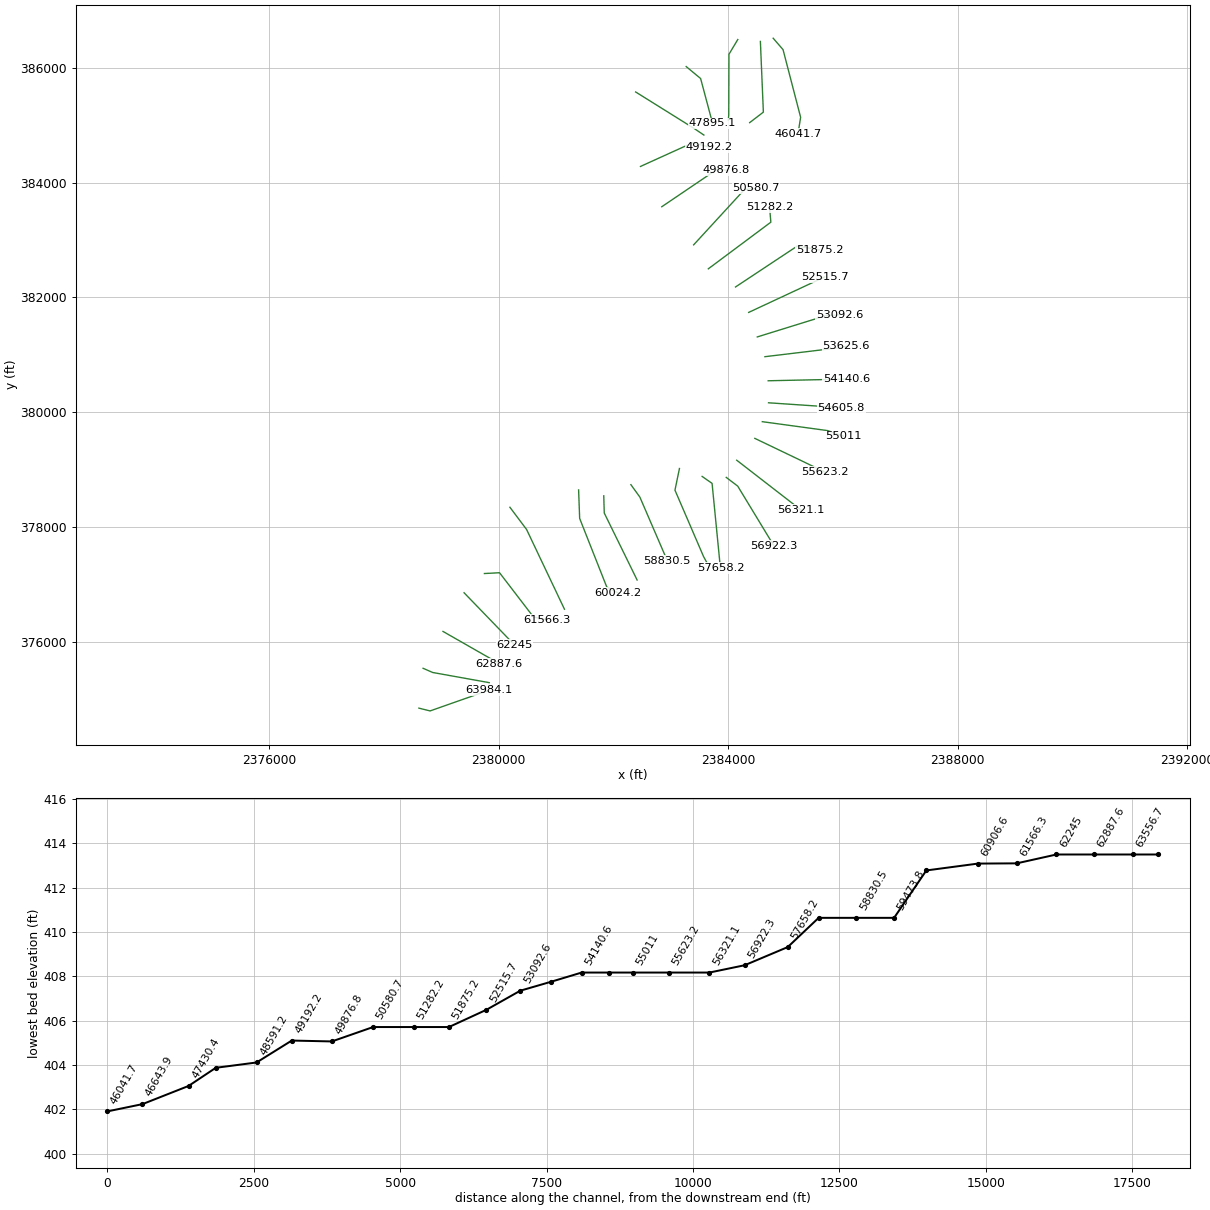
HEC-RAS study BACKCREEK.prj: BACKCREEK

--- BACKCREEK.g01 (geometry) --- (continued)

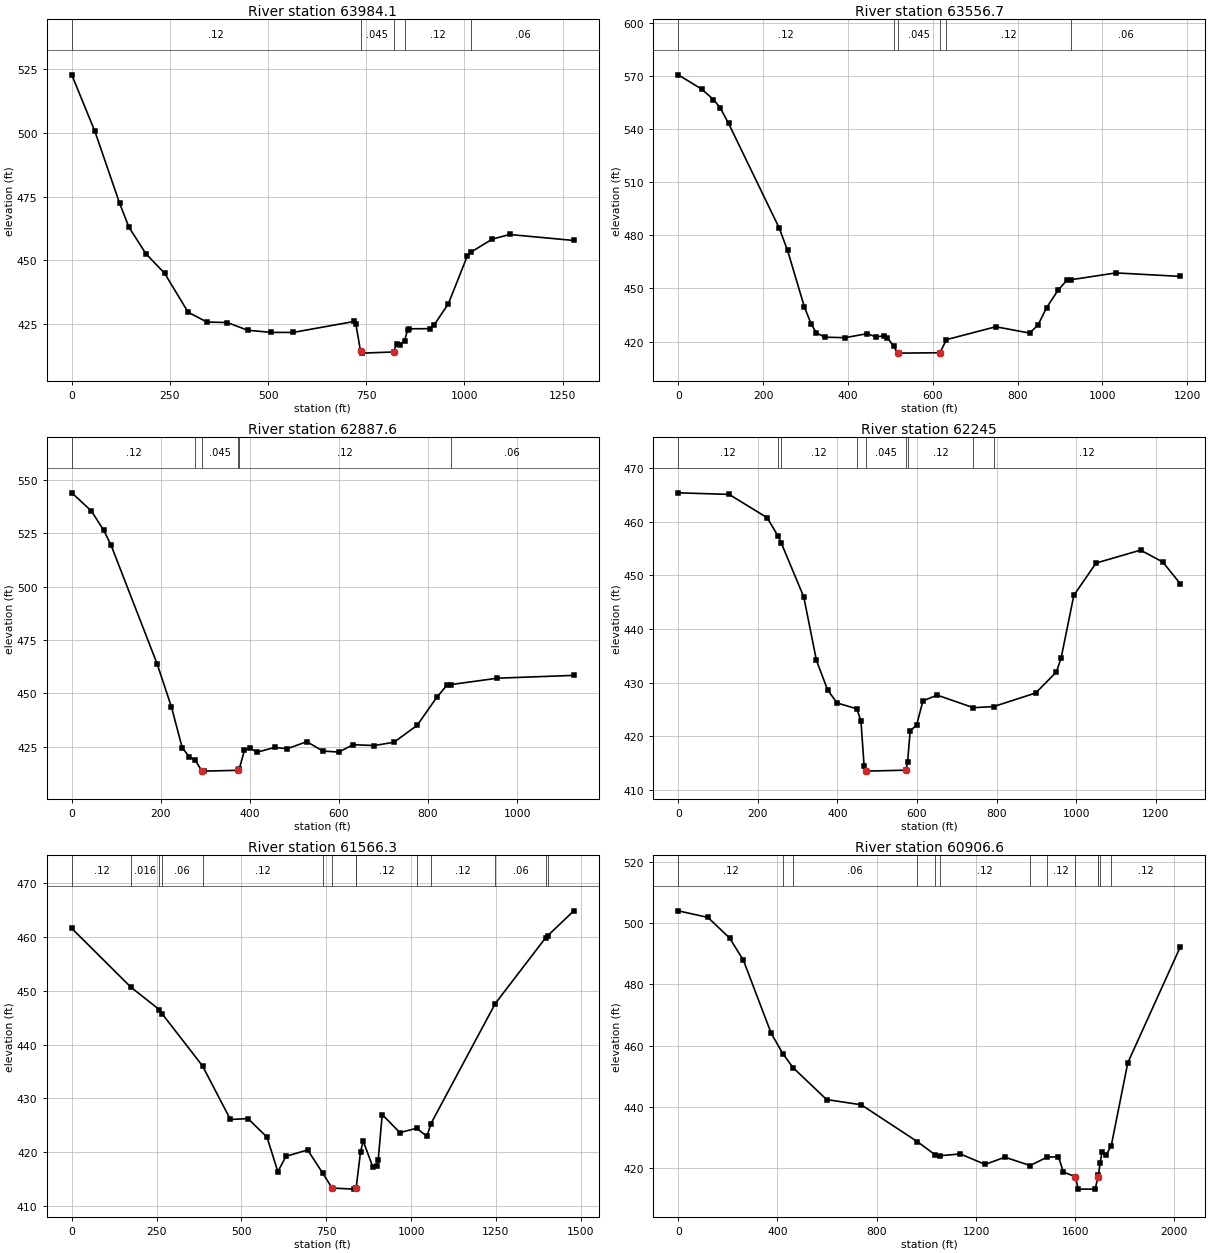
Type RM Length L Ch R = 1 ,63984.1 ,447.9,427.4,406.9
XS GIS Cut Line= 3
     2378607.615      374839.706      2378802.06      374791.095
     2379819.421      375148.734
#Sta/Elev= 30
       0   522.8      59  500.55   121.8  472.37   145.4  463.03   188.6  452.59
   236.4  444.87   296.3  429.58   344.2  425.71   396.1  425.51   448.1  422.49
     508  421.64   563.9  421.63   719.6  425.95   723.6  424.92   735.6  414.16
   739.6   413.5   819.5  413.95   827.5  417.18   835.5  416.75  847.69418.4288
   855.4   422.6   859.4  423.05   911.4  423.11   923.4  424.68   959.3  432.92
  1007.2  451.53 1016.56 453.155  1071.1  458.27  1115.1  460.09  1278.8  457.74
#Mann= 5 ,-1 , 0
       0     .12       0   735.6    .045       0   819.5     .04       0
  847.69     .12       0 1016.56     .06       0
Bank Sta=735.6,819.5
XS Rating Curve= 0 ,0
Exp/Cntr=0.3,0.1

Type RM Length L Ch R = 1 ,63556.7 ,680.8,669.1,657.4
XS GIS Cut Line= 3
     2378680.532      375534.151     2378847.198      375461.234
      2379833.31      375284.151
#Sta/Elev= 30
       0  570.62    55.4  562.52      83  556.66    98.9  552.03   118.6  543.22
   237.8  484.26   257.8  471.46   297.7  439.38   313.6  429.83   325.6  424.96
   345.6   422.5   393.5  422.23   445.4  424.49   465.3  422.73   485.3   423.2
   493.3  422.22  507.86417.3133   517.2   413.7   521.2   413.5     617  413.72
  632.45421.1103   748.7  428.39   828.6  424.82   848.5  429.46   868.5  439.17
   896.4  449.31   916.4  454.64  926.96454.9684  1032.1  458.79  1183.8  456.81
#Mann= 6 ,-1 , 0
       0     .12       0  507.86     .04       0   517.2    .045       0
     617     .04       0  632.45     .12       0  926.96     .06       0
Bank Sta=517.2,617
XS Rating Curve= 0 ,0
Exp/Cntr=0.3,0.1

Type RM Length L Ch R = 1 ,62887.6 ,653.4,642.6,631.9
XS GIS Cut Line= 2
     2379027.754      376176.512     2380006.921      375617.484
#Sta/Elev= 30
       0   543.9      44  535.42      72  526.25      88   519.5   191.9  463.63
   223.9  443.54   247.9  424.55   263.9  420.16  277.27418.5674   291.9  413.68
   295.9   413.5   373.7413.8905  376.23414.6075   387.8  423.26   399.8  424.38
   415.8  422.35   455.8  424.61   483.8  423.99   527.8   427.3   563.8  422.91
   599.7  422.43   631.7  425.87   679.7  425.49   723.7  427.05   775.7  434.97
   819.6  448.07   843.6  454.04  851.09454.0428   955.6  457.04  1127.5  458.37
#Mann= 6 ,-1 , 0
       0     .12       0  277.27     .04       0   291.9    .045       0
   373.7     .04       0  376.23     .12       0  851.09     .06       0
Bank Sta=291.9,373.7
XS Rating Curve= 0 ,0
Exp/Cntr=0.3,0.1

Type RM Length L Ch R = 1 ,62245   ,680.6,678.6,676.7
XS GIS Cut Line= 2
     2379394.772      376850.978     2380271.508       375943.86
#Sta/Elev= 30
       0  465.42   127.8  465.13   223.6  460.77  250.73457.3501  258.82456.0756
   315.4     446   347.3  434.15   375.3  428.66   399.2  426.21  448.85 425.125
   459.1  422.83   467.1  414.44  470.94413.5376   471.1   413.5  572.28413.6794
  576.32415.2234   582.9  421.07   598.8  422.02   614.8   426.6   650.7  427.68
  741.57425.3338  792.66425.5442   898.3  428.08   950.2  431.99   962.1   434.6
   994.1  446.31    1050  452.32  1161.8  454.73  1217.6  452.51  1261.6  448.45
#Mann= 9 ,-1 , 0
       0     .12       0  250.73     .06       0  258.82     .12       0
  448.85     .04       0  470.94    .045       0  572.28     .04       0
  576.32     .12       0  741.57    .016       0  792.66     .12       0
Bank Sta=470.94,572.28
XS Rating Curve= 0 ,0
Exp/Cntr=0.3,0.1

Type RM Length L Ch R = 1 ,61566.3 ,669.8,659.7,649.7
XS GIS Cut Line= 4
     2379749.976       377186.06     2380013.474        377199.6
     2380604.143      376429.116     2380843.726      376377.033
#Sta/Elev= 30
       0  461.61  174.54450.6578  257.87446.5047  266.03445.7491  385.41436.0234
   467.6  426.06   519.5  426.22   575.5  422.77   607.4  416.33   631.4  419.21
   695.3  420.39  739.47416.0943   767.2   413.3   831.2   413.1   837.2 413.265
  838.33413.3582   851.2  420.08   859.1  422.04   887.1  417.26   899.1  417.34
   903.1  418.46   915.1  426.98     967  423.61 1016.41424.4306  1046.9  422.92
 1058.65425.2813 1248.29  447.63 1396.52459.8477 1402.49460.2297  1479.9  464.88
#Mann= 14 ,-1 , 0
       0     .12       0  174.54    .016       0  257.87     .12       0
  266.03     .06       0  385.41     .12       0  739.47     .04       0
   767.2    .045       0   837.2     .04       0  838.33     .12       0
 1016.41    .016       0 1058.65     .12       0 1248.29     .06       0
 1396.52     .08       0 1402.49     .06       0
Bank Sta=767.2,837.2
XS Rating Curve= 0 ,0
Exp/Cntr=0.3,0.1

Type RM Length L Ch R = 1 ,60906.6 ,886.1,882.4,878.6
XS GIS Cut Line= 3
     2380193.673      378341.342     2380485.339      377952.454
     2381145.062      376563.565
#Sta/Elev= 30
       0  504.03   119.5  501.88   207.2  495.13     263  487.81   374.5  464.04
  421.82457.3338  462.72452.7867   597.9  442.36   737.7  440.65  964.29428.5838
 1036.29424.2563 1053.35423.9896  1137.1  424.59  1236.9  421.16  1316.8  423.52
 1418.55420.8058 1485.36423.4905  1532.5  423.69  1552.4  418.67  1600.4  417.17
  1612.4  413.09  1680.3  413.09  1692.2  417.17 1693.32417.6348 1700.98421.7706
  1708.2  425.32  1724.2  424.16 1745.23427.2261    1812  454.38  2023.7  492.25
#Mann= 13 ,-1 , 0
       0     .12       0  421.82    .016       0  462.72     .06       0
  964.29     .12       0 1036.29     .08       0 1053.35     .12       0
 1418.55     .06       0 1485.36     .12       0  1600.4    .045       0
  1692.2     .04       0 1693.32     .12       0 1700.98    .016       0
 1745.23     .12       0
Bank Sta=1600.4,1692.2
XS Rating Curve= 0 ,0
Exp/Cntr=0.3,0.1

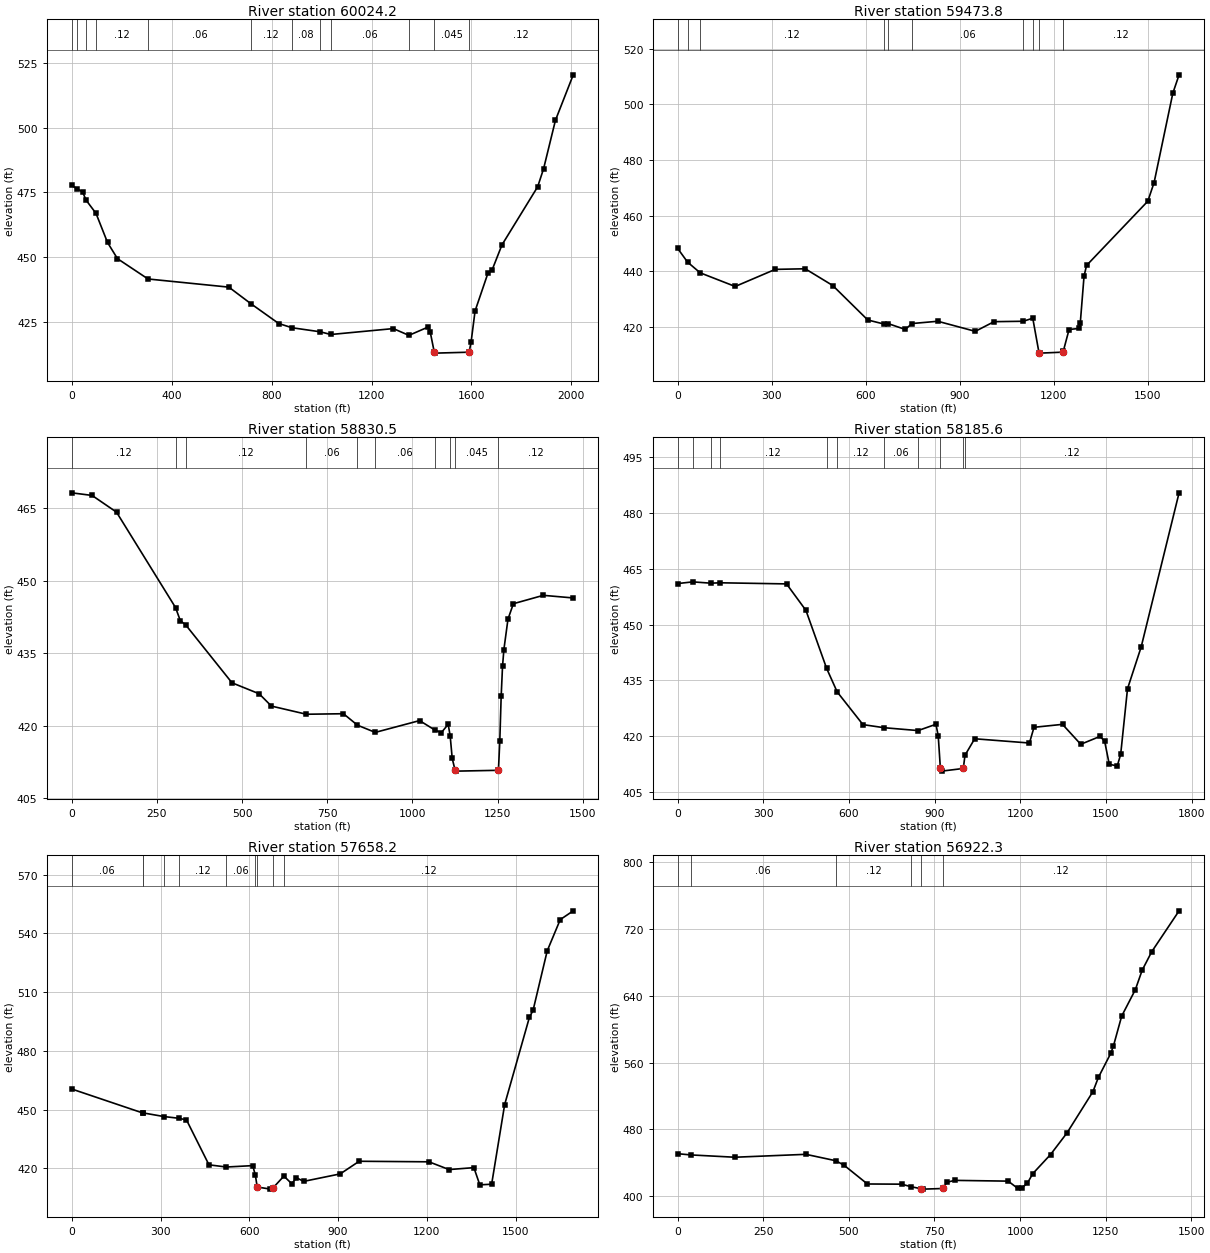
Type RM Length L Ch R = 1 ,60024.2 ,546.1,550.4,554.9
XS GIS Cut Line= 4
       2381391.3      378643.513     2381409.789      378146.541
     2381881.921      376951.685     2382081.404      376846.638
#Sta/Elev= 30
       0  477.71   21.09476.4278    43.8  475.13   57.19472.0403   97.16466.8895
   143.2  455.63     183  449.36  305.29441.4922     629  438.33  716.15431.9855
   828.5  424.25  881.53422.6119  994.28421.0458 1037.07419.9947  1287.3  422.28
 1349.67419.6615    1427   422.9    1435  420.97  1450.9   413.3  1454.9  412.78
  1590.6  413.14  1598.5     417  1614.5  429.09  1666.4  443.85  1682.3  444.88
  1722.2   454.7  1865.1  477.19  1888.9  484.23  1936.3  502.95  2007.5  520.54
#Mann= 12 ,-1 , 0
       0     .06       0   21.09     .12       0   57.19    .016       0
   97.16     .12       0  305.29     .06       0  716.15     .12       0
  881.53     .08       0  994.28     .12       0 1037.07     .06       0
 1349.67     .12       0  1450.9    .045       0  1590.6     .12       0
Bank Sta=1450.9,1590.6
XS Rating Curve= 0 ,0
Exp/Cntr=0.3,0.1

Type RM Length L Ch R = 1 ,59473.8 ,645.4,643.3,640.8
XS GIS Cut Line= 3
     2381829.837      378540.227     2381838.518      378240.748
     2382411.435      377073.213
#Sta/Elev= 30
       0  448.28   31.81443.3199   72.04439.4744   183.8  434.57   311.6  440.71
   407.3  440.92   495.1  434.91   606.8  422.54  657.81421.1041  670.89421.2758
   726.5  419.14  747.78421.2614   830.2  422.08   949.9  418.46  1009.7  421.93
 1102.88422.0811 1133.29423.1715 1153.06410.8324  1157.3  410.64  1229.1  410.99
 1231.08411.4899  1249.1  419.12    1281   419.5    1285  421.62  1296.9   438.3
  1304.9  442.12  1500.4  465.19  1520.4  471.89  1580.2  503.97  1600.1  510.55
#Mann= 11 ,-1 , 0
       0     .12       0   31.81    .016       0   72.04     .12       0
  657.81     .06       0  670.89     .12       0  747.78     .06       0
 1102.88     .12       0 1133.29     .04       0 1153.06    .045       0
  1229.1     .04       0 1231.08     .12       0
#XS Ineff= 2 , 0
       0   367.4                       0
Permanent Ineff=
       F       F
Bank Sta=1153.06,1229.1
XS Rating Curve= 0 ,0
Exp/Cntr=0.3,0.1

Type RM Length L Ch R = 1 ,58830.5 ,646.2,644.9,643.5
XS GIS Cut Line= 3
     2382302.758      378734.658     2382459.178      378518.526
     2382936.608      377411.755
#Sta/Elev= 30
       0  468.14    59.7   467.6   131.4  464.15  304.75444.4295   318.7  441.73
   334.8440.8285   470.4  428.89   550.2  426.62   586.1  424.08  688.77422.3922
   797.6   422.5  838.81420.1309  891.02418.6424  1021.1  421.08 1065.68419.1439
    1085   418.6    1105   420.3 1110.83417.9893  1116.9  413.27  1124.9  410.95
  1128.9  410.64  1252.6  410.81  1256.6  416.86  1260.6  426.08  1264.6  432.28
  1268.6  435.76  1280.6  442.04  1296.5  445.23  1384.3  446.96  1472.2  446.42
#Mann= 10 ,-1 , 0
       0     .12       0  304.75    .016       0   334.8     .12       0
  688.77     .06       0  838.81     .12       0  891.02     .06       0
 1065.68     .12       0 1110.83     .04       0  1124.9    .045       0
  1252.6     .12       0
Bank Sta=1124.9,1252.6
XS Rating Curve= 0 ,0
Exp/Cntr=0.3,0.1

Type RM Length L Ch R = 1 ,58185.6 ,537.8,527.4,517.1
XS GIS Cut Line= 4
     2383149.112      379016.776     2383070.987      378639.172
     2383570.119      377480.318     2383622.203      377384.832
#Sta/Elev= 30
       0  461.01   53.21461.4671  116.74 461.114  148.61461.2211   381.6  460.92
   449.5   453.8  521.97438.2234  558.92431.9088   649.1  423.13  723.58422.2959
  842.13  421.53   904.7  423.22   912.7  420.14  920.11  411.57   924.6  410.64
  1000.5  411.35 1006.43414.8997  1040.4  419.33  1232.1  418.19  1248.1  422.41
  1347.9   423.2  1411.8  417.85  1479.7  419.98  1495.6  418.61  1511.6  412.48
  1539.6  412.03  1551.6  415.15  1575.5  432.75  1623.4     444  1756.1  485.38
#Mann= 11 ,-1 , 0
       0     .06       0   53.21     .12       0  116.74     .06       0
  148.61     .12       0  521.97    .016       0  558.92     .12       0
  723.58     .06       0  842.13     .12       0  920.11    .045       0
  1000.5     .04       0 1006.43     .12       0
Bank Sta=920.11,1000.5
XS Rating Curve= 0 ,0
Exp/Cntr=0.3,0.1

Type RM Length L Ch R = 1 ,57658.2 ,718.9,735.9,752.8
XS GIS Cut Line= 3
     2383544.247      378878.769     2383717.858      378757.241
     2383862.923       377281.22
#Sta/Elev= 30
       0  460.49  239.34 448.274  240.71448.2884  310.97446.4323  362.56445.5165
   387.8   444.7   463.8  421.74  522.71420.6196   611.7  421.33   620.7416.4125
  626.76410.4167   671.6  409.32   680.9410.0563  717.08415.9763   743.6  412.08
   759.6  415.15   783.6  413.27   907.5  417.11   971.5  423.56  1207.3  423.28
  1275.3  419.32  1359.2   420.3  1379.2  411.51  1419.2  411.83  1463.2  452.55
  1547.1  497.26  1559.1  500.63  1607.1  531.14  1651.1  547.08    1695  551.56
#Mann= 10 ,-1 , 0
       0     .06       0  239.34     .12       0  240.71    .016       0
  310.97     .06       0  362.56     .12       0  522.71     .06       0
   620.7     .04       0  626.76    .045       0   680.9     .04       0
  717.08     .12       0
Bank Sta=626.76,680.9
XS Rating Curve= 0 ,0
Exp/Cntr=0.3,0.1

Type RM Length L Ch R = 1 ,56922.3 ,587.3,601.3,615.3
XS GIS Cut Line= 3
     2383965.254      378861.408     2384164.907      378709.498
     2384794.247      377672.171
#Sta/Elev= 30
       0  450.91   37.86449.4458   167.2  446.66   374.6  450.14  462.09442.4635
   486.4  436.99   554.2  414.65     654  414.44  682.12411.3623   709.9  409.04
   717.8   408.5  775.52409.2617   785.7  416.69   809.6  418.97   965.3  418.06
   993.2  409.37  1005.2  410.09  1021.2  415.52  1037.1  427.05    1089  449.92
  1136.9  475.71  1212.7  525.18  1228.7  542.25  1264.6  570.88  1272.6  579.85
  1296.6  615.52  1336.5  647.12  1356.4  670.41  1384.4  692.62  1464.2  741.49
#Mann= 6 ,-1 , 0
       0     .12       0   37.86     .06       0  462.09     .12       0
  682.12     .04       0   709.9    .045       0  775.52     .12       0
Bank Sta=709.9,775.52
XS Rating Curve= 0 ,0
Exp/Cntr=0.3,0.1

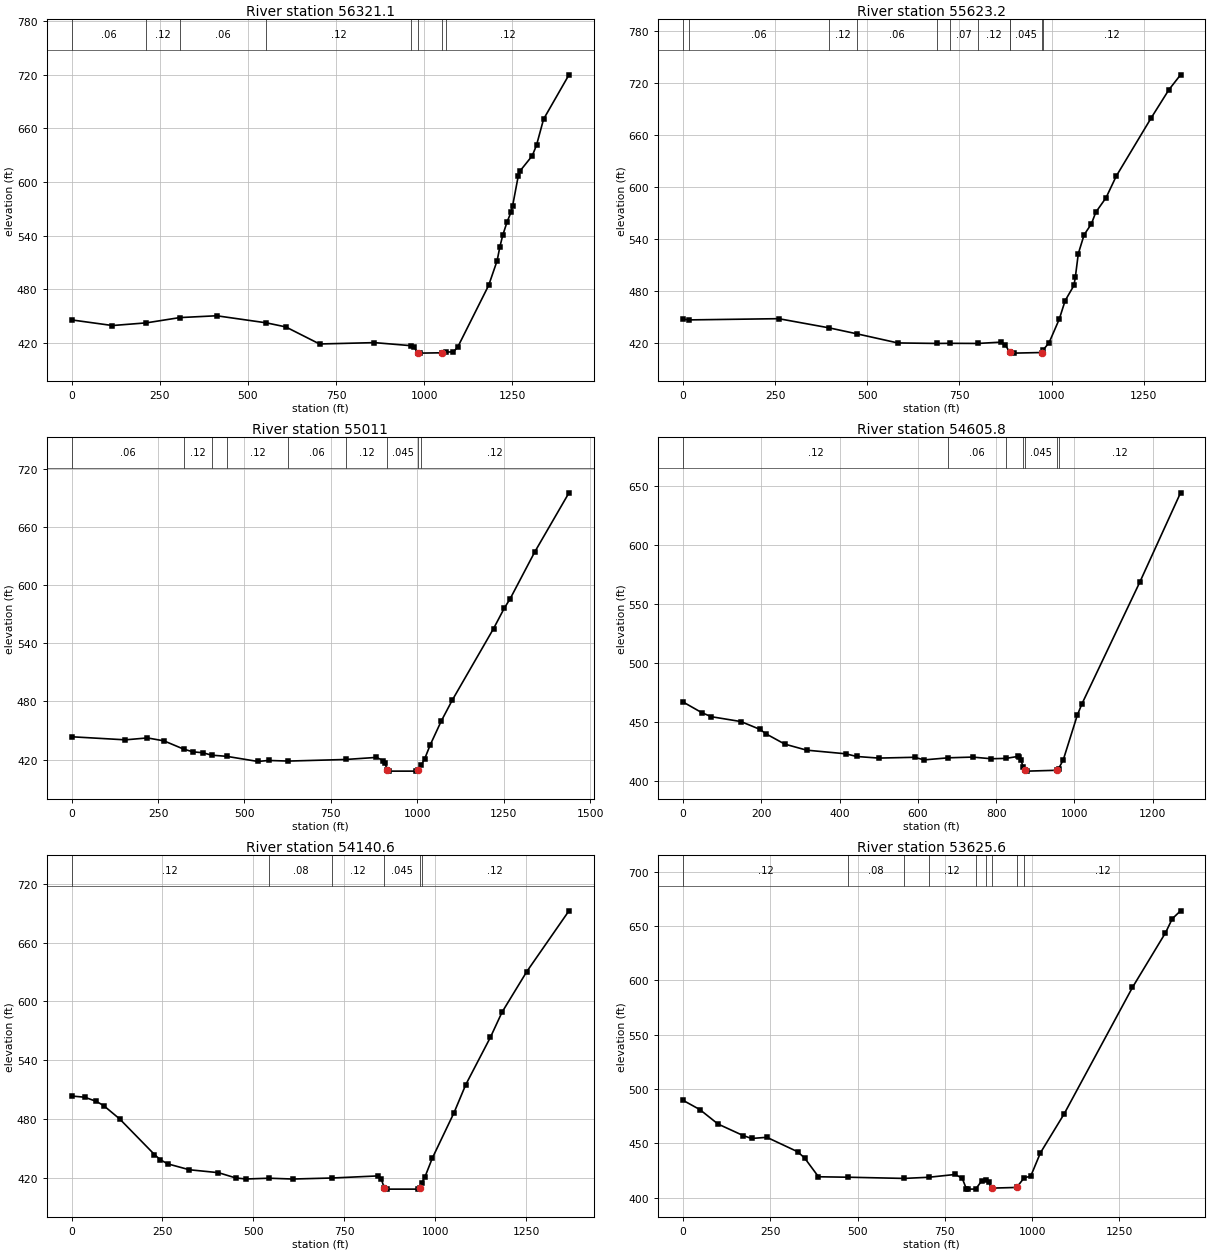
Type RM Length L Ch R = 1 ,56321.1 ,689.9,697.9,705.7
XS GIS Cut Line= 2
     2384147.546      379160.887     2385262.997      378297.171
#Sta/Elev= 30
       0  445.42   115.9   439.1  212.27442.1035  307.06 448.004   411.6  450.05
  552.61442.1079   607.5  437.57   703.4  418.42   859.2  419.94  961.56416.5586
   971.1  414.78   983.1  408.39   987.1  408.17  1051.1  408.56 1062.21409.2935
    1083  409.67    1095  414.71    1183   484.1  1206.9  511.58  1214.9  527.44
  1222.9  540.13  1234.9  554.83  1246.9   566.6  1250.9  573.08  1266.9   606.6
  1270.9  611.78  1306.8  629.48  1318.8   641.3  1338.8  670.43  1410.8  720.11
#Mann= 8 ,-1 , 0
       0     .06       0  212.27     .12       0  307.06     .06       0
  552.61     .12       0  961.56     .04       0   983.1    .045       0
  1051.1     .04       0 1062.21     .12       0
Bank Sta=983.1,1051.1
XS Rating Curve= 0 ,0
Exp/Cntr=0.3,0.1

Type RM Length L Ch R = 1 ,55623.2 ,600.4,612.2,624
XS GIS Cut Line= 3
     2384462.914      379541.934     2385283.476      379148.514
     2385679.664      378956.894
#Sta/Elev= 30
       0  447.27   16.96 446.492   259.4   447.9  395.82437.3516  472.63430.3499
   582.7  419.92  689.43 419.332  724.48419.4784  799.73419.3323   862.1  420.81
   874.1  417.96  885.96409.3744     886  409.35     898  408.17   973.4  408.88
  976.95411.6845   993.3  420.22    1021  447.45  1036.9  468.71  1060.7   486.2
  1064.6  495.88  1072.6  522.88  1088.4  544.66  1108.2  557.29  1120.1  570.68
  1147.9  587.39  1175.6   612.3  1270.8   679.7  1318.4   711.9  1350.1  729.15
#Mann= 11 ,-1 , 0
       0     .12       0   16.96     .06       0  395.82     .12       0
  472.63     .06       0  689.43     .12       0  724.48     .07       0
  799.73     .12       0  885.96     .04       0     886    .045       0
   973.4     .04       0  976.95     .12       0
Bank Sta=886,973.4
XS Rating Curve= 0 ,0
Exp/Cntr=0.3,0.1

Type RM Length L Ch R = 1 ,55011   ,402.6,405.2,407.7
XS GIS Cut Line= 3
     2384593.651      379832.759     2385731.747       379677.38
     2386005.185      379581.894
#Sta/Elev= 30
       0  443.59   155.6  440.42   219.4  442.39   267.2  439.37  323.79430.9162
     351  428.04   378.9  427.17  405.31424.6169  448.21423.4298   538.4  418.15
   570.3  419.16  626.68418.5324   792.7  420.17   881.4  422.31   901.4   419.1
   905.4  416.83   913.3  409.26   917.3  408.17   997.1  408.17 1003.06409.0462
 1011.65414.8439    1021  420.76    1037  435.12  1068.9  459.69  1100.8  481.28
  1220.1  554.99  1251.8  576.47  1267.7  585.46  1339.1   633.9  1438.3     695
#Mann= 9 ,-1 , 0
       0     .06       0  323.79     .12       0  405.31     .06       0
  448.21     .12       0  626.68     .06       0   792.7     .12       0
   913.3    .045       0 1003.06     .04       0 1011.65     .12       0
Bank Sta=913.3,1003.06
XS Rating Curve= 0 ,0
Exp/Cntr=0.3,0.1

Type RM Length L Ch R = 1 ,54605.8 ,462,465.2,468.6
XS GIS Cut Line= 2
     2384702.034      380162.039     2385970.462      380076.685
#Sta/Elev= 30
       0  466.87      48   457.8      72  454.41   147.9  450.27   195.9  443.71
   211.9  439.84   259.9  431.11   315.8  425.98   415.8  422.89   443.8   420.6
   499.7  419.25   591.7  419.93   615.7  417.71  677.82 419.489   739.6  420.09
   787.6  418.69  824.76418.9872   855.5  420.64   859.5  419.99   863.5  417.32
  869.21411.7096  873.69408.8973   879.5  408.17  956.74408.9066  959.71410.3223
   971.5  417.68  1007.4  455.66  1019.4  465.41  1167.4  568.88  1271.3   644.6
#Mann= 7 ,-1 , 0
       0     .12       0  677.82     .06       0  824.76     .12       0
  869.21     .04       0  873.69    .045       0  956.74     .04       0
  959.71     .12       0
Bank Sta=873.69,956.74
XS Rating Curve= 0 ,0
Exp/Cntr=0.3,0.1

Type RM Length L Ch R = 1 ,54140.6 ,511.2,515,518.6
XS GIS Cut Line= 2
     2384695.839      380546.114     2386062.973      380575.181
#Sta/Elev= 30
       0  503.26      36  502.05      68   497.8      88  493.55     132  479.96
   227.9  443.52   243.9  438.24   263.9  434.03   323.9  427.95   403.8  424.98
   451.8  419.54   479.8  418.52  543.12419.3205   607.8  418.48  717.21  419.54
   843.7  421.69   851.6   418.3   859.6  409.46   867.6  408.17   951.6  408.17
  956.65409.7353  962.21414.2372   971.6  420.72   991.6  439.68  1051.6  486.35
  1083.6  514.78  1151.5  563.26  1183.5  588.92  1251.5  630.36  1367.4  692.38
#Mann= 6 ,-1 , 0
       0     .12       0  543.12     .08       0  717.21     .12       0
   859.6    .045       0  956.65     .04       0  962.21     .12       0
Bank Sta=859.6,956.65
XS Rating Curve= 0 ,0
Exp/Cntr=0.3,0.1

Type RM Length L Ch R = 1 ,53625.6 ,526.2,533.1,539.9
XS GIS Cut Line= 3
     2384639.074      380965.654     2385909.698      381118.352
     2386052.928      381144.394
#Sta/Elev= 30
       0  489.51      48     481     100  467.71     172  457.11     196  454.42
     240  455.47   327.9  442.23   347.9  436.52   387.9  419.14  472.94418.7256
  632.86  417.62  703.14418.6643   779.9  421.27   799.8  417.72   811.8  407.87
   815.8  407.76  838.39407.8183   855.8  415.52  868.18415.8053   875.8  414.33
   883.8  408.68   955.8  409.31  977.54418.3615   995.8  419.49  1023.8  441.18
  1091.8  477.06  1287.6  593.56  1382.1   643.8  1401.7   656.8  1425.3  664.06
#Mann= 9 ,-1 , 0
       0     .12       0  472.94     .08       0  632.86     .06       0
  703.14     .12       0  838.39     .04       0  868.18     .12       0
   883.8    .045       0   955.8     .04       0  977.54     .12       0
Bank Sta=883.8,955.8
XS Rating Curve= 0 ,0
Exp/Cntr=0.3,0.1

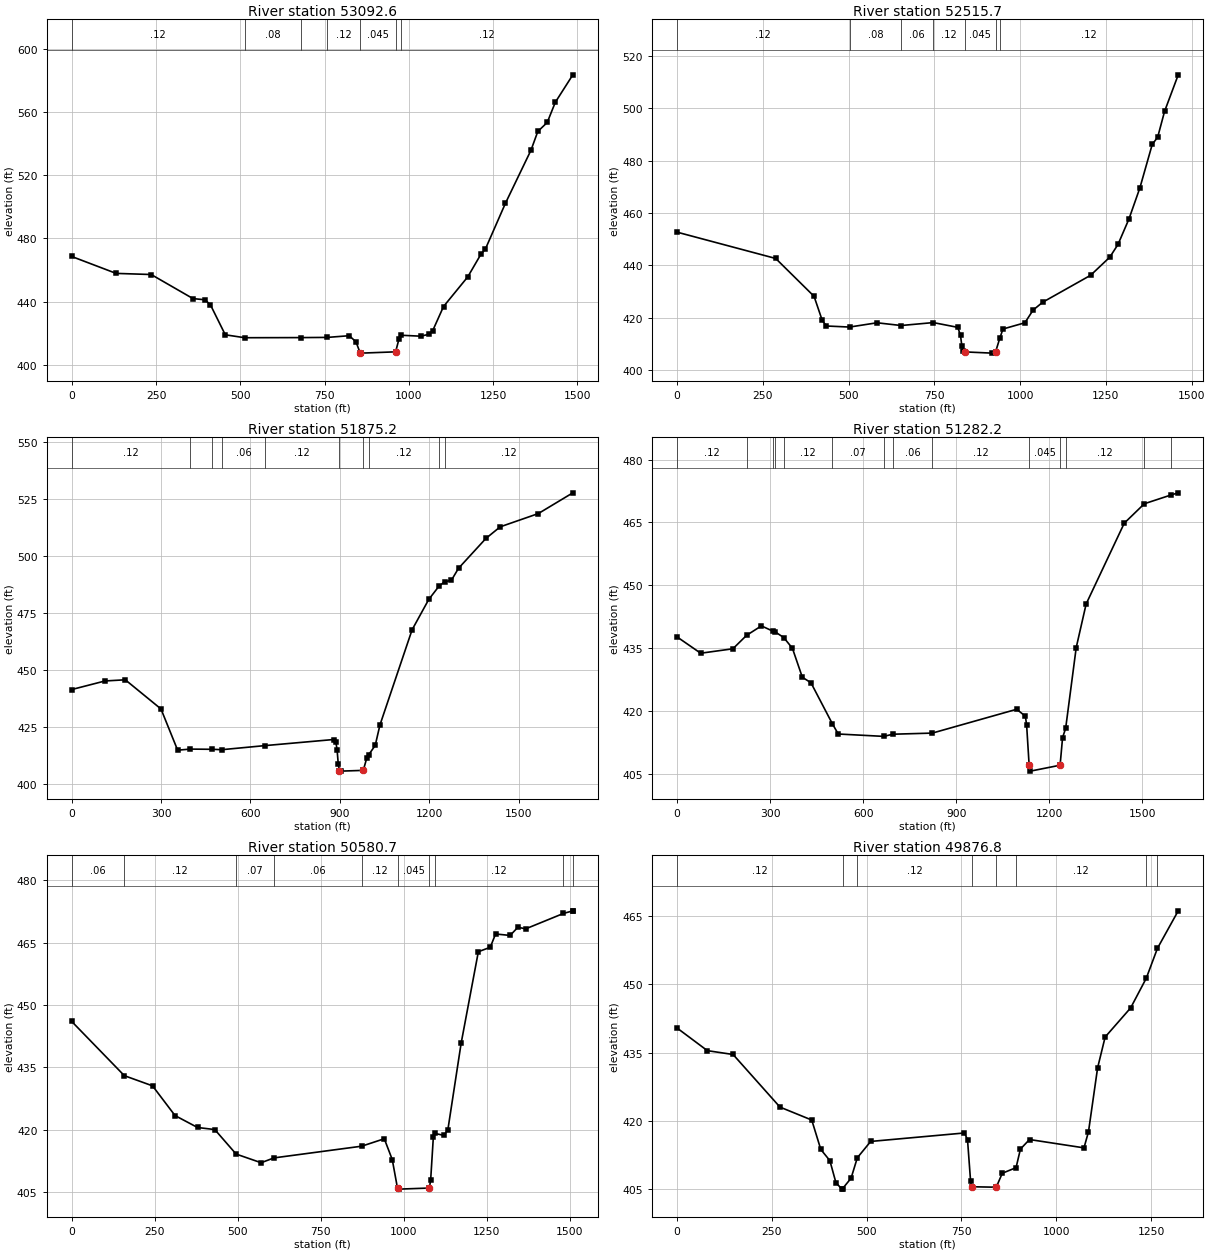
Type RM Length L Ch R = 1 ,53092.6 ,571.7,576.8,581.9
XS GIS Cut Line= 3
     2384505.857      381310.106     2385692.685      381678.248
      2385935.74      381695.609
#Sta/Elev= 30
       0  468.58   131.8  457.87   235.7  457.16   359.6  441.91   395.6  441.14
   411.5  437.92   455.5  418.96  513.16417.1112  680.81417.1921  758.05417.3112
   823.1  418.38   843.1  414.53     855  407.73     859  407.35   960.7  408.17
   970.9  416.52   977.8 418.667  1034.8  418.09  1058.8  419.24  1070.8  421.63
  1102.8  436.89  1174.7  455.68  1214.6  470.35  1226.6  473.12  1286.6  502.39
  1362.4  536.04  1382.4   547.8  1410.4  553.52  1434.4  566.31  1486.3  583.69
#Mann= 7 ,-1 , 0
       0     .12       0  513.16     .08       0  680.81     .06       0
  758.05     .12       0     855    .045       0   960.7     .04       0
   977.8     .12       0
Bank Sta=855,960.7
XS Rating Curve= 0 ,0
Exp/Cntr=0.3,0.1

Type RM Length L Ch R = 1 ,52515.7 ,634.9,640.5,646.1
XS GIS Cut Line= 2
     2384355.829      381737.506     2385679.664      382355.331
#Sta/Elev= 30
       0  452.72   287.4  442.67   399.2  428.21   423.1  418.98   435.1  416.86
  502.75 416.455   582.8  418.09  653.01 417.044  746.84418.1644   818.3  416.34
   826.2  413.25   830.2  409.09   834.2   407.2   838.2  406.96   918.1  406.49
  928.33406.9313  941.01412.3179     950  415.71  1013.8  418.09  1037.8  422.94
  1065.7  425.94  1205.4  436.24  1261.3  443.15  1285.3  448.03  1317.2  457.75
  1349.1  469.64  1385.1  486.26    1401  489.03    1421  498.86  1460.9  512.86
#Mann= 7 ,-1 , 0
       0     .12       0  502.75     .08       0  653.01     .06       0
  746.84     .12       0   838.2    .045       0  928.33     .04       0
  941.01     .12       0
Bank Sta=838.2,928.33
XS Rating Curve= 0 ,0
Exp/Cntr=0.3,0.1

Type RM Length L Ch R = 1 ,51875.2 ,590.9,593,595.1
XS GIS Cut Line= 3
     2384126.636      382181.018     2385202.233      382893.526
     2385588.518      382828.421
#Sta/Elev= 30
       0  441.49   111.8  445.25   179.8  445.76   299.6  432.97   355.5  414.89
  397.25 415.374   472.2415.2793  503.57 415.108  648.54416.8996   878.8  419.57
   886.8  418.34   890.8  414.88   894.7  408.64  898.57405.8923   902.7  405.71
   978.6  406.04   990.6   411.6  997.12412.9728  1018.6  416.96  1034.5  425.94
  1142.4  467.69  1198.3  480.99 1233.01486.8646 1251.78488.7732  1274.2  489.37
  1298.2  494.65  1390.1  507.74  1438.1  512.84    1566  518.65  1681.9  527.75
#Mann= 10 ,-1 , 0
       0     .12       0  397.25     .08       0   472.2     .12       0
  503.57     .06       0  648.54     .12       0  898.57    .045       0
   978.6     .04       0  997.12     .12       0 1233.01    .016       0
 1251.78     .12       0
Bank Sta=898.57,978.6
XS Rating Curve= 0 ,0
Exp/Cntr=0.3,0.1

Type RM Length L Ch R = 1 ,51282.2 ,694.5,701.6,708.6
XS GIS Cut Line= 3
     2383652.585      382497.679     2384742.164      383310.192
     2384720.462      383566.269
#Sta/Elev= 30
       0   437.7      76  433.82   179.9  434.88  224.11438.0863   271.8  440.34
  310.26439.0315  316.32438.9061  343.82437.5582   371.8  435.01   403.8   428.1
   431.7  426.77  500.37417.0463   519.7  414.56  666.37413.9923  695.61  414.51
  823.06414.7768  1095.3  420.46  1123.3  418.79  1127.3  416.64  1135.3  407.19
  1139.3  405.71  1235.2  407.12  1243.2   413.7 1253.14 415.923  1287.2  435.17
  1319.2  445.56  1442.2  464.83 1506.83469.4539 1591.49 471.511  1616.2  472.06
#Mann= 14 ,-1 , 0
       0     .12       0  224.11     .06       0  310.26     .12       0
  316.32     .06       0  343.82     .12       0  500.37     .07       0
  666.37     .12       0  695.61     .06       0  823.06     .12       0
  1135.3    .045       0  1235.2     .04       0 1253.14     .12       0
 1506.83    .016       0 1591.49     .12       0
Bank Sta=1135.3,1235.2
XS Rating Curve= 0 ,0
Exp/Cntr=0.3,0.1

Type RM Length L Ch R = 1 ,50580.7 ,712.6,703.8,695.1
XS GIS Cut Line= 3
     2383396.678      382915.227     2384282.094      383878.769
     2384481.747       383900.47
#Sta/Elev= 30
       0  446.05  158.52433.0078   243.4  430.56   311.2  423.41     379  420.54
   430.9  420.04  495.16414.1459   570.5  412.06   609.1413.2223   873.5 416.042
   941.5  417.83   965.5  412.82   981.4  405.88   985.4  405.71  1077.2  405.97
  1081.2  407.94  1089.2  418.19 1094.54419.1024  1121.1  418.64    1133  419.99
  1172.9  440.78  1224.8  462.83  1260.7   463.9  1276.7   467.1  1320.4  466.75
    1344  468.71  1367.6  468.34 1480.98472.0374 1509.29472.6649  1509.4  472.67
#Mann= 10 ,-1 , 0
       0     .06       0  158.52     .12       0  495.16     .07       0
   609.1     .06       0   873.5     .12       0   981.4    .045       0
  1077.2     .04       0 1094.54     .12       0 1480.98     .06       0
 1509.29     .12       0
Bank Sta=981.4,1077.2
XS Rating Curve= 0 ,0
Exp/Cntr=0.3,0.1

Type RM Length L Ch R = 1 ,49876.8 ,691.1,684.6,678.1
XS GIS Cut Line= 3
     2382841.122      383579.289     2383809.004      384234.671
     2383960.914       384217.31
#Sta/Elev= 30
       0  440.42    79.8  435.46   147.6  434.62   271.3  423.07   355.1  420.23
     379  413.77   402.9  411.32   418.9  406.47   434.8  405.06  436.54405.1862
   458.8  407.45  475.36411.9491   510.6  415.53     758  417.39     766  415.91
     774   406.9  776.99405.5813   841.8  405.48   857.7  408.55  894.01409.7702
   905.6  413.86   929.5  415.95  1073.2  414.12  1085.1  417.66  1109.1  431.67
    1129  438.45  1196.3  444.85  1237.5451.3577 1267.01457.9337  1321.8  466.16
#Mann= 8 ,-1 , 0
       0     .12       0  436.54     .04       0  475.36     .12       0
  776.99    .045       0   841.8     .04       0  894.01     .12       0
  1237.5    .016       0 1267.01     .12       0
Bank Sta=776.99,841.8
XS Rating Curve= 0 ,0
Exp/Cntr=0.3,0.1

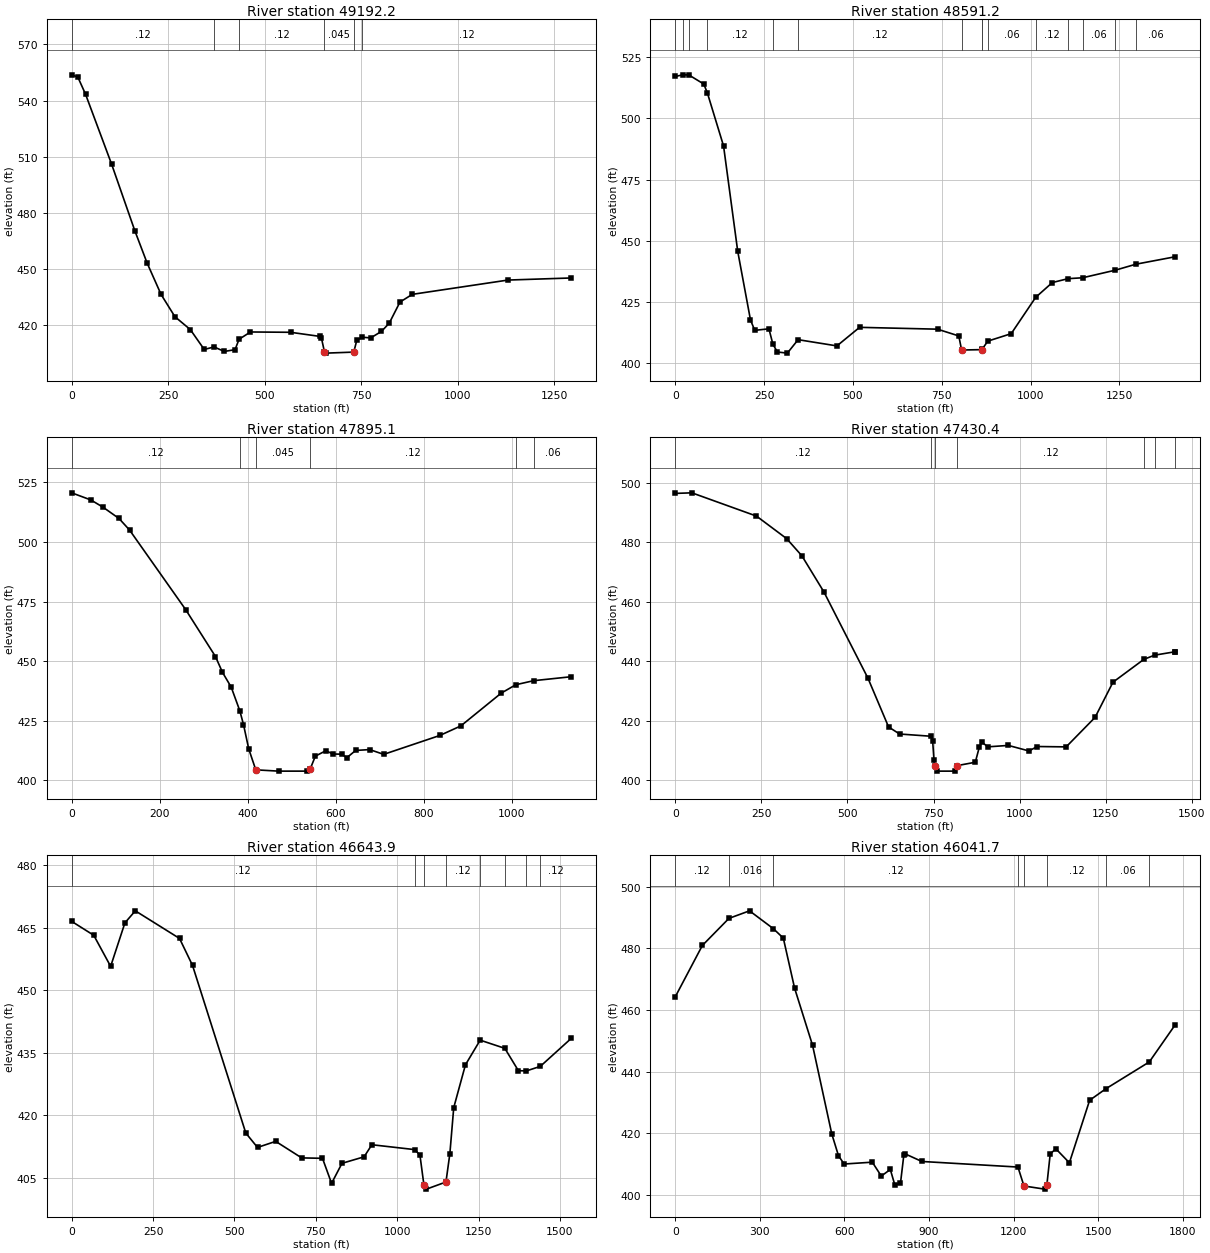
Type RM Length L Ch R = 1 ,49192.2 ,638.2,601,563.9
XS GIS Cut Line= 3
     2382470.431      384282.069     2383379.316      384694.741
     2383665.775      384620.956
#Sta/Elev= 30
       0  553.76      16  552.55    35.9  543.45   103.8  505.87   163.7  470.44
   195.6  453.15   231.6  436.45   267.5  424.55   307.4  417.67   343.4  407.06
  368.89408.4096   395.3     406   423.2  406.94  433.59412.5018   463.2   416.4
     567  416.23   642.8  414.04   646.8   413.3   654.8  405.79   658.8   405.1
   730.7  405.65   738.7  412.08  753.05413.5891   774.6  413.23   802.5  416.72
   822.5  421.07   850.4  432.38   882.4   436.5  1130.1  444.13    1294  445.25
#Mann= 6 ,-1 , 0
       0     .12       0  368.89     .04       0  433.59     .12       0
   654.8    .045       0   730.7     .04       0  753.05     .12       0
Bank Sta=654.8,730.7
XS Rating Curve= 0 ,0
Exp/Cntr=0.3,0.1

Type RM Length L Ch R = 1 ,48591.2 ,724.6,696.1,667.3
XS GIS Cut Line= 3
     2382385.393      385580.158     2383414.039      384937.796
     2383574.629      384829.289
#Sta/Elev= 30
       0  517.09    20.7517.7551   37.78517.7189    79.8     514   89.87510.4395
   135.6  488.71   175.5  445.68   211.4  417.67   223.4  413.41   263.3  414.04
  274.57407.7307   287.2  404.57   315.2  404.11  345.49409.6019   454.8  407.06
   518.6  414.64     738  413.89   797.9  411.13   805.8  405.38  863.14 405.538
   864.4405.8687  879.54409.0082   945.5  412.06  1014.4426.8912  1061.2  432.93
  1105.5434.5163 1146.53434.8845 1238.98437.9981 1296.84 440.433  1406.6  443.45
#Mann= 15 ,-1 , 0
       0     .06       0    20.7     .08       0   37.78    .016       0
   89.87     .12       0  274.57     .04       0  345.49     .12       0
   805.8    .045       0  863.14     .04       0   864.4     .08       0
  879.54     .06       0  1014.4     .12       0  1105.5    .016       0
 1146.53     .06       0 1238.98     .12       0 1296.84     .06       0
Bank Sta=805.8,863.14
XS Rating Curve= 0 ,0
Exp/Cntr=0.3,0.1

Type RM Length L Ch R = 1 ,47895.1 ,474.6,464.8,455.2
XS GIS Cut Line= 3
     2383266.469      386022.866     2383518.205      385814.533
     2383726.539      385033.283
#Sta/Elev= 30
       0  520.64    43.8  517.64    71.7  514.56   107.6  509.88   131.5  505.05
     259  471.67   326.8  451.96   342.7  445.33   362.6   439.1  382.07429.2336
   390.5  423.42   402.4   413.2   418.4  404.41   470.2  403.87   533.9  403.87
   541.8  404.64   553.8  410.15   577.7  412.44   593.6  411.06   613.5  410.98
   625.5  409.53   645.4  412.55   677.3  412.91   709.1   410.9   836.6  418.83
   884.4  422.84     976  436.58 1009.33440.1197 1049.94 441.822  1135.3  443.48
#Mann= 6 ,-1 , 0
       0     .12       0  382.07     .04       0   418.4    .045       0
   541.8     .12       0 1009.33    .016       0 1049.94     .06       0
Bank Sta=418.4,541.8
XS Rating Curve= 0 ,0
Exp/Cntr=0.3,0.1

Type RM Length L Ch R = 1 ,47430.4 ,786.3,786.4,786.6
XS GIS Cut Line= 4
     2384165.895       386494.12     2384012.223      386237.132
     2384008.657      385185.192     2383999.976      385085.366
#Sta/Elev= 30
       0  496.52    47.9  496.71   235.6  488.88   323.4  481.28   367.4  475.53
   431.4  463.38   559.4  434.35   619.4  417.92   651.4  415.54   742.6 414.788
   747.4  413.32   751.4  406.69  753.84404.7014   759.4  403.05   811.4  403.05
   819.4  404.92   871.4  406.04   883.4  411.28   891.4  412.76   907.4  411.22
   967.4   411.7  1027.4  409.84  1051.4  411.33  1135.4  411.21  1219.4  421.14
  1271.4  432.98 1361.12440.6628 1392.32442.0765 1451.25 443.211  1451.6  443.22
#Mann= 7 ,-1 , 0
       0     .12       0   742.6     .04       0  753.84    .045       0
   819.4     .12       0 1361.12    .016       0 1392.32     .12       0
 1451.25     .06       0
Bank Sta=753.84,819.4
XS Rating Curve= 0 ,0
Exp/Cntr=0.3,0.1

Type RM Length L Ch R = 1 ,46643.9 ,594.2,602.2,610.2
XS GIS Cut Line= 3
     2384559.872      386461.234     2384611.955      385228.595
     2384373.071      385045.422
#Sta/Elev= 30
       0  466.53    67.9  463.19   119.8  455.72   163.7  466.18   195.6  469.06
   331.4  462.43   371.3  455.96     535   415.7     571  412.24   626.8   413.7
   706.7  409.73   770.6  409.63   798.5  403.62   830.5  408.43   898.4  409.99
   922.3  412.89 1054.22411.7167    1070  410.38    1082  403.34    1090  402.23
  1149.9  403.94  1161.9  410.75  1173.8   421.8  1209.8  432.09 1254.98438.0036
 1330.78436.0372  1372.4  430.67 1396.84430.6158 1439.64431.7006  1534.8  438.43
#Mann= 8 ,-1 , 0
       0     .12       0 1054.22     .04       0    1082    .045       0
  1149.9     .12       0 1254.98    .016       0 1330.78     .12       0
 1396.84    .016       0 1439.64     .12       0
Bank Sta=1082,1149.9
XS Rating Curve= 0 ,0
Exp/Cntr=0.3,0.1

Type RM Length L Ch R = 1 ,46041.7 ,956.8,957.6,958.3
XS GIS Cut Line= 4
     2384782.596      386516.893     2384954.837      386318.005
      2385261.51      385138.191     2385215.254      384850.991
#Sta/Elev= 30
       0  464.33    95.7  480.91  190.05489.6926   263.1  492.14  347.76486.3397
     383   483.3     423  467.08   486.9  448.49   554.9  419.83   578.8  412.73
   598.8  410.04   698.8  410.64   730.7  406.14   762.7  408.27   778.7  403.28
   798.7  403.73   810.7  412.95   814.7  413.36   874.6  410.87 1215.63409.0574
 1237.08402.9191  1310.3   401.9  1318.3  403.28  1330.2  413.31  1350.2  414.98
  1398.2  410.44  1470.1  430.71 1528.34 434.482 1681.76443.1379    1773  455.09
#Mann= 8 ,-1 , 0
       0     .12       0  190.05    .016       0  347.76     .12       0
 1215.63     .04       0 1237.08    .045       0  1318.3     .12       0
 1528.34     .06       0 1681.76     .12       0
Bank Sta=1237.08,1318.3
XS Rating Curve= 0 ,0
Exp/Cntr=0.3,0.1