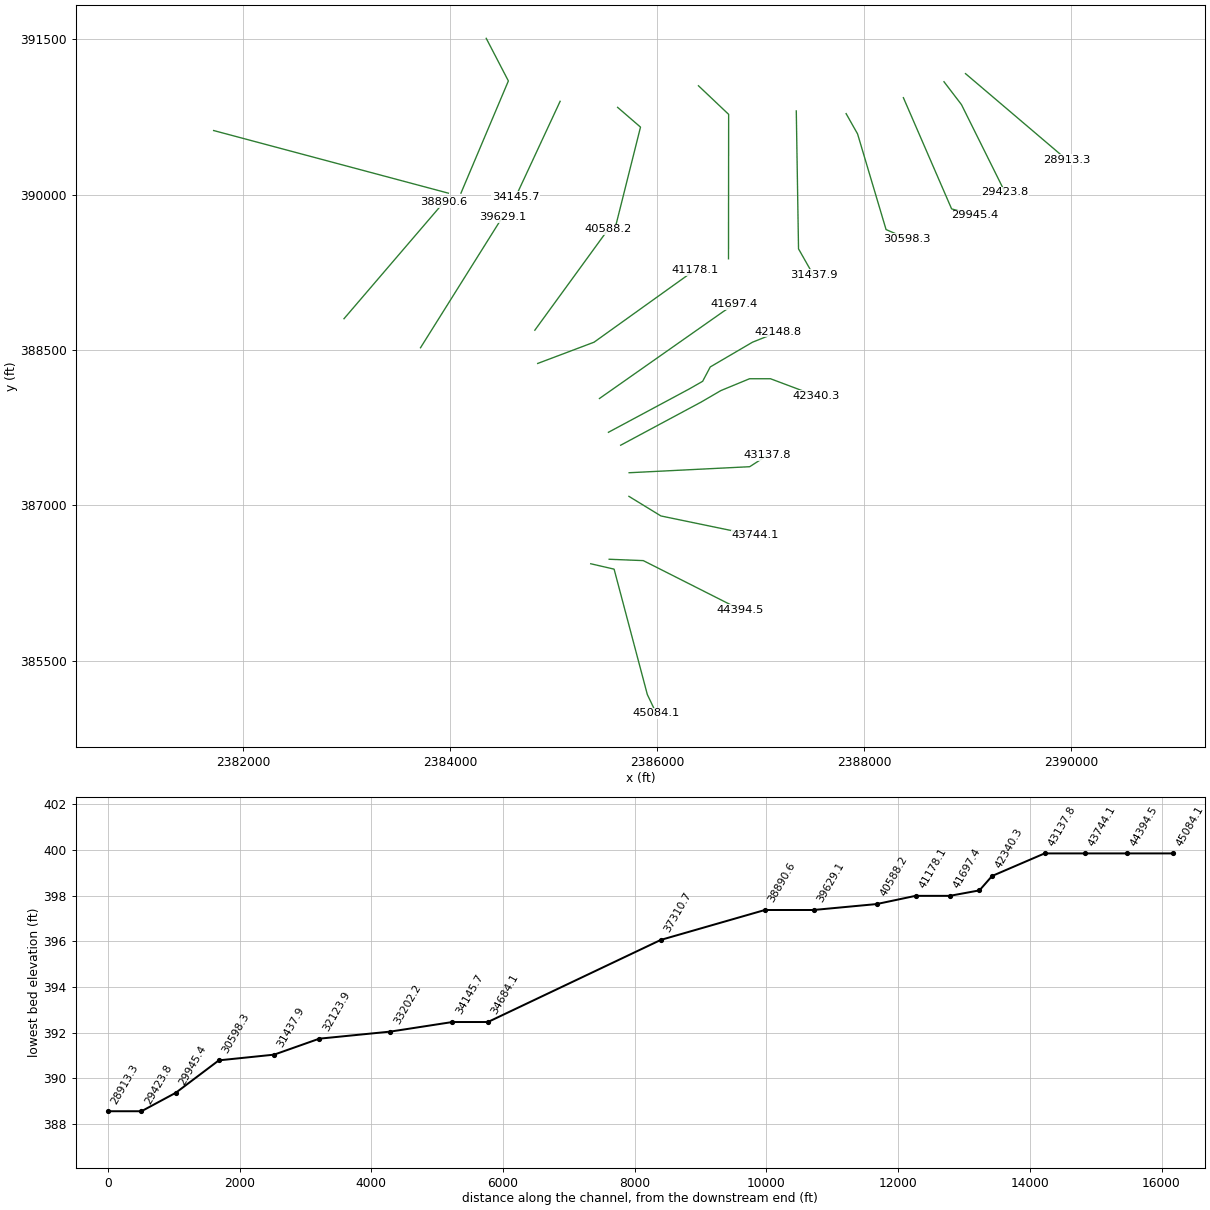
HEC-RAS study BACKCREEK.prj: BACKCREEK

--- BACKCREEK.g01 (geometry) --- (continued)

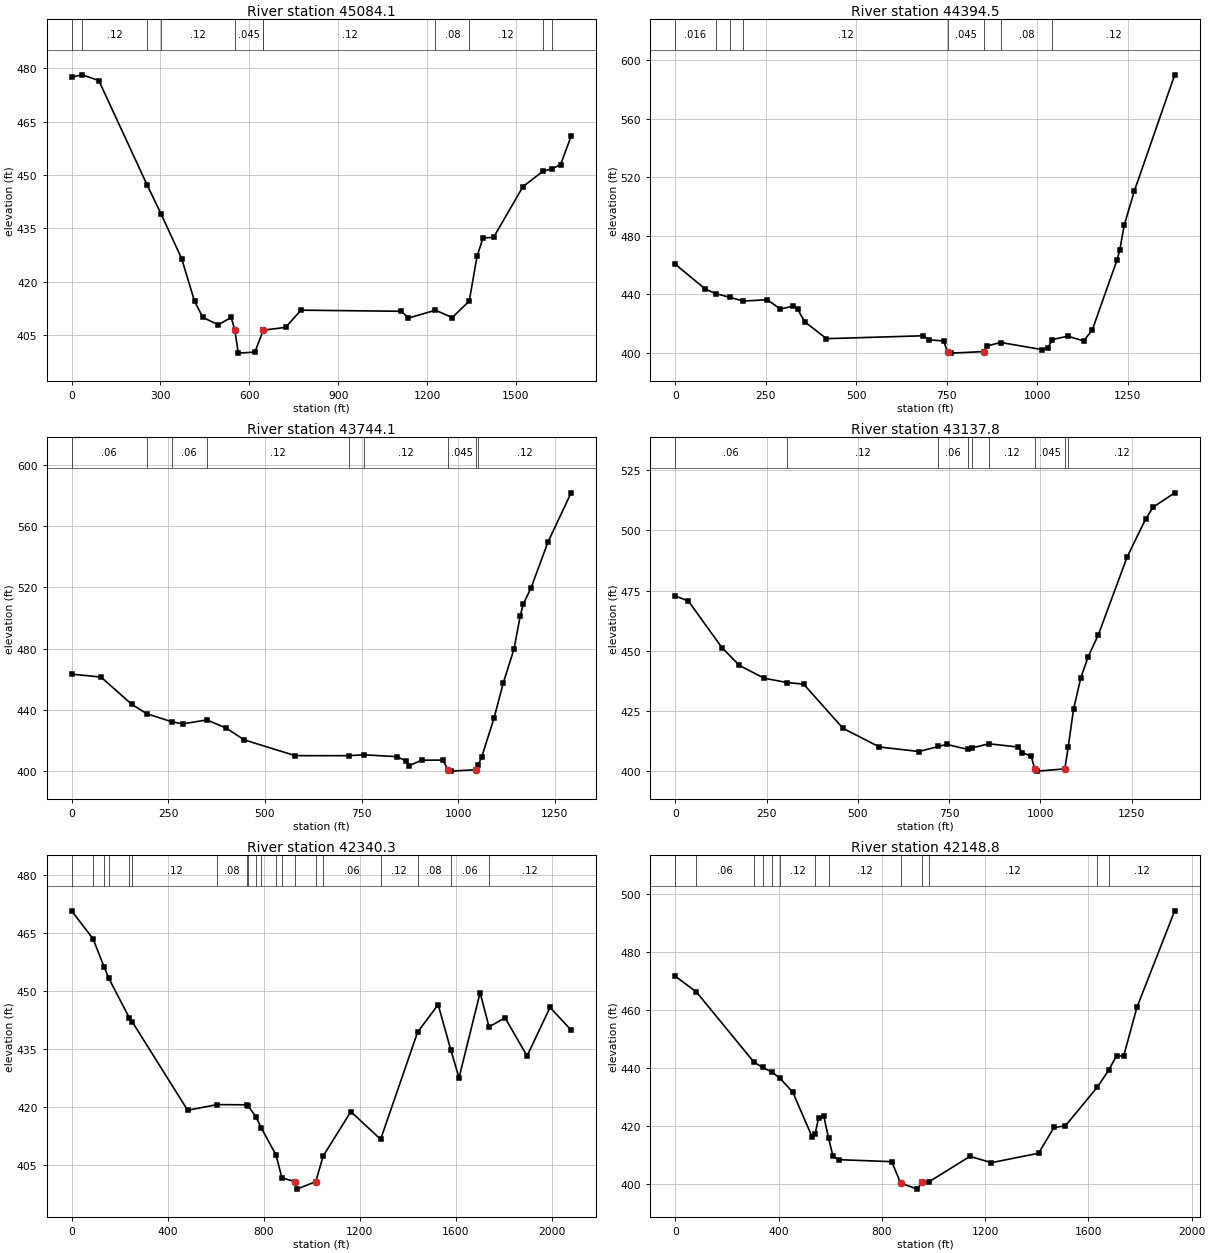
Type RM Length L Ch R = 1 ,45084.1 ,657.1,689.6,721.7
XS GIS Cut Line= 4
     2385358.483      386435.192     2385584.178      386383.109
     2385905.358      385172.171     2385992.164       384989.88
#Sta/Elev= 30
       0  477.59    36.4478.2125    91.8  476.59  254.48  447.26   302.6  438.93
   371.3  426.49   415.2  414.39   443.1  409.89     495  407.84   538.8  409.91
   550.8  406.39   562.8  399.85   618.6  400.14   646.6  406.23  647.48406.3224
   722.4   407.1   774.2  411.95  1113.4  411.63  1137.3  409.72 1228.47 411.939
  1284.9  409.86 1342.39414.5096  1368.7  427.09  1388.7  432.26  1424.6  432.46
    1524  446.75 1590.68451.0357 1622.27   451.8  1650.7   452.9  1686.3  460.91
#Mann= 11 ,-1 , 0
       0    .016       0    36.4     .12       0  254.48    .016       0
   302.6     .12       0   550.8    .045       0   646.6     .04       0
  647.48     .12       0 1228.47     .08       0 1342.39     .12       0
 1590.68    .016       0 1622.27     .12       0
Bank Sta=550.8,646.6
XS Rating Curve= 0 ,0
Exp/Cntr=0.3,0.1

Type RM Length L Ch R = 1 ,44394.5 ,640.9,650.4,660.3
XS GIS Cut Line= 3
     2385536.435      386478.595     2385866.296      386465.574
     2386803.796      385992.484
#Sta/Elev= 30
       0  460.56    83.5  443.56   111.7440.5231  151.78437.9209  188.14435.4183
   254.6  436.32   290.3  429.96   326.1  431.94   338.1  429.84   358.1  421.19
     418  409.73   685.5   411.7   701.4  408.92   741.4  408.18   753.4  400.36
   761.3  399.85   853.2  400.91   861.2  404.75   899.7407.1085  1012.9   402.3
  1028.9  403.05 1041.87409.1046  1084.8   411.4  1128.7  408.16  1152.6   415.8
  1220.5  463.24  1228.5   470.3  1240.5  487.05  1268.4  510.36  1380.2  589.93
#Mann= 8 ,-1 , 0
       0    .016       0   111.7     .12       0  151.78    .016       0
  188.14     .12       0   753.4    .045       0   853.2     .12       0
   899.7     .08       0 1041.87     .12       0
Bank Sta=753.4,853.2
XS Rating Curve= 0 ,0
Exp/Cntr=0.3,0.1

Type RM Length L Ch R = 1 ,43744.1 ,596.7,606.3,615.9
XS GIS Cut Line= 3
     2385727.407      387086.234      2386037.15      386896.875
     2386947.025       386708.63
#Sta/Elev= 30
       0  463.28    75.8  461.41   155.6  443.53   194.6 437.392  258.92432.1709
   287.2  430.77  349.95433.3446   398.9  428.14   446.8  420.27   578.4  409.98
  717.05409.9534  755.66410.5386   841.6   409.3   865.5  406.51   873.5  403.42
   905.4  406.99   961.2  407.07   973.2  400.66   981.1  399.85 1046.08400.7862
 1051.42403.7462  1060.9  409.14  1092.8  434.44  1116.7  457.54  1144.6  479.81
  1160.6  501.46  1168.6  509.16  1188.5  519.72  1232.4  549.72  1292.2  581.92
#Mann= 9 ,-1 , 0
       0     .06       0   194.6     .12       0  258.92     .06       0
  349.95     .12       0  717.05     .06       0  755.66     .12       0
   973.2    .045       0 1046.08     .04       0 1051.42     .12       0
Bank Sta=973.2,1046.08
XS Rating Curve= 0 ,0
Exp/Cntr=0.3,0.1

Type RM Length L Ch R = 1 ,43137.8 ,782.7,797.5,810.8
XS GIS Cut Line= 3
     2385729.557      387314.427     2386894.941      387372.692
     2387064.212      387481.199
#Sta/Elev= 30
       0  472.73      36  470.62   127.9  451.25   175.8  443.81   243.8  438.49
  306.14 436.718   351.6  436.05   459.5  417.66   559.4  409.89   667.3  408.01
  720.63410.1132   743.3  410.97  802.28408.8601  811.96409.4855  859.45411.2274
   939.1  409.87     951  407.58     975  406.01   984.7 400.736     991  399.85
  1066.9  400.77 1076.44409.9986  1090.9  425.65  1110.9  438.71  1130.9  447.46
  1158.8  456.58  1237.8  489.03    1289  504.93  1308.8  509.67  1367.9  515.65
#Mann= 9 ,-1 , 0
       0     .06       0  306.14     .12       0  720.63     .06       0
  802.28     .12       0  811.96     .06       0  859.45     .12       0
   984.7    .045       0  1066.9     .04       0 1076.44     .12       0
Bank Sta=984.7,1066.9
XS Rating Curve= 0 ,0
Exp/Cntr=0.3,0.1

Type RM Length L Ch R = 1 ,42340.3 ,189,191.5,195.7
XS GIS Cut Line= 6
     2385647.632      387580.201      2386425.41      387996.868
     2386616.382      388107.979      2386894.16      388222.562
     2387095.549      388222.562     2387539.994      388055.895
#Sta/Elev= 30
       0  470.74   89.18463.5103  135.55456.2072   154.3 453.366  239.72443.1389
  253.04442.0075   483.1  419.23  605.08420.6873  729.89420.6384  733.51420.4572
   767.3417.5378  790.51414.6035  851.14407.6471  875.44 401.812   929.7  400.78
   937.6  398.86  1016.5  400.79 1047.42407.4048  1162.6  418.87  1286.7411.7271
 1440.51439.3796  1526.2  446.53 1578.66434.8372  1613.2  427.63  1700.9  449.62
 1738.07440.7546  1804.6  443.13  1896.4  433.25  1992.1  445.79  2079.8  439.95
#Mann= 20 ,-1 , 0
       0     .06       0   89.18     .12       0  135.55     .06       0
   154.3     .12       0  239.72     .06       0  253.04     .12       0
  605.08     .08       0  729.89     .06       0  733.51     .08       0
   767.3     .12       0  790.51     .08       0  851.14     .06       0
  875.44     .12       0   929.7    .045       0  1016.5     .04       0
 1047.42     .06       0  1286.7     .12       0 1440.51     .08       0
 1578.66     .06       0 1738.07     .12       0
#XS Ineff= 2 , 0
       0     750            1160       0
Permanent Ineff=
       F       F
Bank Sta=929.7,1016.5
XS Rating Curve= 0 ,0
Exp/Cntr=0.3,0.1

Type RM Length L Ch R = 1 ,42148.8 ,448.5,451.3,454
XS GIS Cut Line= 6
     2385529.577      387705.201     2386307.355      388121.868
     2386440.215      388197.664     2386513.999      388336.552
     2386921.985      388575.268     2387171.551      388675.094
#Sta/Elev= 30
       0  471.67   81.88466.2368  304.34442.0813  338.15440.1941  375.74438.5546
  405.86436.4272   455.2  431.66     531  416.04  541.75417.2175     555  422.76
   574.9  423.56  593.94415.7808   610.9   409.5   634.8  408.38   838.4   407.7
  872.81400.3098   937.3  398.23   956.9  400.79  982.11400.7351  1141.5  409.53
  1224.4  407.35  1407.1  410.61  1466.7   419.5  1510.4  420.02 1634.08433.3686
  1678.3 439.221  1708.8  444.22  1736.4   444.1  1787.8   460.9  1934.1  494.21
#Mann= 13 ,-1 , 0
       0     .12       0   81.88     .06       0  304.34    .016       0
  338.15     .12       0  375.74     .06       0  405.86     .12       0
  541.75    .016       0  593.94     .12       0  872.81    .045       0
   956.9     .04       0  982.11     .12       0 1634.08     .06       0
  1678.3     .12       0
#XS Ineff= 2 , 0
       0     700            1290       0
Permanent Ineff=
       F       F
Bank Sta=872.81,956.9
XS Rating Curve= 0 ,0
Exp/Cntr=0.3,0.1

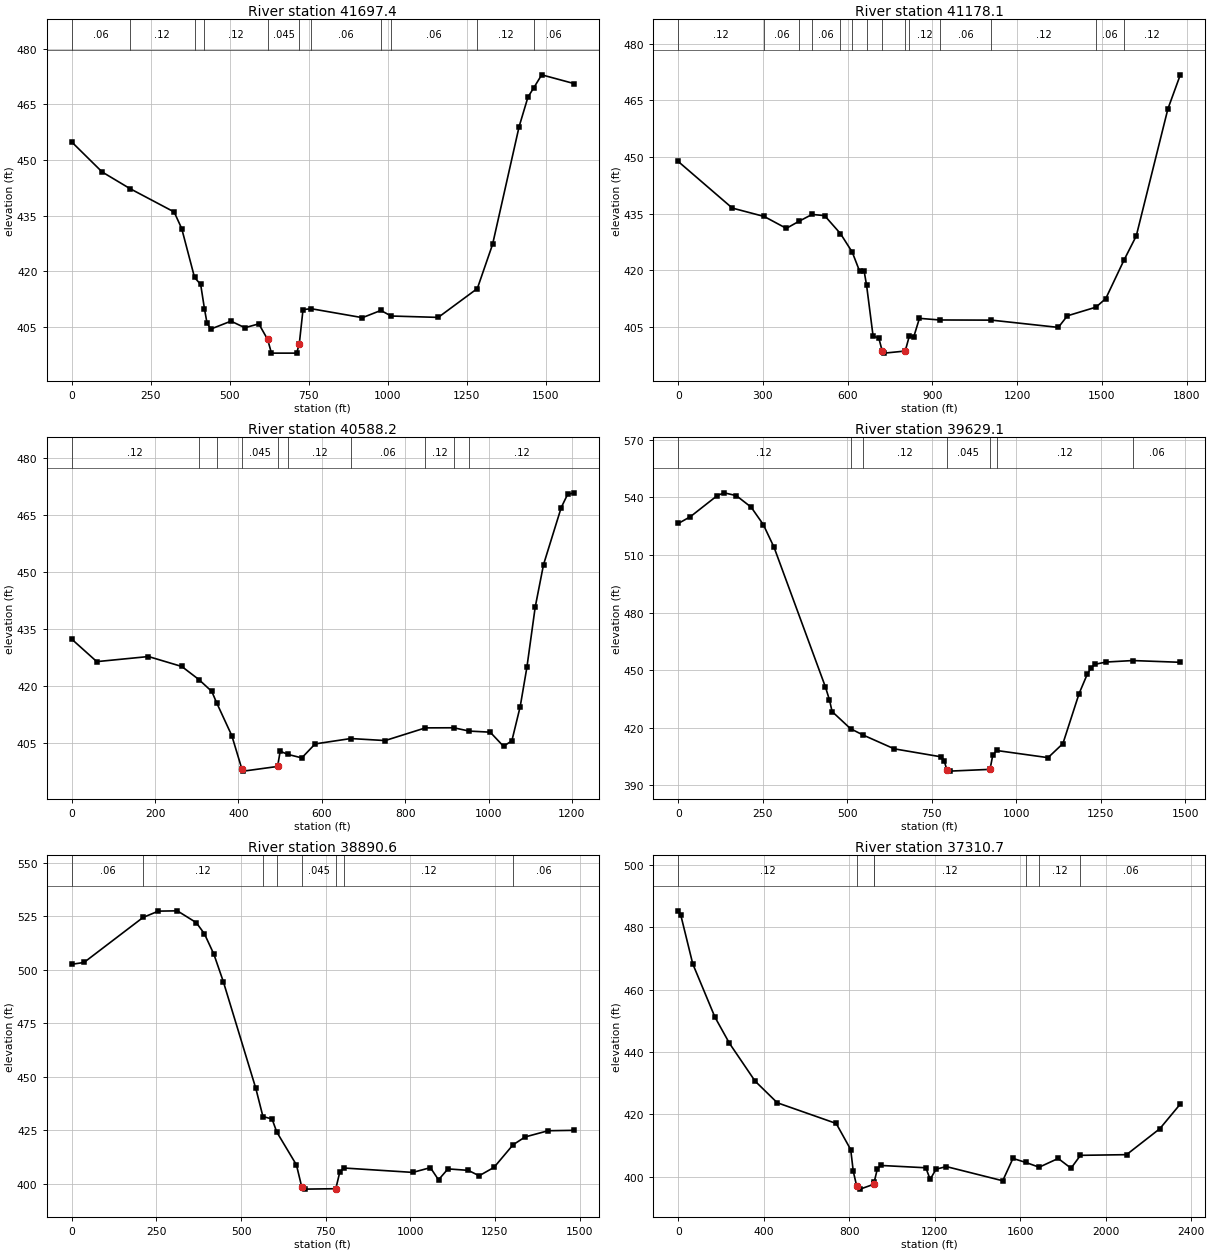
Type RM Length L Ch R = 1 ,41697.4 ,517.9,519.4,520.8
XS GIS Cut Line= 3
     2385442.771       388031.59     2386640.688      388871.868
     2386744.855      388941.312
#Sta/Elev= 30
       0  454.83      96  446.77   184.4442.2725   323.8     436   347.8  431.53
  388.45418.3593   407.8  416.48  419.78409.9226   427.8  406.13   439.8  404.47
   503.7   406.6   547.7  404.83   591.7  405.87   619.7  401.67   631.7  397.99
   711.6  397.99  719.82400.5224   731.6  409.72  757.76409.9424   919.5  407.54
  977.96409.4854  1010.2407.9822  1159.4  407.61 1283.04415.3759  1331.3  427.28
  1415.3  458.99  1443.2  466.92 1461.43469.4019  1486.7  472.92  1588.4  470.58
#Mann= 11 ,-1 , 0
       0     .06       0   184.4     .12       0  388.45    .016       0
  419.78     .12       0   619.7    .045       0  719.82     .04       0
  757.76     .06       0  977.96     .12       0  1010.2     .06       0
 1283.04     .12       0 1461.43     .06       0
Bank Sta=619.7,719.82
XS Rating Curve= 0 ,0
Exp/Cntr=0.3,0.1

Type RM Length L Ch R = 1 ,41178.1 ,577.7,589.9,602.1
XS GIS Cut Line= 3
     2384845.549      388370.131     2385390.292      388575.377
      2386362.91      389271.173
#Sta/Elev= 30
       0   448.8   191.4  436.45  304.16434.2268   382.8  431.07  427.95432.9612
  473.96434.7657   518.3  434.45   574.5429.6761  616.19424.7705   642.1  419.75
   658.1  419.83  666.92416.0143   690.1  402.47   710.1  402.03   722.1  398.62
   730.1  397.99   803.8398.5447  818.02 402.436   834.1  402.32   854.1  407.21
  926.13406.7807 1109.16  406.74    1346  404.81    1378  407.88 1479.31410.1793
    1514  412.45 1578.06422.5747    1622  429.06    1734  462.74    1778  471.78
#Mann= 14 ,-1 , 0
       0     .12       0  304.16     .06       0  427.95     .12       0
  473.96     .06       0   574.5     .12       0  616.19    .016       0
  666.92     .12       0   722.1    .045       0   803.8     .04       0
  818.02     .12       0  926.13     .06       0 1109.16     .12       0
 1479.31     .06       0 1578.06     .12       0
Bank Sta=722.1,803.8
XS Rating Curve= 0 ,0
Exp/Cntr=0.3,0.1

Type RM Length L Ch R = 1 ,40588.2 ,960.2,959,958.4
XS GIS Cut Line= 3
     2384817.771      388691.312     2385493.498      389619.223
     2385522.632      389667.875
#Sta/Elev= 30
       0  432.38      60  426.47     184  427.81     264  425.19   304.9421.7573
     336  418.61   347.5  415.65     384  406.97     408  398.23     412  397.63
  493.83398.8609     500  402.87  519.04402.0156   551.9  401.12   583.9   404.8
  669.39406.2123   751.9  405.68  848.45 409.021  916.54409.0492  953.42408.1786
  1003.9  407.89  1035.9  404.17  1055.9  405.62  1075.9  414.64  1091.9  424.93
  1111.9  440.83  1131.9  452.04  1174.3  467.05  1189.5   470.5  1204.6  470.93
#Mann= 10 ,-1 , 0
       0     .12       0   304.9    .016       0   347.5     .12       0
     408    .045       0  493.83     .04       0  519.04     .12       0
  669.39     .06       0  848.45     .12       0  916.54     .06       0
  953.42     .12       0
Bank Sta=408,493.83
XS Rating Curve= 0 ,0
Exp/Cntr=0.3,0.1

Type RM Length L Ch R = 1 ,39629.1 ,740.4,738.5,736.1
XS GIS Cut Line= 2
     2383712.737      388522.041     2384502.667      389780.722
#Sta/Elev= 30
       0  526.41      36  529.96   115.8  540.99   135.8  542.39   171.8  540.94
   215.7  534.93   251.7  525.87   283.6     514   435.4  441.34   447.4   434.6
   455.4  428.41  509.88419.4862  546.81416.2037   639.2  408.99     779  404.79
     787   402.8   794.9  398.14   802.9  397.37   922.8  398.29   930.8  405.57
  942.15 408.128  1094.5  404.39  1138.5  411.71  1186.4  437.77  1210.4  447.79
  1222.4  451.31  1234.4  453.08  1266.3  454.21 1344.96454.9907    1486  454.08
#Mann= 7 ,-1 , 0
       0     .12       0  509.88    .016       0  546.81     .12       0
   794.9    .045       0   922.8     .04       0  942.15     .12       0
 1344.96     .06       0
Bank Sta=794.9,922.8
XS Rating Curve= 0 ,0
Exp/Cntr=0.3,0.1

Type RM Length L Ch R = 1 ,38890.6 ,1622.2,1579.9,1537.6
XS GIS Cut Line= 2
     2382972.897      388802.367     2383938.431      389928.291
#Sta/Elev= 30
       0  502.49      36  503.33  210.69524.3972   255.9  527.34   311.8  527.48
   367.8  521.96   391.8  516.76   419.8   507.2   447.8  494.33   543.7  444.46
  564.71431.3107   591.7  430.15   605.6424.0627   663.6  408.73   679.6  398.26
   687.6  397.37  779.99397.5658   791.6  405.24  803.79407.2443  1007.5  405.19
  1059.4  407.41  1083.4  401.73  1111.4  406.83  1171.4  406.14  1203.4  403.61
  1247.4  407.54 1303.51418.0873  1339.3  421.77  1407.3  424.67  1483.2  424.86
#Mann= 8 ,-1 , 0
       0     .06       0  210.69     .12       0  564.71    .016       0
   605.6     .12       0   679.6    .045       0  779.99     .04       0
  803.79     .12       0 1303.51     .06       0
Bank Sta=679.6,779.99
XS Rating Curve= 0 ,0
Exp/Cntr=0.3,0.1

Type RM Length L Ch R = 1 ,37310.7 ,2689.3,2626.6,2563.5
XS GIS Cut Line= 2
     2381712.481      390620.075     2383981.834      390015.097
#Sta/Elev= 30
       0  485.23      12  483.84    67.9  468.24   171.8  451.15   239.6  442.78
   359.5  430.67   463.3  423.73   738.9   417.1   806.8  408.72   818.8  401.75
   834.8  397.04   850.8  396.06   914.7  397.62  916.42398.2736   930.7  402.35
   946.6  403.65  1158.3   402.9  1178.3   399.2  1206.3  402.46  1254.2  403.28
  1517.8  398.74  1565.7  405.89 1624.66404.6358 1688.47403.0863  1777.4  405.89
  1837.4  402.75 1881.51406.8878    2097   407.1  2252.8  415.42  2348.6  423.32
#Mann= 7 ,-1 , 0
       0     .12       0   834.8    .045       0   914.7     .04       0
  916.42     .12       0 1624.66     .06       0 1688.47     .12       0
 1881.51     .06       0
Bank Sta=834.8,914.7
XS Rating Curve= 0 ,0
Exp/Cntr=0.3,0.1

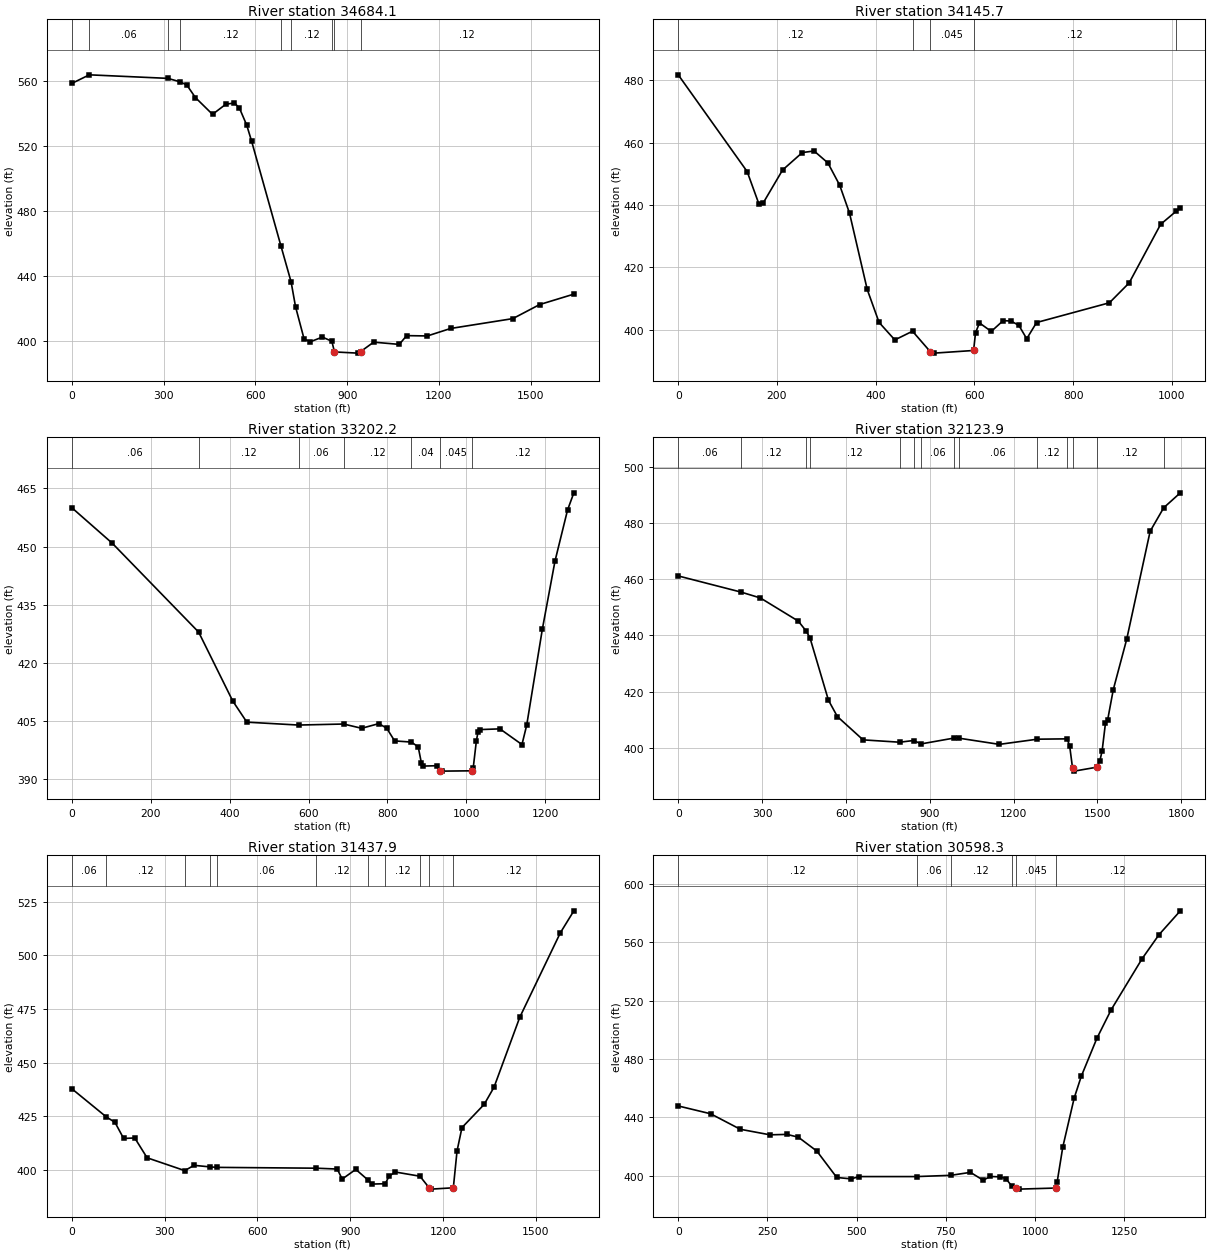
Type RM Length L Ch R = 1 ,34684.1 ,540.3,538.4,537
XS GIS Cut Line= 3
     2384347.897        391510.7     2384561.947      391099.027
     2384103.362      390015.097
#Sta/Elev= 30
       0  558.58   57.36 563.886  313.99561.7051  353.93559.5731     376  557.62
     404   549.9     460  539.54   503.9  545.83   531.8  546.51   547.8  543.45
   571.7  532.93   587.7  523.05  683.72458.4148  716.79436.3647   731.3  421.06
   759.2  401.24   779.2  399.43   819.1  402.34  849.96399.7606  858.62393.1968
   934.8  392.46  943.72393.3574   986.6  399.22  1070.4  397.84  1094.4  403.24
  1162.2  403.04    1238  407.64  1441.5  413.72  1529.2  422.38  1640.9   428.8
#Mann= 9 ,-1 , 0
       0     .12       0   57.36     .06       0  313.99    .016       0
  353.93     .12       0  683.72    .016       0  716.79     .12       0
  849.96     .04       0  858.62    .045       0  943.72     .12       0
Bank Sta=858.62,943.72
XS Rating Curve= 0 ,0
Exp/Cntr=0.3,0.1

Type RM Length L Ch R = 1 ,34145.7 ,936.3,943.5,950.7
XS GIS Cut Line= 2
     2385062.355      390902.454     2384632.875      389980.375
#Sta/Elev= 30
       0  481.76   139.6  450.73   163.6  440.25   171.5  440.48   211.4  451.22
   251.3  456.81   275.2  457.33   303.2  453.49   327.1  446.35     347  437.39
   382.9  412.88   406.9  402.31   438.8   396.7  474.68399.4902   510.6  392.93
   518.6  392.46   598.4  393.31   602.3  398.99   610.3  402.15   634.2  399.42
   658.2  402.88   674.1  402.76   690.1  401.37     706  397.07     726  402.28
   873.6  408.62   913.5  414.98   977.3  433.79  1009.1  438.03  1017.2  439.08
#Mann= 5 ,-1 , 0
       0     .12       0  474.68     .04       0   510.6    .045       0
   598.4     .12       0  1009.1     .06       0
Bank Sta=510.6,598.4
XS Rating Curve= 0 ,0
Exp/Cntr=0.3,0.1

Type RM Length L Ch R = 1 ,33202.2 ,1069.2,1078.3,1087.5
XS GIS Cut Line= 3
     2385618.119       390844.09     2385839.473      390653.118
     2385600.757      389702.597
#Sta/Elev= 30
       0  460.05   102.7  450.86  321.55427.9244   407.9  410.15   443.7  404.68
  574.63403.9328  688.86404.1989   734.6   403.1   778.4  404.31   798.3   403.1
   818.2  399.84  860.72399.5409     878  398.29     886  394.16   889.9  393.34
   925.8  393.44   933.8  392.12   937.7  392.04 1013.79392.1229  1017.4  392.89
  1025.4  399.86  1029.4  402.07  1033.4  402.76  1085.1  402.95  1140.9   398.9
  1152.9  403.89  1192.7  428.76  1224.6  446.25  1256.4  459.43  1272.4  463.88
#Mann= 7 ,-1 , 0
       0     .06       0  321.55     .12       0  574.63     .06       0
  688.86     .12       0  860.72     .04       0   933.8    .045       0
 1013.79     .12       0
Bank Sta=933.8,1013.79
XS Rating Curve= 0 ,0
Exp/Cntr=0.3,0.1

Type RM Length L Ch R = 1 ,32123.9 ,685.3,686,686.7
XS GIS Cut Line= 3
     2386399.981      391052.367     2386691.647      390776.325
     2386690.167      389381.416
#Sta/Elev= 30
       0  461.16  226.32455.3687   294.2  453.31   429.6  445.09  458.67441.4344
  471.65439.0486   537.5  416.94   569.4  411.14   661.4  402.85  792.55402.0144
  841.95402.6194  869.48401.4184  986.99403.4931 1004.55403.4486    1149  401.25
 1284.96403.0908  1391.9403.2112  1400.8  400.52 1411.06392.7126  1416.8  391.73
  1496.7  393.11  1508.7  395.42  1516.7  398.93  1528.7  408.82  1536.7  410.06
  1556.7  420.73  1604.6   438.6  1688.6  477.06 1737.09485.4075  1796.5  490.72
#Mann= 14 ,-1 , 0
       0     .06       0  226.32     .12       0  458.67     .06       0
  471.65     .12       0  792.55     .06       0  841.95     .12       0
  869.48     .06       0  986.99     .12       0 1004.55     .06       0
 1284.96     .12       0  1391.9     .04       0 1411.06    .045       0
  1496.7     .12       0 1737.09     .06       0
Bank Sta=1411.06,1496.7
XS Rating Curve= 0 ,0
Exp/Cntr=0.3,0.1

Type RM Length L Ch R = 1 ,31437.9 ,829.3,839.5,849.8
XS GIS Cut Line= 3
     2387345.549      390809.368      2387367.25      389476.902
      2387510.48      389225.166
#Sta/Elev= 30
       0  437.81  110.59 424.786   139.6  422.12   167.6  414.62   203.5  414.87
   243.4  405.63  365.09399.6497     395  402.11  447.34401.3822  470.12401.1602
  789.71400.7814   857.8  400.38   873.8  395.72   917.7  400.22  955.69395.4659
   969.6  393.38 1012.97393.5545  1025.4  397.09  1045.4     399 1125.11397.0418
 1154.02391.7776  1161.1  391.03  1232.9  391.65  1244.9  408.83  1260.8  419.69
  1332.6  430.51  1364.4  438.51  1447.7  471.12  1578.6   510.4  1622.3  520.66
#Mann= 11 ,-1 , 0
       0     .06       0  110.59     .12       0  365.09     .06       0
  447.34     .12       0  470.12     .06       0  789.71     .12       0
  955.69     .04       0 1012.97     .12       0 1125.11     .04       0
 1154.02    .045       0  1232.9     .12       0
Bank Sta=1154.02,1232.9
XS Rating Curve= 0 ,0
Exp/Cntr=0.3,0.1

Type RM Length L Ch R = 1 ,30598.3 ,648.5,652.9,657.3
XS GIS Cut Line= 4
      2387827.32      390783.326     2387938.138      390587.408
     2388213.605      389663.534     2388413.257      389576.729
#Sta/Elev= 30
       0   447.8    90.8  442.44   173.8  431.82     257  428.01   304.8   428.3
   336.6  426.38   388.4  416.86   444.2  398.77     484  397.82   507.9  399.38
  667.69399.3839  763.96400.2426   818.7  402.28   854.5   396.9   874.4  399.44
   902.3   399.2   918.3  397.96   934.1393.0185   946.2  391.35   954.1  390.78
  1057.7  391.52  1061.7  395.52  1077.6  419.65  1109.5  453.22  1129.4  468.15
  1173.2  494.22  1212.9  513.65    1300  548.81  1347.5  565.31  1406.9  581.58
#Mann= 6 ,-1 , 0
       0     .12       0  667.69     .06       0  763.96     .12       0
   934.1     .04       0   946.2    .045       0  1057.7     .12       0
Bank Sta=946.2,1057.7
XS Rating Curve= 0 ,0
Exp/Cntr=0.3,0.1

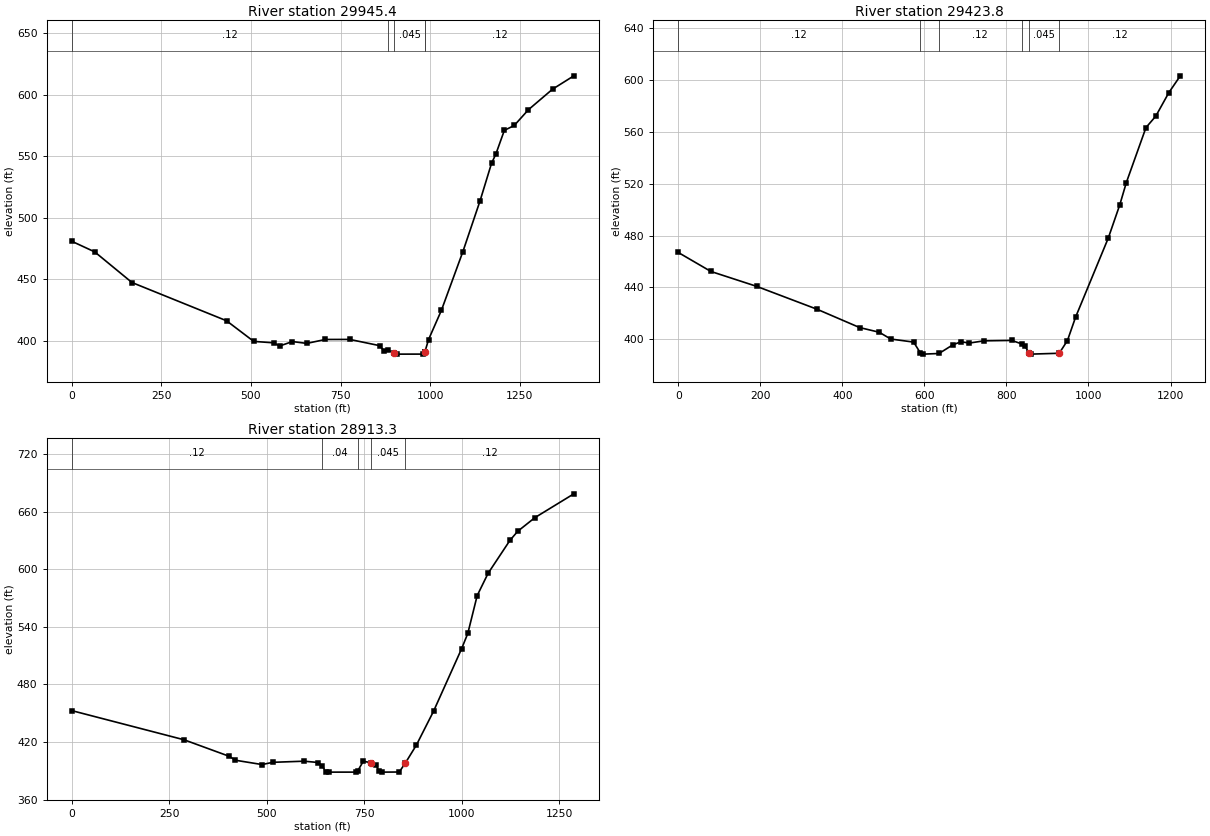
Type RM Length L Ch R = 1 ,29945.4 ,519.7,521.7,523.6
XS GIS Cut Line= 3
     2388381.023      390937.495     2388847.285      389863.187
     2389068.639      389802.423
#Sta/Elev= 30
       0  480.98      64  472.36   167.9   447.5   431.7  416.46   507.6   399.7
   563.6  398.53   579.6  395.94   615.5  399.56   655.5  398.07   707.5  401.26
   775.4   401.3   859.4  396.21   871.4   391.8  882.62392.5422   899.3  390.43
   907.3  389.36   979.3  389.38  985.19391.2936  985.46391.4812   995.3  401.14
  1031.2   424.9  1091.2  472.62  1139.2  513.96  1171.1  544.32    1183  551.65
  1206.8  571.02  1234.4  574.97    1274  587.78  1341.3  604.45  1400.7  615.29
#Mann= 5 ,-1 , 0
       0     .12       0  882.62     .04       0   899.3    .045       0
  985.19     .04       0  985.46     .12       0
Bank Sta=899.3,985.19
XS Rating Curve= 0 ,0
Exp/Cntr=0.3,0.1

Type RM Length L Ch R = 1 ,29423.8 ,495.2,510.4,525.7
XS GIS Cut Line= 3
       2388773.5      391091.486     2388942.771      390870.131
     2389363.778      390023.777
#Sta/Elev= 30
       0  466.94    79.6  452.29   191.1  440.81   338.5  423.14   442.2  409.03
     490  405.42     518  400.19   573.8  397.83  589.69389.7582   597.7  388.55
   635.6 389.035   669.5  395.74   689.5   398.1   709.4  397.08   745.3  398.79
   813.1  399.12  837.22396.4281     845  394.88  854.44389.7492     861  388.57
   928.8  389.22   948.7  398.99   968.7  417.12  1048.4  478.12  1076.4  503.73
  1092.3  520.81  1140.2  563.24  1164.1  572.04    1196  590.21  1223.9  603.13
#Mann= 6 ,-1 , 0
       0     .12       0  589.69     .04       0   635.6     .12       0
  837.22     .04       0  854.44    .045       0   928.8     .12       0
Bank Sta=854.44,928.8
XS Rating Curve= 0 ,0
Exp/Cntr=0.3,0.1

Type RM Length L Ch R = 1 ,28913.3 ,527.1,544.1,561.1
XS GIS Cut Line= 2
     2388981.834      391169.611     2389962.737      390336.277
#Sta/Elev= 30
       0  452.64   287.8  422.26   403.7  405.03   419.7  400.92   487.7  396.45
   515.6  398.78   595.6  399.95   631.6  398.58  642.38394.9188   651.5  388.69
   659.5  388.55   727.5  388.56  733.57390.2254   747.5  399.94   767.5  398.27
   779.4  396.28   787.4     390   795.4  388.55   839.4  388.67   855.4  398.16
   883.4   416.7   927.4  451.97   999.3  517.05  1015.3  533.14  1039.3  572.48
  1067.2  595.64  1123.2  629.98  1143.2  639.48  1187.2   653.7  1287.1  678.52
#Mann= 5 ,-1 , 0
       0     .12       0  642.38     .04       0  733.57     .12       0
   767.5    .045       0   855.4     .12       0
Bank Sta=767.5,855.4
XS Rating Curve= 0 ,0
Exp/Cntr=0.3,0.1