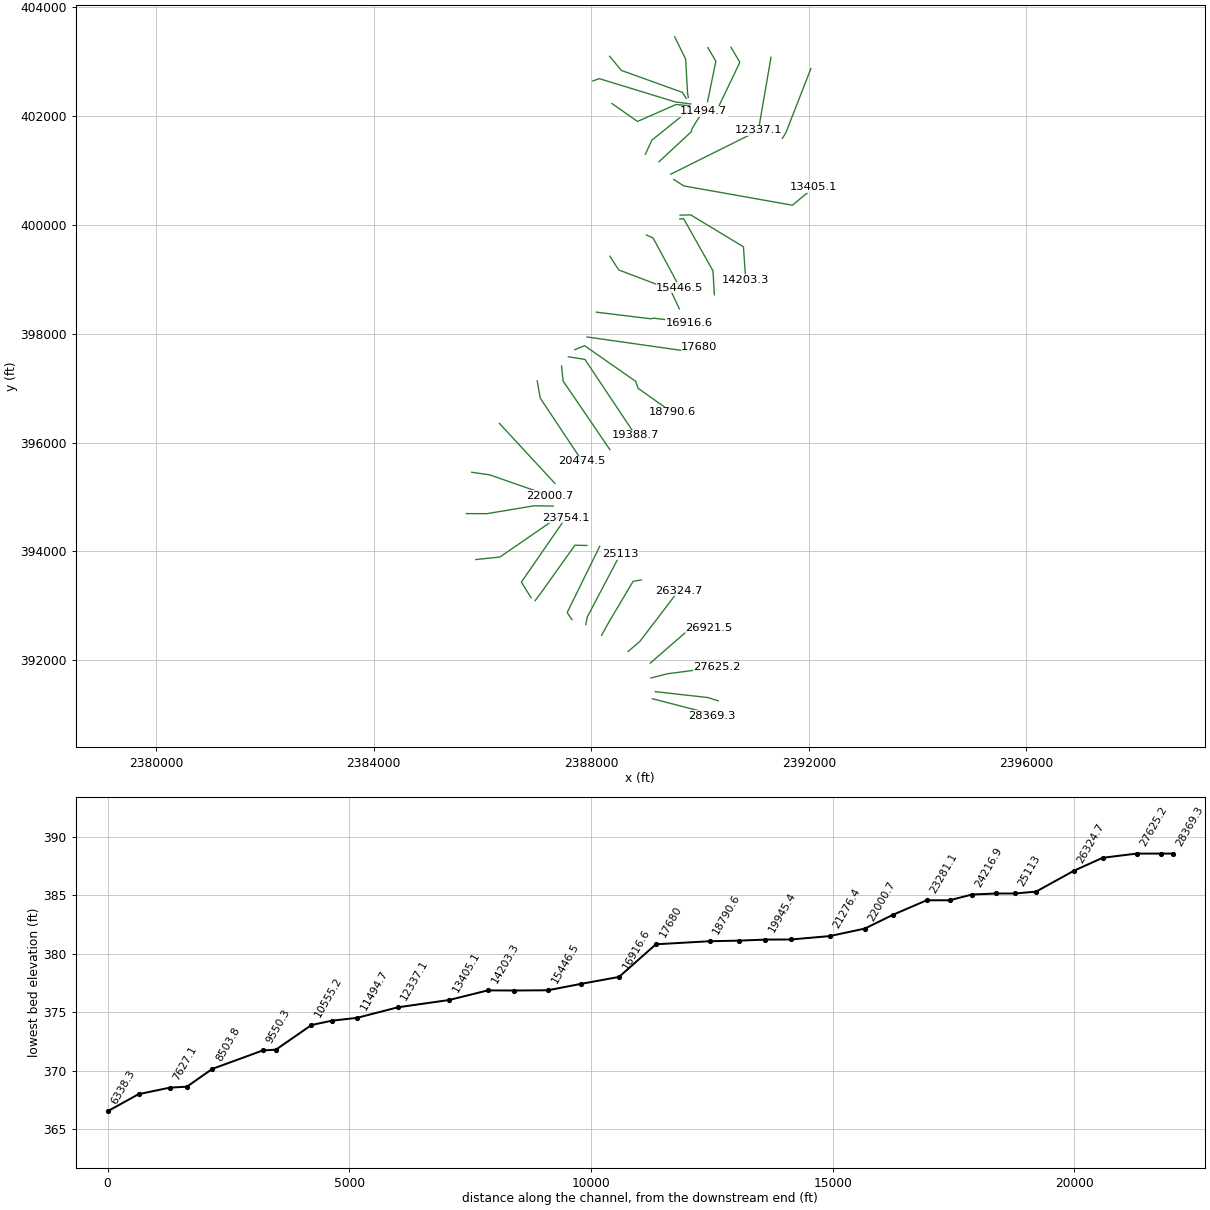
HEC-RAS study BACKCREEK.prj: BACKCREEK

--- BACKCREEK.g01 (geometry) --- (continued)

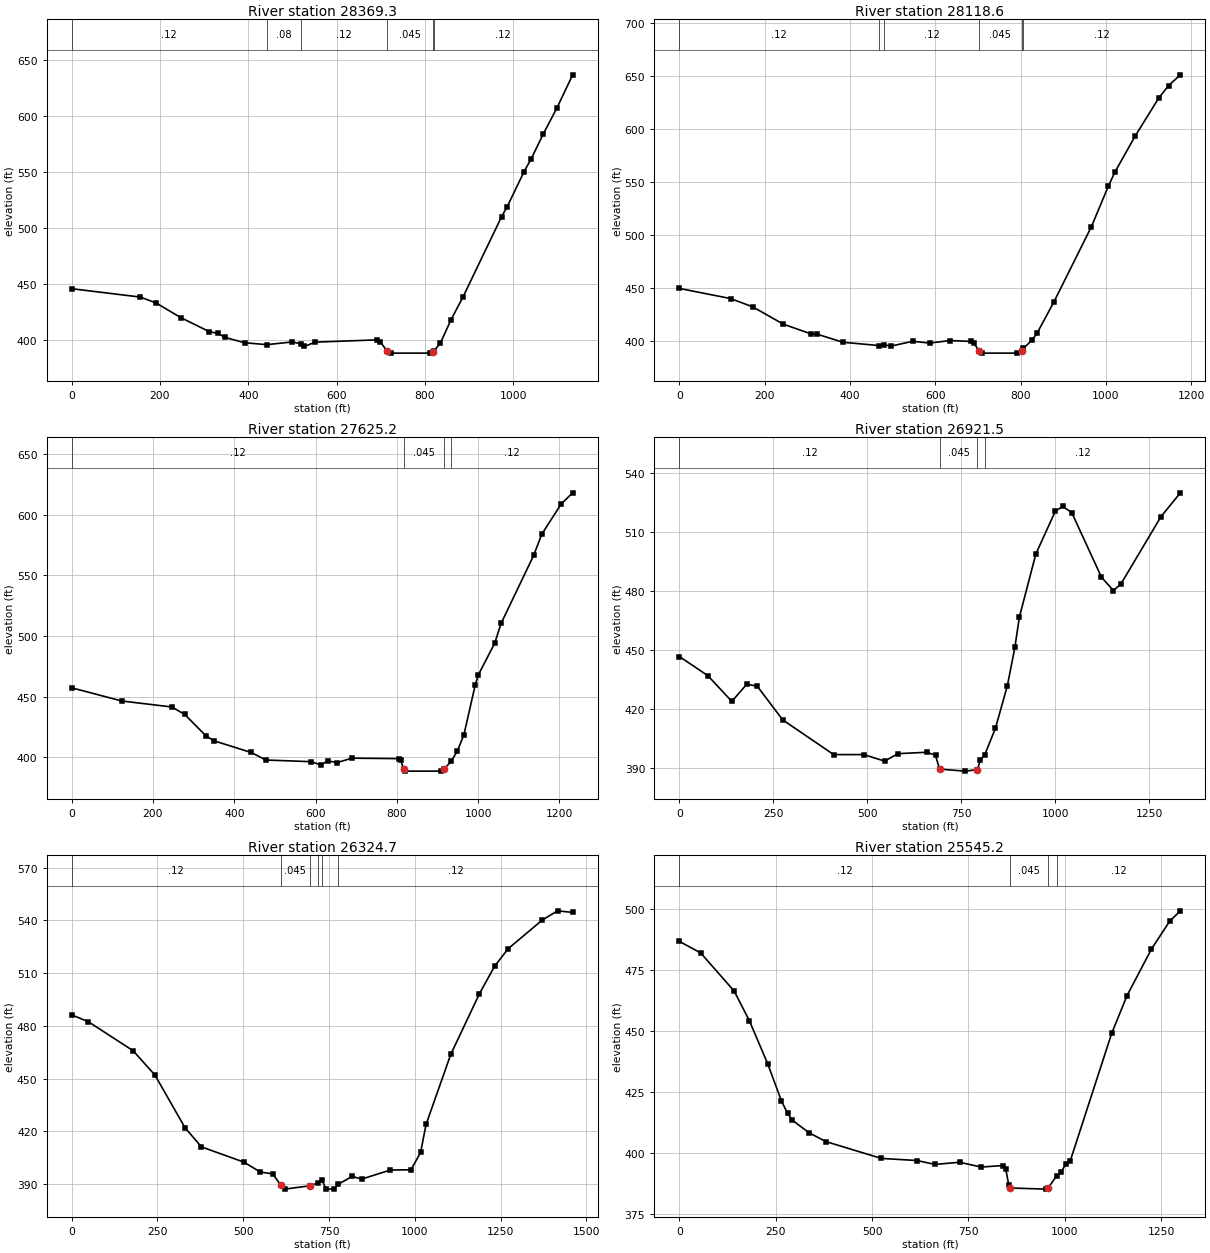
Type RM Length L Ch R = 1 ,28369.3 ,245.3,250.7,256.1
XS GIS Cut Line= 3
     2389125.063      391291.138      2390014.82      391061.104
     2390214.473      390978.638
#Sta/Elev= 30
       0  446.07   155.8  438.59   191.8  433.22   247.7  420.13   311.7  407.75
   331.6  406.11   347.6  402.54   391.6  397.83  442.04 396.113   499.5  398.54
  518.63 396.941   527.4  394.58   551.4  398.35   691.3  400.38   699.2  398.54
   715.2   390.1   723.2  388.55   811.1  388.56   819.1   389.9  819.88390.1964
   835.1  397.31   859.1  418.12     887  439.04     974   510.4   985.8   518.6
  1025.1  550.71  1040.8  561.82  1068.3   584.1  1099.7  607.71    1135  637.05
#Mann= 6 ,-1 , 0
       0     .12       0  442.04     .08       0  518.63     .12       0
   715.2    .045       0   819.1     .04       0  819.88     .12       0
Bank Sta=715.2,819.1
XS Rating Curve= 0 ,0
Exp/Cntr=0.3,0.1

Type RM Length L Ch R = 1 ,28118.6 ,484.3,493.3,502.3
XS GIS Cut Line= 3
     2389177.146      391421.347     2390145.028       391312.84
        2390336.      391252.076
#Sta/Elev= 30
       0  449.66   119.8   440.1   171.6  432.32   243.5  415.91   307.4  406.88
   323.3   406.4   383.2  398.81   467.8 395.718   480.6 396.538     495  395.11
   546.8  399.71   586.8  398.08   634.7  400.43   682.6  399.63   690.5  397.75
   702.5  390.75   710.5  388.55   790.3  388.56   802.3  391.02  806.46393.0352
   826.3  400.74   838.2  407.18   878.2  437.15     966  508.14  1005.4  546.14
  1021.1  559.73  1068.2  593.48  1123.3   629.3  1146.8  641.36  1174.4  651.48
#Mann= 6 ,-1 , 0
       0     .12       0   467.8     .08       0   480.6     .12       0
   702.5    .045       0   802.3     .04       0  806.46     .12       0
Bank Sta=702.5,802.3
XS Rating Curve= 0 ,0
Exp/Cntr=0.3,0.1

Type RM Length L Ch R = 1 ,27625.2 ,681.5,703.7,725.9
XS GIS Cut Line= 3
     2389099.021      391673.083     2389407.181      391751.208
     2390314.299      391868.395
#Sta/Elev= 30
       0  457.28   123.2   446.4   246.4  441.46   278.2  435.28   329.9  417.77
   349.9  413.57   441.7  403.92   477.7  397.72   589.5  396.34   613.5  393.61
   629.4  397.04   653.4  395.61   689.4  399.24   805.2  398.86   809.2  397.86
   817.2     390   821.2  388.55     909  388.55     917   390.5  933.84 396.725
     949  405.13     965  418.45   992.9  459.69  1000.9  468.13  1040.8   494.1
  1056.8  510.61  1136.7  566.52  1156.7  584.06  1204.6     609  1232.6  618.13
#Mann= 4 ,-1 , 0
       0     .12       0   817.2    .045       0     917     .04       0
  933.84     .12       0
Bank Sta=817.2,917
XS Rating Curve= 0 ,0
Exp/Cntr=0.3,0.1

Type RM Length L Ch R = 1 ,26921.5 ,588.9,596.8,604.6
XS GIS Cut Line= 3
        2389086.       391946.52      2389858.57      392619.263
      2390166.73      392597.562
#Sta/Elev= 30
       0  446.61    75.7  436.86   139.5  423.74   179.4  432.55   207.3  431.44
     275  414.31   410.6  396.62   490.3  396.62   546.1  393.32     582   397.1
   657.7   397.8   681.6   396.3  692.28389.2163   760.3  388.19   793.2  388.91
   801.2     394  812.88396.6216   841.1  410.03     873  431.83   892.9  451.32
   904.8  466.68   948.7  498.91  1000.5  520.73  1020.4  523.15  1044.2  520.04
  1123.4  487.07  1155.1  480.29  1174.9  483.52  1281.9  517.99  1333.4   530.1
#Mann= 4 ,-1 , 0
       0     .12       0  692.28    .045       0   793.2     .04       0
  812.88     .12       0
Bank Sta=692.28,793.2
XS Rating Curve= 0 ,0
Exp/Cntr=0.3,0.1

Type RM Length L Ch R = 1 ,26324.7 ,774.9,779.5,784.2
XS GIS Cut Line= 3
     2388678.014      392159.194     2388895.028      392345.826
     2389606.834      393278.986
#Sta/Elev= 30
       0  486.17    47.7  482.41   178.9  465.82   242.5  451.98   330.1  422.05
     378  411.12   501.8  402.44   549.7  396.79   585.6  395.78   609.6   389.3
   621.6   387.1   693.4  388.96  716.69390.5711  729.58392.0895   741.3  387.13
   765.3  387.08  776.37389.7724   817.2  394.33   845.1   392.8   928.9  397.95
   988.8  398.08  1016.8  407.96  1032.7  423.87  1104.6  463.68  1188.4  498.29
  1232.3  513.84  1272.2  523.89    1372  540.24    1416   545.4  1459.9  544.49
#Mann= 6 ,-1 , 0
       0     .12       0   609.6    .045       0   693.4     .04       0
  716.69     .12       0  729.58     .04       0  776.37     .12       0
Bank Sta=609.6,693.4
XS Rating Curve= 0 ,0
Exp/Cntr=0.3,0.1

Type RM Length L Ch R = 1 ,25545.2 ,430.6,432.2,433.8
XS GIS Cut Line= 4
     2388191.903      392458.673     2388293.403       392645.87
      2388769.16      393448.256      2388921.07      393474.298
#Sta/Elev= 30
       0   486.9    55.2  482.16     142  466.54   181.4   454.4   228.9  436.77
   264.8  421.41   280.7  416.35   292.7  413.59   336.5   408.4   380.4  404.78
   523.9   397.9   615.6  397.04   663.4  395.44   727.2  396.32     783  394.35
   838.8  394.97   846.8  393.53   854.8  386.89   858.8  385.77   950.4   385.3
  956.14385.6028  978.47390.6936   990.3  392.13  1002.3  395.58  1014.2  396.91
  1121.8  449.25  1161.6  464.71  1224.8  483.73  1272.2  495.19  1299.9  499.44
#Mann= 4 ,-1 , 0
       0     .12       0   858.8    .045       0  956.14     .04       0
  978.47     .12       0
Bank Sta=858.8,956.14
XS Rating Curve= 0 ,0
Exp/Cntr=0.3,0.1

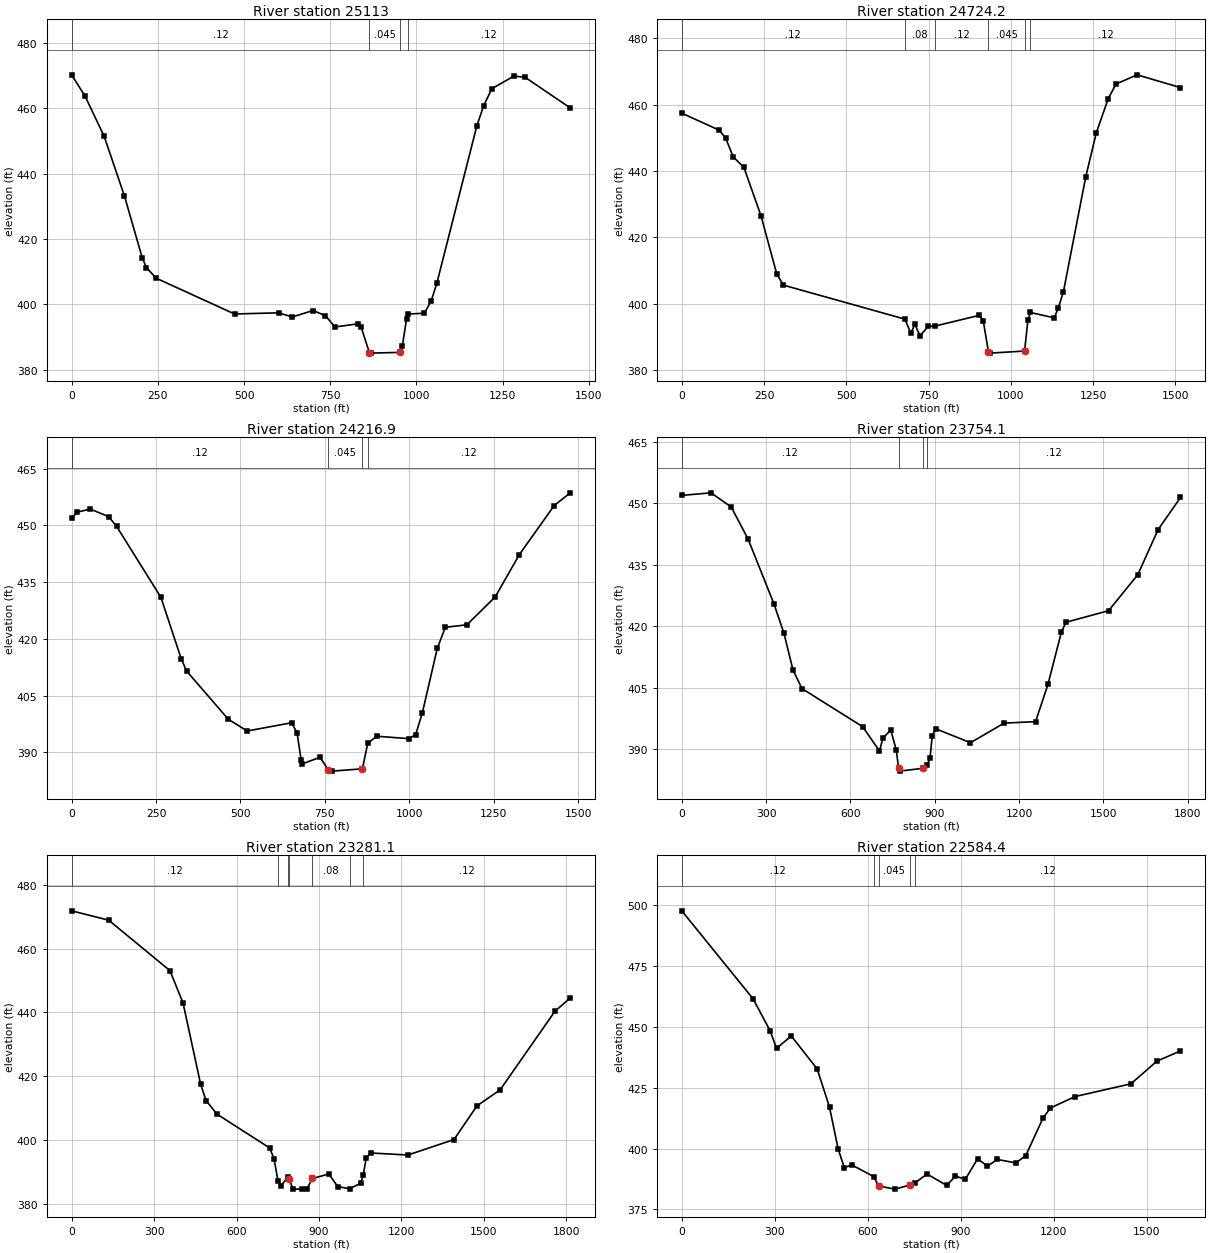
Type RM Length L Ch R = 1 ,25113   ,387.8,388.8,389.8
XS GIS Cut Line= 3
     2387901.105      392653.986     2387927.146      392792.875
     2388534.785      393947.388
#Sta/Elev= 30
       0  470.16    39.2  463.61    94.2  451.43   153.3  433.13   205.2  414.12
   217.1  411.26     245  408.04   472.5   397.1   600.1  397.45     640  396.19
   699.9  398.16   735.8  396.59   763.7  393.13   831.5  394.11   839.5   393.1
   863.5  385.26   867.4  385.14  952.92385.3693   959.2  387.41   971.2  395.59
  975.83397.0729    1023  397.34    1043  401.17    1059  406.48  1174.7  454.43
  1194.6  460.68  1218.6  465.94  1282.4  469.75  1314.3  469.45    1446  460.04
#Mann= 4 ,-1 , 0
       0     .12       0   863.5    .045       0  952.92     .04       0
  975.83     .12       0
Bank Sta=863.5,952.92
XS Rating Curve= 0 ,0
Exp/Cntr=0.3,0.1

Type RM Length L Ch R = 1 ,24724.2 ,516.8,507.3,497.8
XS GIS Cut Line= 3
     2387645.028      392745.131     2387558.223       392875.34
     2388157.181      394094.958
#Sta/Elev= 30
       0  457.41   113.5   452.3     133  449.96   156.5  444.19   188.5  441.14
   240.4  426.58   288.4  409.05   308.4  405.63  678.02395.3722     696   391.1
     708  393.87     724  390.32     748  393.17  768.44393.2575   903.8  396.52
   915.8  394.96   931.8  385.46   935.8  385.14 1041.49385.7665  1051.7  395.16
 1059.19397.3773  1131.6  395.77  1143.6   398.6  1159.6  403.67  1227.5   438.3
  1259.5  451.52  1295.4  461.72  1319.4  466.19  1383.4  468.96  1515.2  465.12
#Mann= 6 ,-1 , 0
       0     .12       0  678.02     .08       0  768.44     .12       0
   931.8    .045       0 1041.49     .04       0 1059.19     .12       0
Bank Sta=931.8,1041.49
XS Rating Curve= 0 ,0
Exp/Cntr=0.3,0.1

Type RM Length L Ch R = 1 ,24216.9 ,459.1,462.8,466.5
XS GIS Cut Line= 4
     2386969.441      393093.866     2387075.621      393235.143
     2387700.579      394112.941     2387922.806      394107.979
#Sta/Elev= 30
       0  451.88    15.7  453.48      55  454.34     110  452.31   133.5  449.72
   264.5  430.98   324.4  414.79   340.4  411.52   464.1  398.75     520  395.66
   651.6  397.84   667.6  395.16   679.6     388   683.6  386.99   735.5   388.7
   759.4  385.47   771.4  385.05  861.02385.6624  876.81392.3735   903.1  394.27
   998.9  393.64  1018.8  394.71  1038.8  400.54  1082.7  417.49  1106.6  423.07
  1170.5  423.73  1254.3  431.11  1325.7  442.28  1428.9  455.26  1476.6  458.62
#Mann= 4 ,-1 , 0
       0     .12       0   759.4    .045       0  861.02     .04       0
  876.81     .12       0
Bank Sta=759.4,861.02
XS Rating Curve= 0 ,0
Exp/Cntr=0.3,0.1

Type RM Length L Ch R = 1 ,23754.1 ,486.7,472.9,459.2
XS GIS Cut Line= 3
     2386894.772      393146.117     2386716.209      393435.236
     2387532.181      394615.791
#Sta/Elev= 30
       0  451.97   103.9   452.6   175.9  449.14   235.9   441.3   327.8   425.5
   363.8  418.22   395.8  409.28   427.8  404.74   643.6  395.43   703.6  389.49
   715.6  392.55   743.6  394.65   763.6  389.65   771.6  385.24   775.5  384.56
   859.5  385.26  873.78386.0013   883.5  387.85   891.5  393.21   903.5  394.93
  1027.4   391.5  1147.3   396.3  1259.2  396.66  1303.2  405.77  1351.2  418.59
  1367.2  420.95  1519.1  423.79    1623  432.59    1695  443.58  1774.9  451.46
#Mann= 4 ,-1 , 0
       0     .12       0   771.6    .045       0   859.5     .04       0
  873.78     .12       0
Bank Sta=771.6,859.5
XS Rating Curve= 0 ,0
Exp/Cntr=0.3,0.1

Type RM Length L Ch R = 1 ,23281.1 ,713.1,696.8,680.5
XS GIS Cut Line= 3
     2385879.147      393849.242     2386321.856      393896.117
     2387449.716      394672.215
#Sta/Elev= 30
       0  471.87   135.1  468.93   357.7  453.11   405.4  442.98   469.1   417.6
   489.1  412.36     529  408.08   720.6  397.48   736.6  394.06  750.97387.0664
   760.5  385.57  787.18388.2755   792.4  387.81   804.4  384.57   838.1  384.56
   856.3  384.64   876.3  387.91   936.1  389.31   968.1  385.36 1011.52384.6768
  1051.9  386.44 1061.13388.9681  1071.8  394.38  1087.8   395.9  1223.5  395.26
  1391.2  400.12    1475   410.7  1558.8  415.68  1758.4  440.35  1814.3  444.55
#Mann= 7 ,-1 , 0
       0     .12       0  750.97     .04       0  787.18     .12       0
   792.4    .045       0   876.3     .08       0 1011.52     .04       0
 1061.13     .12       0
Bank Sta=792.4,876.3
XS Rating Curve= 0 ,0
Exp/Cntr=0.3,0.1

Type RM Length L Ch R = 1 ,22584.4 ,602.7,583.7,564.7
XS GIS Cut Line= 4
     2385704.924      394693.916      2386082.06      394692.372
     2386946.244      394837.145     2387302.146      394832.805
#Sta/Elev= 30
       0  497.73   230.2  461.54   285.8  448.22   305.7  441.16   353.3  446.29
   436.9  432.72   476.7  417.02   504.6  399.78   524.5  392.15   548.4   393.3
  619.88388.4257  635.07384.6094   687.8  383.32   735.6  384.98  751.51385.7707
   791.4  389.53   855.1  384.84     883   388.7   914.8  387.33   954.6  395.78
   986.5  392.78  1018.4  395.52  1078.1   394.1    1110  397.08  1165.7  412.54
  1189.6  416.68  1269.4  421.39  1449.3  426.61  1533.3  435.94  1609.3  440.13
#Mann= 5 ,-1 , 0
       0     .12       0  619.88     .04       0  635.07    .045       0
   735.6     .04       0  751.51     .12       0
Bank Sta=635.07,735.6
XS Rating Curve= 0 ,0
Exp/Cntr=0.3,0.1

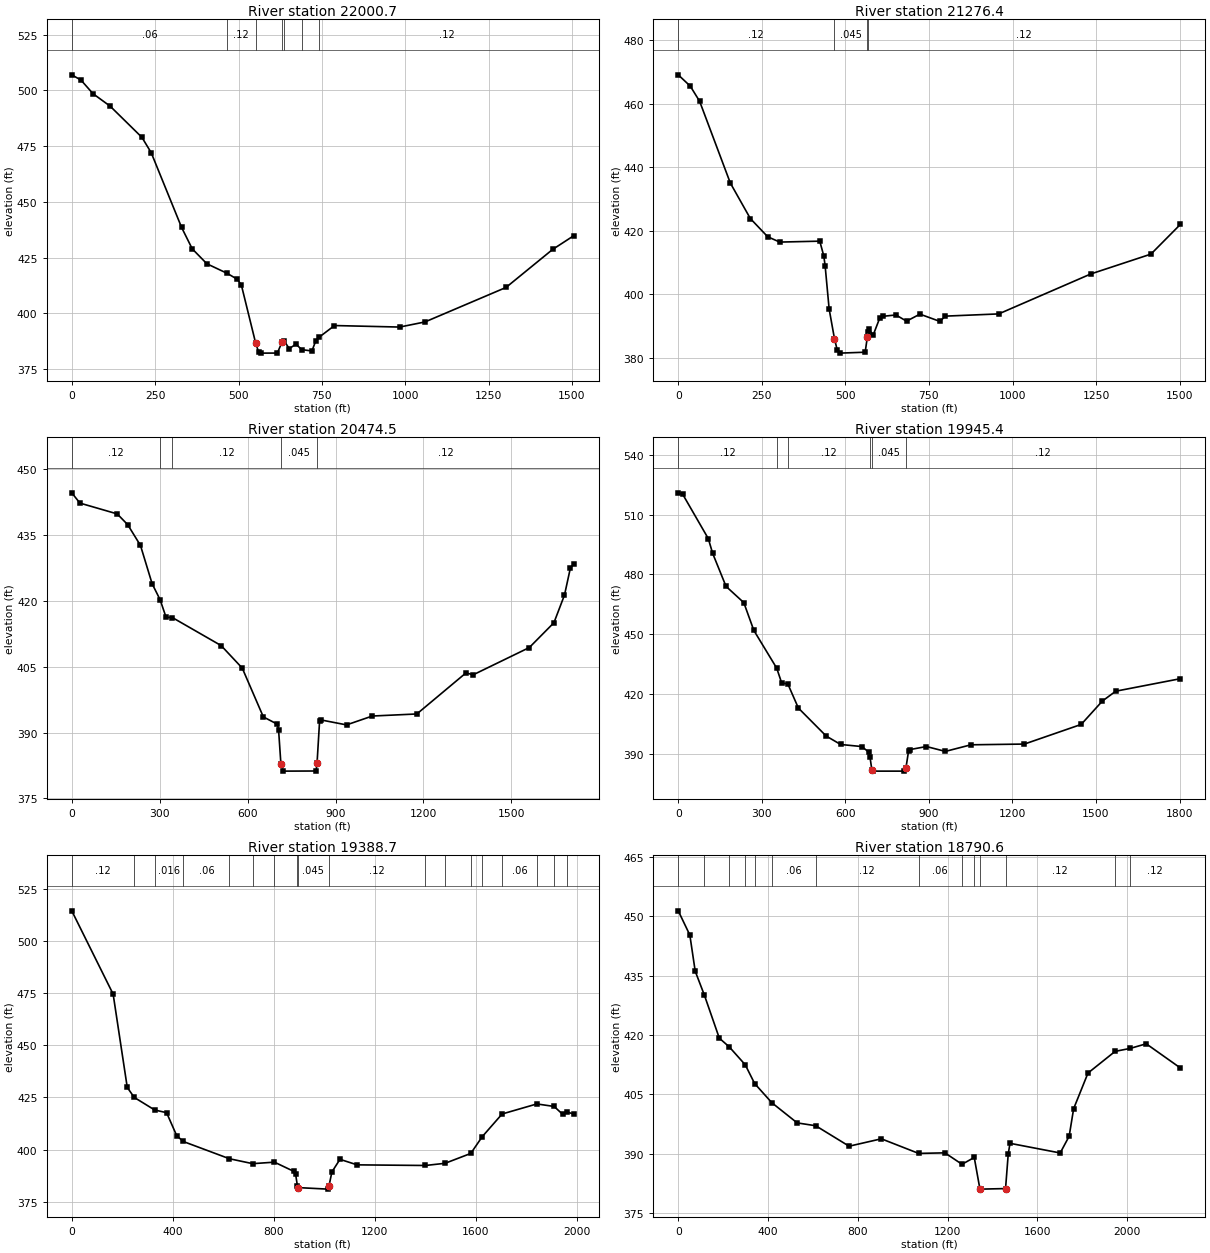
Type RM Length L Ch R = 1 ,22000.7 ,742.8,724.3,705.9
XS GIS Cut Line= 3
      2385804.75      395453.465     2386134.612      395405.722
     2387241.382      395019.437
#Sta/Elev= 30
       0  506.94    27.8  504.56    63.5   498.5   115.1  492.88   210.3  478.91
   238.1  472.05   329.3  438.51   361.2  428.91   405.1  422.21  465.87417.9221
   496.8  415.23   508.7  412.57   551.2386.7485   560.6  382.47   568.5  382.14
   616.4  382.17   631.1387.2907   637.3 387.495   652.3  384.14   672.2   386.2
  689.58383.6982   720.1  383.11     732  387.77  741.22389.2249   787.8  394.51
   983.2  393.83    1059  396.12  1302.2   411.6  1441.8  428.63  1505.5  434.82
#Mann= 7 ,-1 , 0
       0     .06       0  465.87     .12       0   551.2    .045       0
   631.1     .04       0   637.3     .12       0  689.58     .08       0
  741.22     .12       0
Bank Sta=551.2,631.1
XS Rating Curve= 0 ,0
Exp/Cntr=0.3,0.1

Type RM Length L Ch R = 1 ,21276.4 ,807.9,801.9,795.9
XS GIS Cut Line= 2
     2386312.563      396351.902     2387332.528      395249.472
#Sta/Elev= 30
       0  469.14      36  465.58    63.9  460.83   155.8  435.07   215.7  423.88
   267.6  418.15   303.6  416.47   423.4  416.76   435.4   412.1   439.4  409.02
   451.4   395.4   467.3  386.07   475.3  382.61   483.3   381.5   559.2  381.79
   565.5 386.433  568.23388.1087   571.2  388.97   583.2   387.2   603.2  392.66
   611.1  393.08   651.1  393.52     683  391.57     723  393.78   782.9  391.48
   798.9  393.15   958.7  393.85  1234.3  406.44    1414  412.68  1501.9  422.01
#Mann= 4 ,-1 , 0
       0     .12       0   467.3    .045       0   565.5     .04       0
  568.23     .12       0
Bank Sta=467.3,565.5
XS Rating Curve= 0 ,0
Exp/Cntr=0.3,0.1

Type RM Length L Ch R = 1 ,20474.5 ,528.6,529,529.5
XS GIS Cut Line= 3
     2387007.007      397133.152     2387063.431      396816.312
     2387834.424      395658.021
#Sta/Elev= 30
       0   444.6    27.8  442.26     155   439.8   190.7  437.36   234.4  432.62
   274.2  423.89  301.48420.2468   321.8  416.24   343.3416.1862   509.8   409.8
   581.7  404.68   653.7  393.56   701.7  391.89   705.7  390.61   713.7  382.74
   721.7  381.21   833.6  381.24  837.06383.1344   845.6  392.61   849.6  392.88
   937.6  391.74  1025.5  393.76  1177.5  394.23  1345.4   403.6  1369.4  403.14
  1561.3  409.36  1645.3  415.02  1681.3  421.32  1701.3  427.45  1713.2   428.4
#Mann= 5 ,-1 , 0
       0     .12       0  301.48    .016       0   343.3     .12       0
   713.7    .045       0  837.06     .12       0
Bank Sta=713.7,837.06
XS Rating Curve= 0 ,0
Exp/Cntr=0.3,0.1

Type RM Length L Ch R = 1 ,19945.4 ,556.7,556.7,556.7
XS GIS Cut Line= 3
     2387454.056       397406.59     2387484.438      397128.812
     2388342.689      395870.075
#Sta/Elev= 30
       0  521.03      16  520.31   107.8  498.06   123.8  490.55   171.6  474.04
   235.5  465.85   271.4  451.92  353.62432.9383   371.4  425.51  393.57425.0047
   431.4  412.89   531.4  398.81   583.3  394.59   659.3  393.54   683.3  390.85
  688.45388.3752   695.3  381.78   699.3   381.2   811.3   381.2  817.57382.7401
   827.2   391.4   831.2     392   891.2  393.56   959.2  391.11  1051.2  394.43
  1243.1   394.8    1447  404.67    1523  416.41    1571  421.36  1802.9  427.64
#Mann= 6 ,-1 , 0
       0     .12       0  353.62    .016       0  393.57     .12       0
  688.45     .04       0   695.3    .045       0  817.57     .12       0
Bank Sta=695.3,817.57
XS Rating Curve= 0 ,0
Exp/Cntr=0.3,0.1

Type RM Length L Ch R = 1 ,19388.7 ,607.4,598.1,588.8
XS GIS Cut Line= 3
     2387579.924      397575.861     2387883.744      397528.118
     2388816.647      396130.492
#Sta/Elev= 30
       0  514.33   163.8  474.45   219.7  429.79  247.22425.0213  328.36418.9879
   375.4  417.71   415.3  406.75  441.09403.9268  624.34  395.65  716.39393.3017
  802.39394.0186   878.3  389.66   886.3  388.24  893.74382.3792   894.3  381.85
    1014  381.11    1018  382.38    1030  389.36  1061.9  395.37  1129.8  392.73
 1400.28392.4284  1478.1393.4782 1579.77398.1952 1625.07406.2036 1703.86417.0816
 1841.45421.8888 1909.94420.6846    1944  416.87 1959.73418.1414  1987.9  416.98
#Mann= 18 ,-1 , 0
       0     .12       0  247.22     .06       0  328.36    .016       0
  441.09     .06       0  624.34     .12       0  716.39     .06       0
  802.39     .12       0  893.74     .04       0   894.3    .045       0
    1018     .12       0 1400.28     .08       0  1478.1     .12       0
 1579.77    .016       0 1625.07     .12       0 1703.86     .06       0
 1841.45     .12       0 1909.94     .06       0 1959.73     .12       0
Bank Sta=894.3,1018
XS Rating Curve= 0 ,0
Exp/Cntr=0.3,0.1

Type RM Length L Ch R = 1 ,18790.6 ,1070.2,1110.5,1150.8
XS GIS Cut Line= 5
     2387697.768      397706.057     2387878.009      397780.283
     2388816.647      397125.283     2388863.522      396995.075
     2389483.314      396557.575
#Sta/Elev= 30
       0  451.41    51.7  445.29    75.6  436.15  116.96 430.018     183  419.22
  227.35417.0153  298.51412.4908  340.36407.7503  417.16402.8912   529.9   397.8
  612.34397.0851   761.2  391.91   904.8  393.78  1070.8390.0919    1188  390.23
 1264.13387.3401 1318.65389.0635  1343.5  381.21  1347.4  381.06  1458.1   381.2
    1470  389.92  1477.9  392.64  1701.5   390.2  1741.4  394.43  1761.4  401.39
  1825.3   410.4 1946.08415.8781  2014.1 416.644  2084.8   417.8  2236.6   411.7
#Mann= 14 ,-1 , 0
       0     .12       0  116.96     .06       0  227.35    .016       0
  298.51     .06       0  340.36     .08       0  417.16     .06       0
  612.34     .12       0  1070.8     .06       0 1264.13     .12       0
 1318.65     .04       0  1343.5    .045       0  1458.1     .12       0
 1946.08    .016       0  2014.1     .12       0
Bank Sta=1343.5,1458.1
XS Rating Curve= 0 ,0
Exp/Cntr=0.3,0.1

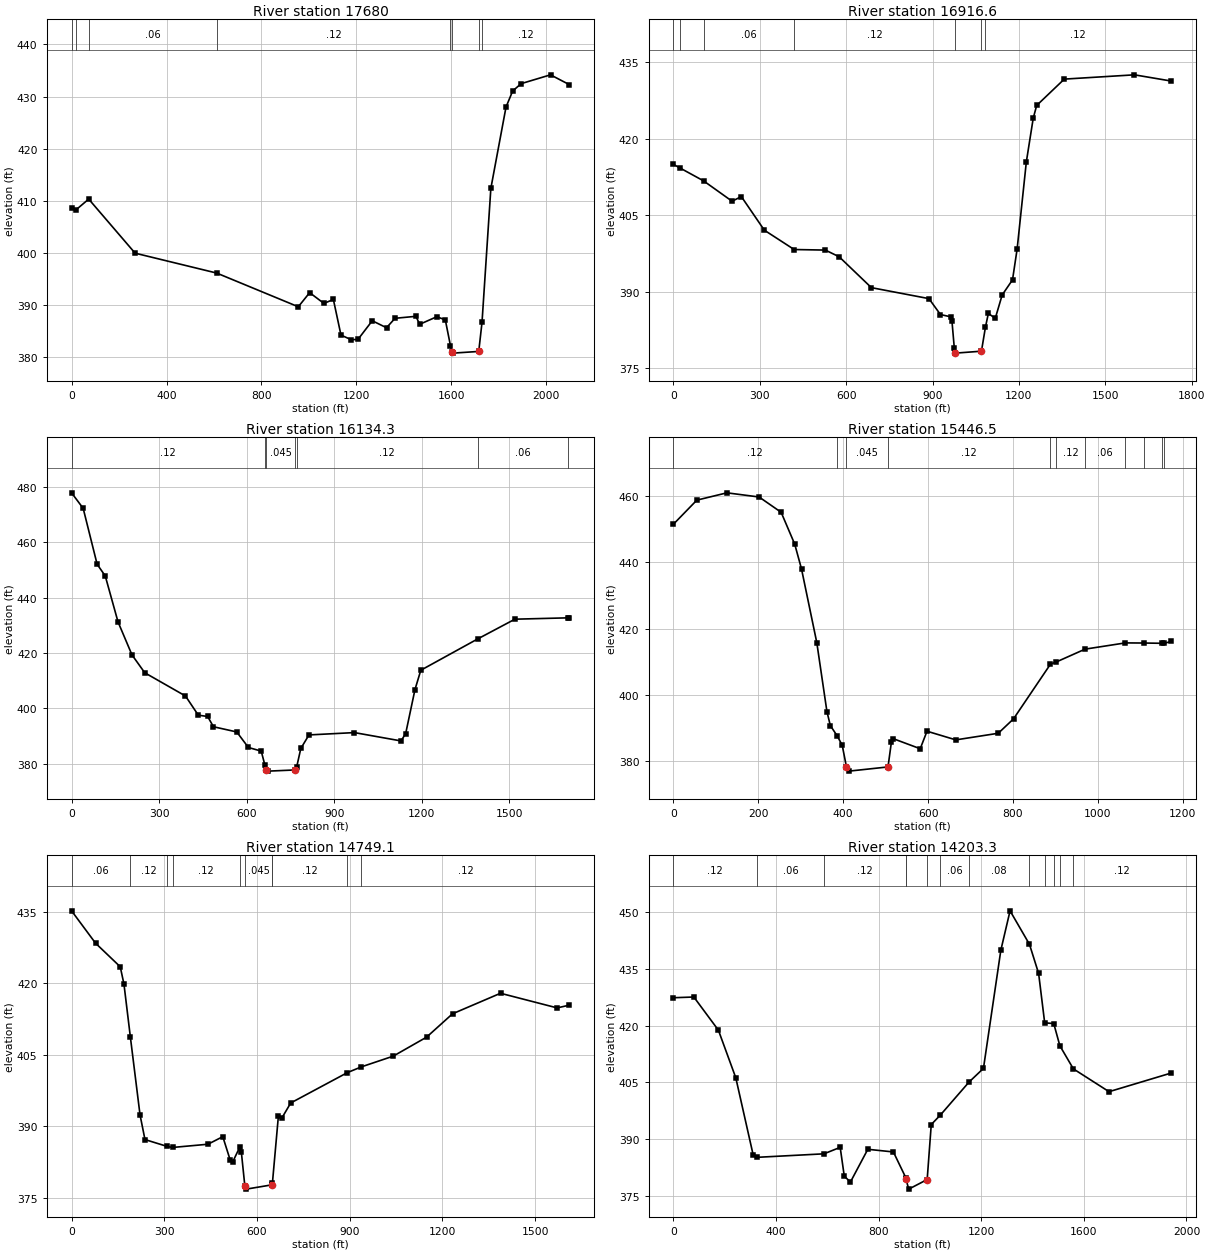
Type RM Length L Ch R = 1 ,17680   ,757.5,763.5,778.4
XS GIS Cut Line= 3
     2387922.806      397940.444     2389754.403      397680.027
     2389988.778      397758.152
#Sta/Elev= 30
       0  408.69    18.1  408.26   72.21410.3446   267.7  399.97  611.14396.1592
     955  389.69  1002.9   392.4  1062.9  390.34  1102.8  391.09  1134.8  384.26
  1178.7  383.36  1206.7  383.45  1266.6  387.01  1326.6  385.67  1362.5  387.48
  1450.4  387.86  1466.4  386.33  1538.4  387.78  1574.3  387.18 1595.94382.2359
  1602.3  380.97  1606.3   380.8 1715.09381.1226 1728.86 386.691  1766.1   412.4
    1830     428    1858  431.08  1893.8  432.49  2017.4  434.18  2097.1  432.29
#Mann= 8 ,-1 , 0
       0     .06       0    18.1     .12       0   72.21     .06       0
  611.14     .12       0 1595.94     .04       0  1602.3    .045       0
 1715.09     .04       0 1728.86     .12       0
Bank Sta=1602.3,1715.09
XS Rating Curve= 0 ,0
Exp/Cntr=0.3,0.1

Type RM Length L Ch R = 1 ,16916.6 ,798,782.3,757.6
XS GIS Cut Line= 4
      2388093.72      398396.196     2389101.822      398274.062
     2389142.086      398287.542     2389807.803      398201.139
#Sta/Elev= 30
       0     415   24.54414.2351  104.81411.7609   203.9  407.77   235.9  408.69
   315.8   402.1  419.43  398.31   527.7   398.2   575.7  396.89   687.6  390.84
   887.5  388.69   927.5  385.57   963.5  385.12   967.5  384.26   975.5  379.08
  979.13 378.109   979.5  378.01  1069.9  378.39 1083.79383.1085  1093.9  385.79
  1117.9  384.82  1141.8   389.4  1177.8  392.37  1193.8   398.4  1225.8  415.48
  1249.7  424.03  1261.7  426.54  1357.6   431.7  1601.4  432.54  1729.2  431.32
#Mann= 7 ,-1 , 0
       0     .06       0   24.54     .12       0  104.81     .06       0
  419.43     .12       0  979.13    .045       0  1069.9     .04       0
 1083.79     .12       0
Bank Sta=979.13,1069.9
XS Rating Curve= 0 ,0
Exp/Cntr=0.3,0.1

Type RM Length L Ch R = 1 ,16134.3 ,712,687.8,663.6
XS GIS Cut Line= 4
     2388343.813      399424.819     2388504.403      399173.083
     2389452.274      398812.949     2389619.855      398456.937
#Sta/Elev= 30
       0  477.74    39.8  472.15    87.6     452   115.5  447.76   159.2  431.22
     207  419.33   250.8  412.88   390.4   404.5   434.3  397.59   466.3  397.12
   486.2  393.42   566.1  391.54     606  385.94   649.9  384.64  662.17379.7277
   665.9   377.9   673.8  377.42   765.7  377.84  771.19378.8063   785.6  385.59
   813.6  390.47   969.3  391.31  1128.9  388.31  1144.9  390.94  1176.8  406.82
  1196.8  413.79  1391.2425.0432  1519.2  432.19 1702.22432.6794  1706.1  432.66
#Mann= 7 ,-1 , 0
       0     .12       0  662.17     .04       0   665.9    .045       0
   765.7     .04       0  771.19     .12       0  1391.2     .06       0
 1702.22     .12       0
Bank Sta=665.9,765.7
XS Rating Curve= 0 ,0
Exp/Cntr=0.3,0.1

Type RM Length L Ch R = 1 ,15446.5 ,697.2,697.4,697.6
XS GIS Cut Line= 3
     2389012.216      399815.444     2389138.084       399759.02
     2389628.535      398847.562
#Sta/Elev= 30
       0  451.53    55.2  458.82   126.1  461.03   201.9  459.77   253.8  455.15
   285.8  445.52   301.8  438.02   337.8  415.76   361.7   394.9   369.7  390.66
   386.2 387.465   397.7   384.7  407.81378.0893   413.7  376.87   505.6  378.14
   513.6  385.65   517.6   386.7   581.5  383.64   597.5  388.94   665.4  386.32
   765.4  388.32   801.3  392.67  888.39409.2232  902.54409.9071  969.82413.7563
 1064.84415.6461 1107.72415.6092 1151.22415.5278 1155.39415.4801    1173   416.1
#Mann= 11 ,-1 , 0
       0     .12       0   386.2     .04       0  407.81    .045       0
   505.6     .12       0  888.39     .06       0  902.54     .12       0
  969.82     .06       0 1064.84    .016       0 1107.72     .12       0
 1151.22     .06       0 1155.39     .12       0
Bank Sta=407.81,505.6
XS Rating Curve= 0 ,0
Exp/Cntr=0.3,0.1

Type RM Length L Ch R = 1 ,14749.1 ,526,545.8,565.5
XS GIS Cut Line= 4
     2389628.535      400110.583      2389697.98      400114.923
     2390237.508       399157.26     2390263.985      398715.995
#Sta/Elev= 30
       0  435.25    77.6  428.46   157.5  423.51   169.5  419.89  190.38408.7058
   221.5  392.44   237.5  387.25  309.95385.8004   326.6 385.593   441.3  386.27
   489.3  387.86   513.2  382.96   521.2  382.53  544.74385.7428   549.2   384.7
   560.6377.5395   565.2  376.85   649.2  377.76  649.91378.1647   669.1  392.13
   681.1  391.85   709.1  394.93  892.69401.3114  937.91402.5125  1040.9  404.76
  1148.8  408.75  1232.5  413.64  1387.8  417.95    1571  414.88  1610.8  415.46
#Mann= 10 ,-1 , 0
       0     .06       0  190.38     .12       0  309.95     .06       0
   326.6     .12       0  544.74     .04       0   560.6    .045       0
   649.2     .04       0  649.91     .12       0  892.69    .016       0
  937.91     .12       0
Bank Sta=560.6,649.2
XS Rating Curve= 0 ,0
Exp/Cntr=0.3,0.1

Type RM Length L Ch R = 1 ,14203.3 ,784.2,798.2,812.2
XS GIS Cut Line= 4
     2389632.875      400180.027     2389828.188      400184.368
     2390797.839      399598.287     2390839.506      398987.176
#Sta/Elev= 30
       0  427.36    79.7  427.55   175.4   418.8   243.2  406.24   311.1  385.84
  325.83385.2507  586.83386.1747   650.2  387.88   666.1  380.29   690.1  378.73
   757.9  387.37   857.6  386.67  905.84379.8951  906.86379.4004   917.5  376.86
   989.3  379.39  1005.2   393.9 1040.62396.3944 1152.44405.1083  1208.7  408.72
  1276.5  439.91  1312.4  450.29 1388.15441.4413  1423.8  433.76 1447.39420.7378
 1482.73420.5469 1506.63414.6791 1559.25408.5873  1698.3  402.57  1940.9   407.5
#Mann= 13 ,-1 , 0
       0     .12       0  325.83     .06       0  586.83     .12       0
  905.84     .04       0  906.86    .045       0   989.3    .016       0
 1040.62     .06       0 1152.44     .08       0 1388.15     .06       0
 1447.39    .016       0 1482.73     .12       0 1506.63     .08       0
 1559.25     .12       0
Bank Sta=906.86,989.3
XS Rating Curve= 0 ,0
Exp/Cntr=0.3,0.1

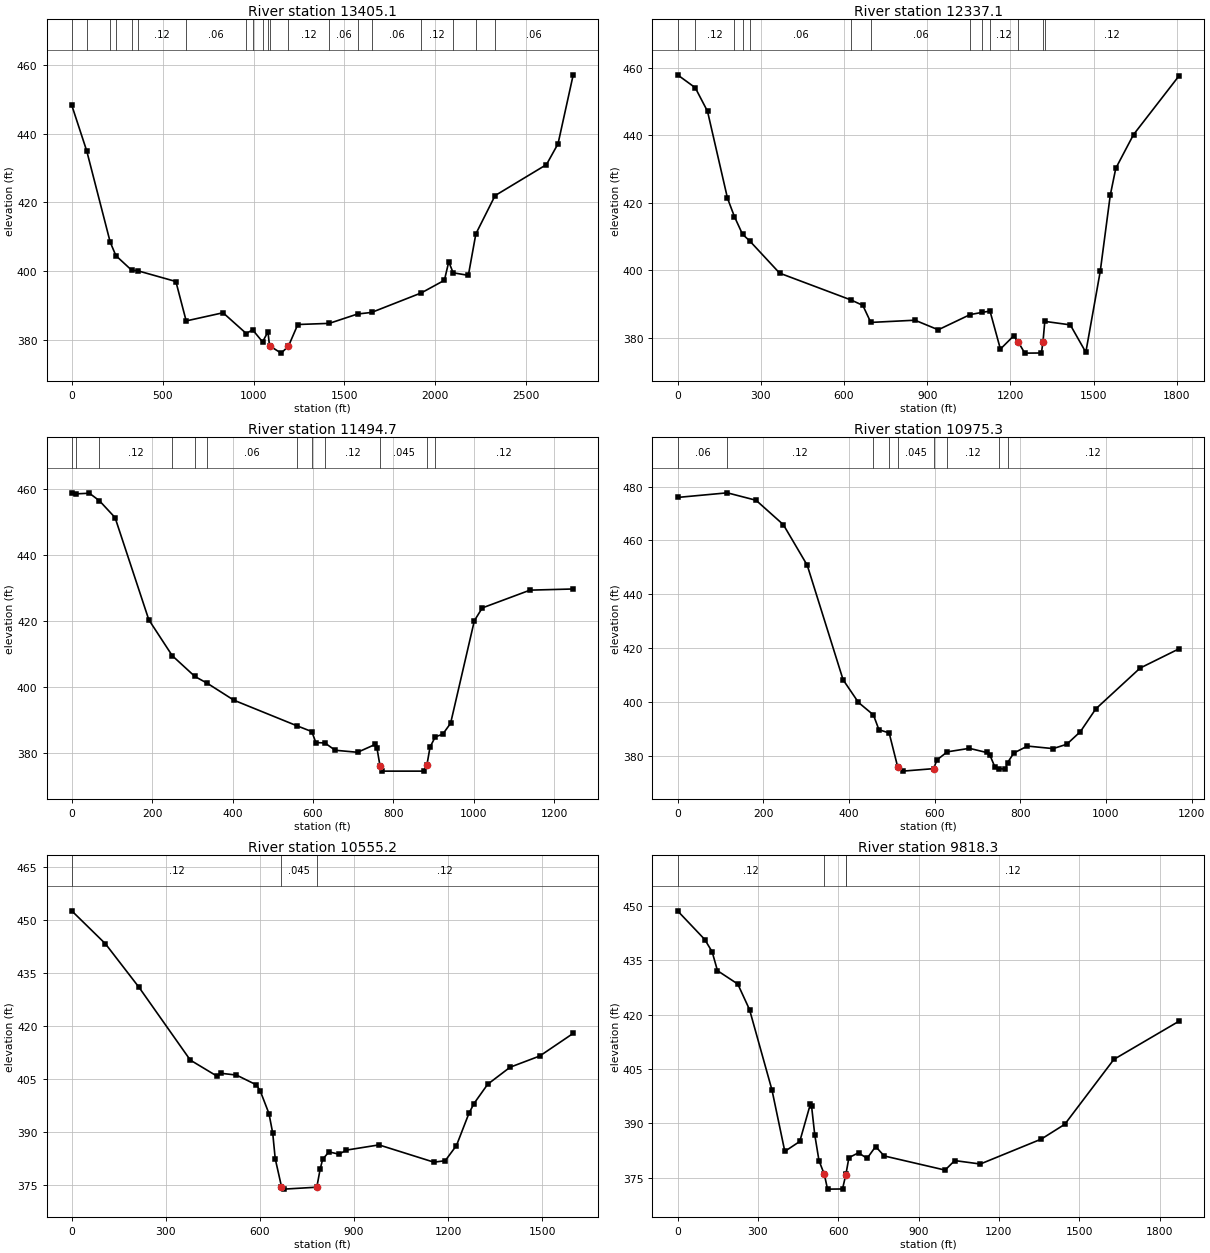
Type RM Length L Ch R = 1 ,13405.1 ,1044.1,1068.1,1092.1
XS GIS Cut Line= 4
     2389516.556      400834.541     2389704.056      400716.486
     2391697.112      400362.319     2392092.945      400688.708
#Sta/Elev= 30
       0  448.39   82.57 435.024  211.51408.4513  242.75404.4919  330.19 400.208
  362.61400.0822   572.9  396.94  629.56385.4353   832.4  387.82  960.14381.7643
  995.27382.8401 1049.81379.3279  1079.7382.2582    1088  378.19  1151.9  376.04
  1191.8  378.02  1243.7  384.39 1416.65384.7231 1572.79387.4615 1649.66387.9168
 1923.55393.6231  2050.2   397.3  2074.2   402.7 2098.26399.4868    2182  398.73
 2223.32410.8383 2329.06422.0089  2611.7  431.05  2675.4  437.14  2758.9  457.25
#Mann= 20 ,-1 , 0
       0     .06       0   82.57     .12       0  211.51    .016       0
  242.75     .12       0  330.19     .06       0  362.61     .12       0
  629.56     .06       0  960.14    .016       0  995.27     .12       0
 1049.81     .08       0  1079.7     .04       0    1088    .045       0
  1191.8     .12       0 1416.65     .06       0 1572.79     .12       0
 1649.66     .06       0 1923.55     .12       0 2098.26     .04       0
 2223.32     .12       0 2329.06     .06       0
#XS Ineff= 2 , 0
       0     570            1900       0
Permanent Ineff=
       F       F
Bank Sta=1088,1191.8
XS Rating Curve= 0 ,0
Exp/Cntr=0.3,0.1

Type RM Length L Ch R = 1 ,12337.1 ,828,842.4,872.6
XS GIS Cut Line= 2
        2389461.      400931.763     2391079.056      401737.319
#Sta/Elev= 30
       0  457.93   63.79454.1105     108  447.13     180  421.35   205.1 415.872
  234.23410.6515   259.4 408.745   367.9  399.13  625.97391.1488   667.8  389.57
  696.58384.5151   855.8  385.17   939.7  382.33 1054.52386.8358 1098.88387.5076
 1126.28387.8658  1163.7  376.61  1211.7  380.54  1227.6  378.76  1251.6  375.41
  1311.6  375.45 1317.31378.8554 1323.74384.8233  1415.6  383.79  1471.6  375.66
  1523.6  399.68  1559.6  422.19  1579.6  430.21  1643.5   440.2  1807.5  457.62
#Mann= 13 ,-1 , 0
       0     .06       0   63.79     .12       0   205.1     .06       0
  234.23     .08       0   259.4     .06       0  625.97     .12       0
  696.58     .06       0 1054.52     .12       0 1098.88    .016       0
 1126.28     .12       0  1227.6    .045       0 1317.31     .04       0
 1323.74     .12       0
Bank Sta=1227.6,1317.31
XS Rating Curve= 0 ,0
Exp/Cntr=0.3,0.1

Type RM Length L Ch R = 1 ,11494.7 ,529.3,519.3,493.6
XS GIS Cut Line= 5
     2389245.723       401160.93     2389834.084      401707.265
      2389854.23      401772.909     2389955.792      401936.972
     2390062.563      402085.409
#Sta/Elev= 30
       0  458.85   10.72458.5344    43.9  458.73   68.86456.4448   107.8  451.34
   191.7  420.38  250.04409.4933  306.34403.1932   337.5  401.11   403.4     396
  560.24388.2458  597.12386.4956   607.2  383.18  629.89383.0401   655.1  380.84
     711  380.22     755  382.61     759  381.67     767  375.95     771  374.51
   875.5  374.51   883.4  376.31   891.3  381.81  904.33384.8914   922.8  385.69
   942.4  389.01  1001.5   420.1  1021.2  423.97    1140  429.36  1247.4  429.71
#Mann= 12 ,-1 , 0
       0     .12       0   10.72     .06       0   68.86     .12       0
  250.04     .06       0  306.34     .08       0   337.5     .06       0
  560.24     .12       0  597.12    .016       0  629.89     .12       0
     767    .045       0   883.4     .04       0  904.33     .12       0
Bank Sta=767,883.4
XS Rating Curve= 0 ,0
Exp/Cntr=0.3,0.1

Type RM Length L Ch R = 1 ,10975.3 ,427.5,420.1,412.7
XS GIS Cut Line= 4
     2388995.723      401299.819     2389113.778      401556.763
      2389724.64      402049.754     2389817.805      402092.731
#Sta/Elev= 30
       0  475.99  116.08477.7042   183.2  474.94   246.9  465.88   302.7  450.79
   386.4  408.22   422.2   399.8   457.2395.1545     470  389.66  493.88388.4613
   513.9  375.77   525.8  374.27   597.6  375.19   605.5  378.44  629.45 381.432
   681.2  382.74   721.1   381.2     729  380.25     741  375.67  751.12375.2023
   764.9  374.96  770.17377.3818   784.8     381   816.7  383.58   876.5  382.64
   908.4  384.25   940.2  388.94   976.1  397.39  1079.6  412.57  1170.4  419.73
#Mann= 9 ,-1 , 0
       0     .06       0  116.08     .12       0   457.2    .016       0
  493.88     .12       0   513.9    .045       0   597.6     .04       0
  629.45     .12       0  751.12     .04       0  770.17     .12       0
Bank Sta=513.9,597.6
XS Rating Curve= 0 ,0
Exp/Cntr=0.3,0.1

Type RM Length L Ch R = 1 ,10555.2 ,762.8,736.9,711
XS GIS Cut Line= 4
     2388381.173       402231.62     2388849.923      401901.759
     2389561.728      402214.259     2389809.124      402188.217
#Sta/Elev= 30
       0  452.62   107.5  443.29   214.9  430.94   378.1   410.4   461.7  405.94
   477.6  406.65   525.4  406.16   589.1  403.38   601.1  401.69     629  395.27
     641  389.73   648.9  382.52   668.9  374.63   676.8   373.9  781.57374.4465
   792.4  379.63   800.4  382.38   820.4  384.43   852.2  383.79   876.2  384.94
   979.8  386.41  1155.2  381.52  1191.1  381.94    1227  386.24  1266.8  395.35
  1282.8   398.1  1326.6  403.57    1398  408.38  1492.7  411.56  1599.3  417.96
#Mann= 3 ,-1 , 0
       0     .12       0   668.9    .045       0  781.57     .12       0
Bank Sta=668.9,781.57
XS Rating Curve= 0 ,0
Exp/Cntr=0.3,0.1

Type RM Length L Ch R = 1 ,9818.3  ,266.4,268,269.7
XS GIS Cut Line= 4
     2388030.445      402647.041       2388148.5      402688.708
     2389540.658      402261.867     2389829.056       402223.43
#Sta/Elev= 30
       0  448.69   101.7  440.76   129.2  437.36   149.1  432.15   224.9  428.46
   268.8  421.39   352.6  399.17   400.5  382.22   456.3  384.96   496.2  395.36
   500.2  394.86   512.2  386.85   528.1  379.67   548.1  375.84     560  371.79
   615.9  371.83   627.8  375.61  628.79375.9515   639.8  380.49   675.7  381.83
   707.6  380.28   739.6  383.56   771.5  380.96   998.9  377.05  1034.8  379.68
  1130.5  378.73  1357.9  385.61  1445.7   389.7  1629.1  407.64  1872.3  418.19
#Mann= 4 ,-1 , 0
       0     .12       0   548.1    .045       0   627.8     .04       0
  628.79     .12       0
#XS Ineff= 2 , 0
       0     496            1110       0
Permanent Ineff=
       F       F
Bank Sta=548.1,627.8
XS Rating Curve= 0 ,0
Exp/Cntr=0.3,0.1

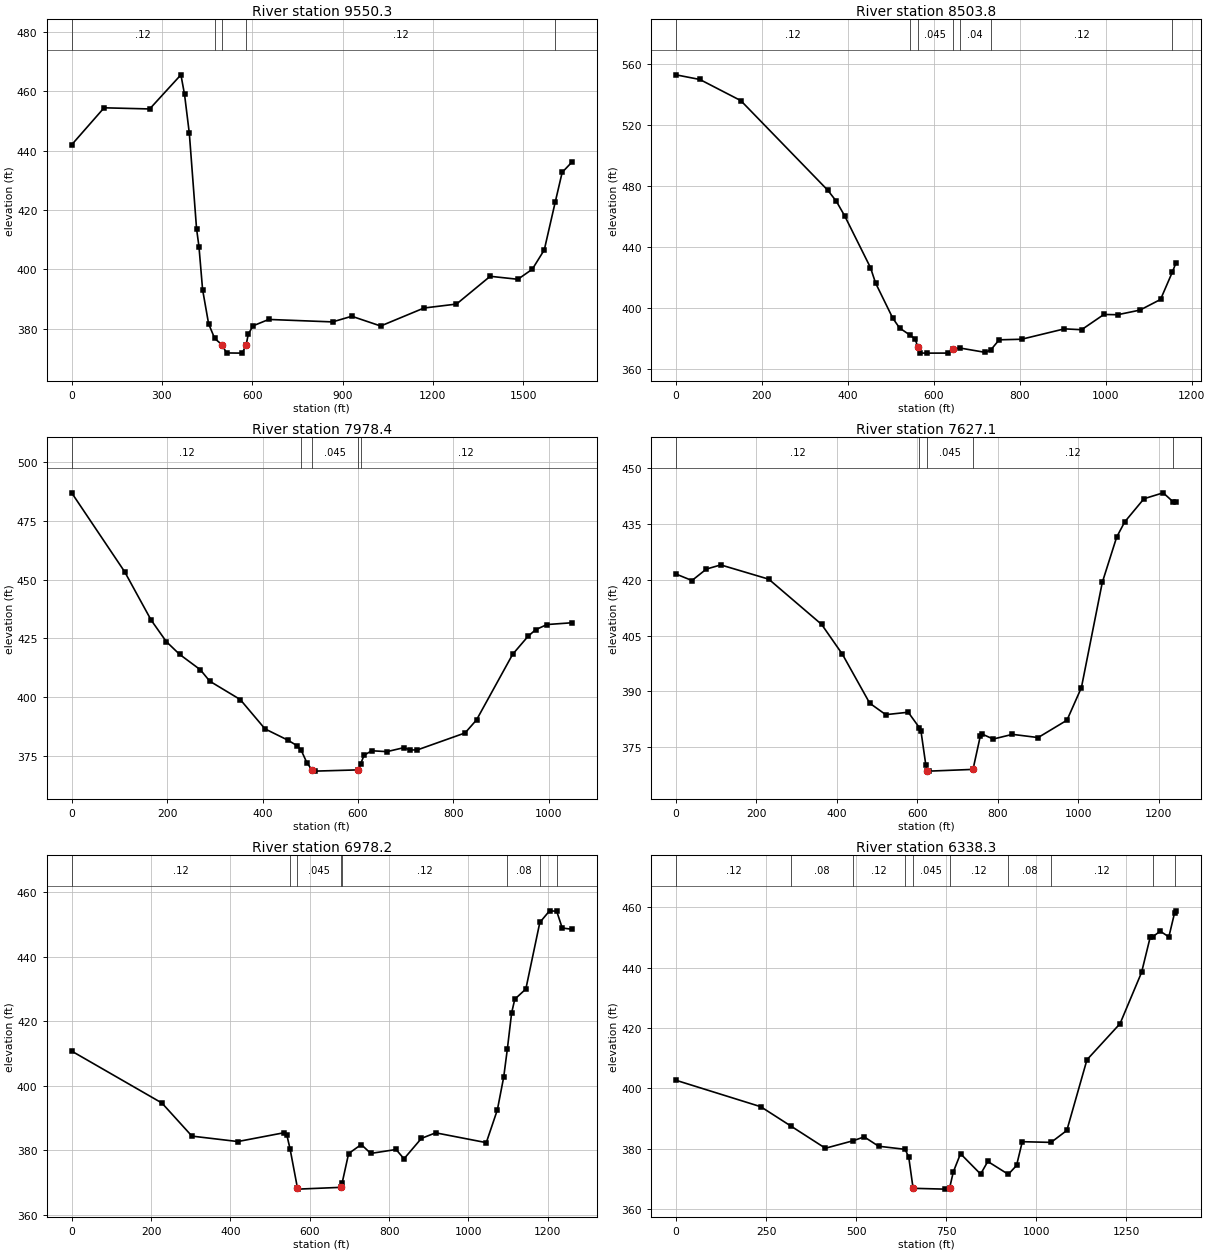
Type RM Length L Ch R = 1 ,9550.3  ,1094.5,1046.5,998.4
XS GIS Cut Line= 4
      2388337.77      403099.676     2388554.784      402839.259
     2389676.312      402436.481     2389745.756       402325.37
#Sta/Elev= 30
       0  441.93   107.7  454.39   259.2     454     363   465.5     375  458.91
     391  445.75     415  413.61     423  407.61     435  393.15     455  381.63
  475.19376.6772   498.9   374.6   514.9  371.79   566.9  371.73  579.94 374.574
   586.9  378.17   602.9  380.94   654.9  383.08   866.8  382.25   930.8  384.15
  1026.8  380.87  1170.8  386.93  1278.7  388.26  1390.7  397.62  1482.7  396.61
  1530.6     400  1570.4  406.51 1606.52422.5021  1629.9  432.64  1661.7  436.04
#Mann= 5 ,-1 , 0
       0     .12       0  475.19     .04       0   498.9    .045       0
  579.94     .12       0 1606.52     .08       0
#XS Ineff= 2 , 0
       0                     760       0
Permanent Ineff=
       F       F
Bank Sta=498.9,579.94
XS Rating Curve= 0 ,0
Exp/Cntr=0.3,0.1

Type RM Length L Ch R = 1 ,8503.8  ,535.5,525.4,515.3
XS GIS Cut Line= 4
      2389533.95      403457.315     2389735.339      403047.592
     2389770.062      402429.537      2389783.95      402342.731
#Sta/Elev= 30
       0  552.85    55.6   549.8   150.9  535.92   353.3  477.07   373.2  469.84
     393  460.04   452.6  426.29   464.5  416.15   504.5  393.09   520.4  386.63
  543.96382.0994   556.4  379.47  562.72 374.252   568.4  370.19   584.3  370.15
   632.3  370.18   644.2  372.56   659.9373.5415   720.1  370.63  732.83372.3734
   752.1  378.89     804  379.26   903.8  386.08   943.8  385.52   995.7  395.53
  1027.6  395.36  1079.6   398.4  1127.5   405.4 1155.15423.5037  1163.5   429.5
#Mann= 7 ,-1 , 0
       0     .12       0  543.96     .04       0  562.72    .045       0
   644.2     .12       0   659.9     .04       0  732.83     .12       0
 1155.15     .08       0
Bank Sta=562.72,644.2
XS Rating Curve= 0 ,0
Exp/Cntr=0.3,0.1

Type RM Length L Ch R = 1 ,7978.4  ,360.6,351.3,342
XS GIS Cut Line= 3
     2390145.028      403258.152     2390290.862      403008.152
     2390138.084      402265.097
#Sta/Elev= 30
       0  486.87     111  453.35   166.5  432.81   198.2  423.69     226  418.27
   269.6  411.71   289.4  406.84   353.3  399.04   405.2  386.57   453.1  381.79
   473.1  379.34  480.94 377.524     493  372.17  503.64369.1398     509  368.63
   600.8  369.16  605.64371.7433   612.8  375.38   628.8  377.28   660.7  376.91
   696.7  378.63   708.6   377.6   724.6  377.66   824.4  384.85   848.4  390.38
   924.2  418.28   956.2  425.86   972.2   428.7   996.1  430.91    1048  431.66
#Mann= 5 ,-1 , 0
       0     .12       0  480.94     .04       0  503.64    .045       0
   600.8     .04       0  605.64     .12       0
Bank Sta=503.64,600.8
XS Rating Curve= 0 ,0
Exp/Cntr=0.3,0.1

Type RM Length L Ch R = 1 ,7627.1  ,638.5,649,659.4
XS GIS Cut Line= 3
     2390568.673      403266.342     2390731.867      402988.565
     2390334.303      402158.195
#Sta/Elev= 30
       0  421.57    39.8  419.82    75.6   422.9   111.4  424.02   230.7  420.18
     362  408.02   413.8  399.97   481.6  386.82   521.4  383.74   577.2  384.39
  604.72380.2775   609.1  379.21   621.1  370.11  624.82368.6685     629  368.55
  738.26369.0165   756.6  378.08   760.6  378.53   788.5  377.18   836.3  378.44
   900.1  377.58   971.8  382.25  1007.7  391.04  1059.5  419.29  1095.3   431.5
  1115.3  435.59  1163.1  441.82  1210.9  443.41 1235.32441.0183  1242.8  440.86
#Mann= 5 ,-1 , 0
       0     .12       0  604.72     .04       0  624.82    .045       0
  738.26     .12       0 1235.32     .08       0
Bank Sta=624.82,738.26
XS Rating Curve= 0 ,0
Exp/Cntr=0.3,0.1

Type RM Length L Ch R = 1 ,6978.2  ,647.4,639.8,632.3
XS GIS Cut Line= 2
     2391304.409      403081.152     2391089.848      401839.176
#Sta/Elev= 30
       0  410.72   227.4  394.65   303.1   384.4   418.8  382.72   534.5  385.43
   542.4  384.69  550.55380.3779     569368.3645   570.4  367.99     678  368.54
  681.59369.8324     698     379   729.9   381.8   753.8  379.04   817.6  380.26
   837.6  377.38   881.5   383.7   917.4  385.42    1045  382.38  1072.9  392.52
  1088.9  402.68 1098.11411.3888  1108.8   422.5  1116.8  426.78  1144.7  429.94
 1179.94450.5508  1204.5  454.14 1222.46454.0153  1236.4  448.82  1260.4  448.44
#Mann= 8 ,-1 , 0
       0     .12       0  550.55     .04       0     569    .045       0
     678     .04       0  681.59     .12       0 1098.11     .08       0
 1179.94     .12       0 1222.46     .08       0
Bank Sta=569,678
XS Rating Curve= 0 ,0
Exp/Cntr=0.3,0.1

Type RM Length L Ch R = 1 ,6338.3  ,802.7,808.6,814.5
XS GIS Cut Line= 3
     2392037.423      402873.981     2391575.584      401688.708
     2391513.084      401591.486
#Sta/Elev= 30
       0  402.64   235.3  393.87  320.01387.3711   414.7  380.09  491.87 382.588
   522.4  383.86   562.3  380.76  635.98379.7263     646  377.12     658   366.8
   745.7  366.53  759.15366.7868   769.6  372.23   789.6  378.28   845.4  371.52
   865.3  375.71  922.24371.4366   945.1  374.38     961  382.26 1040.84 382.033
  1084.6  385.99  1140.5  409.45  1232.2   421.4    1292  438.41  1315.9  450.08
  1322.6450.2105  1343.8  452.08  1367.7  450.19 1383.57458.1642  1387.6  458.84
#Mann= 10 ,-1 , 0
       0     .12       0  320.01     .08       0  491.87     .12       0
  635.98     .04       0     658    .045       0  759.15     .12       0
  922.24     .08       0 1040.84     .12       0  1322.6     .08       0
 1383.57     .12       0
Bank Sta=658,759.15
XS Rating Curve= 0 ,0
Exp/Cntr=0.3,0.1