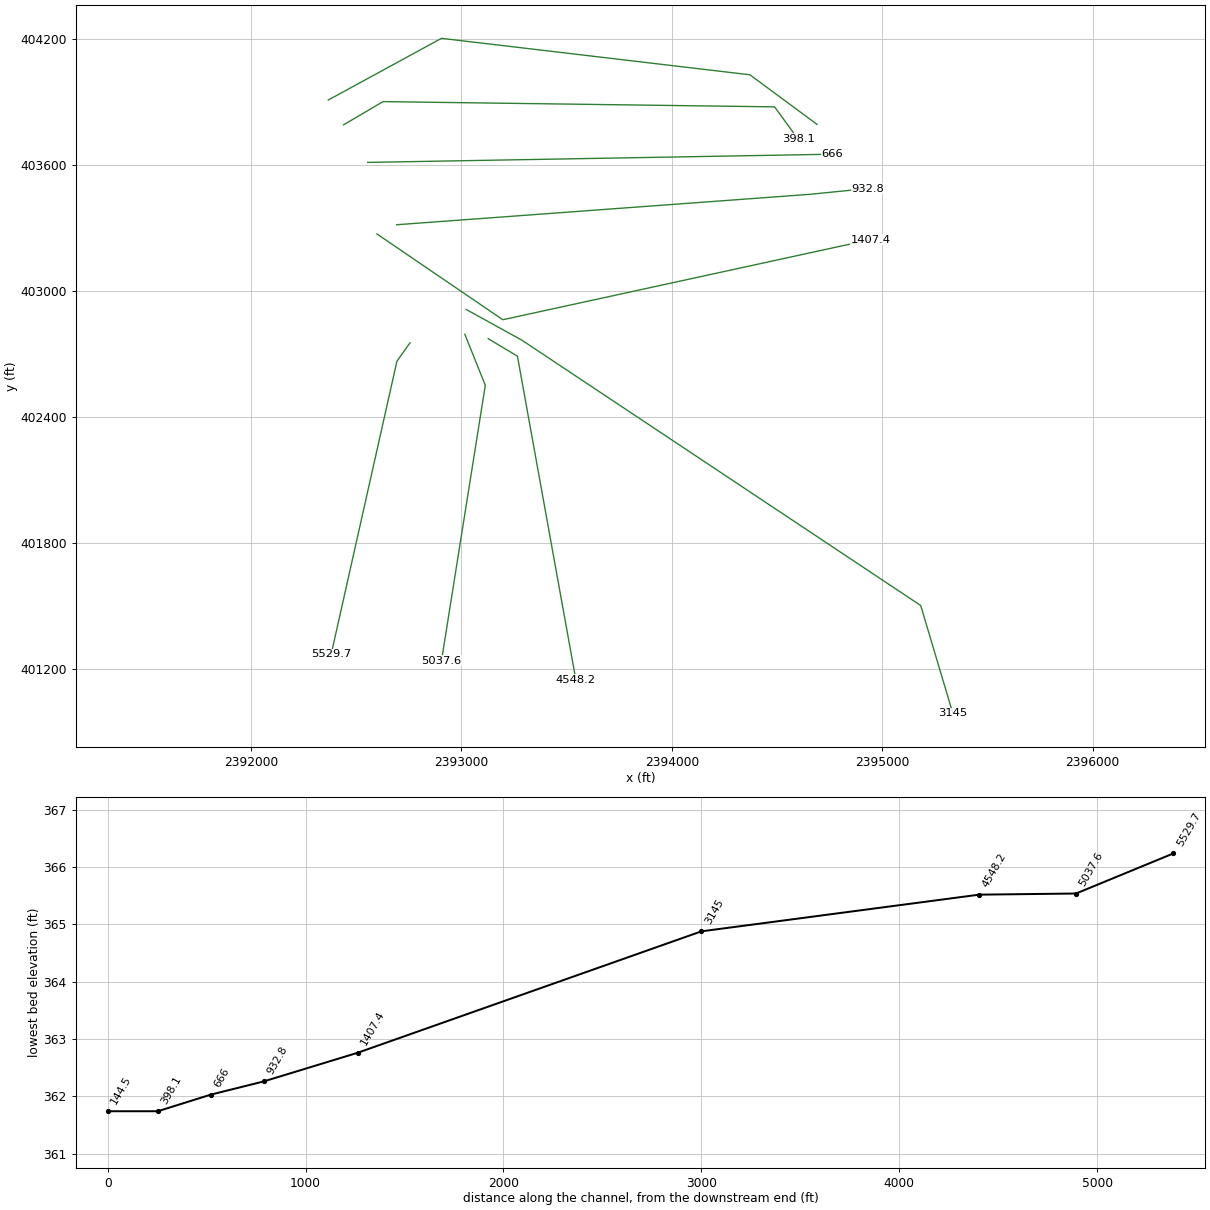
HEC-RAS study BACKCREEK.prj: BACKCREEK

--- BACKCREEK.g01 (geometry) --- (continued)

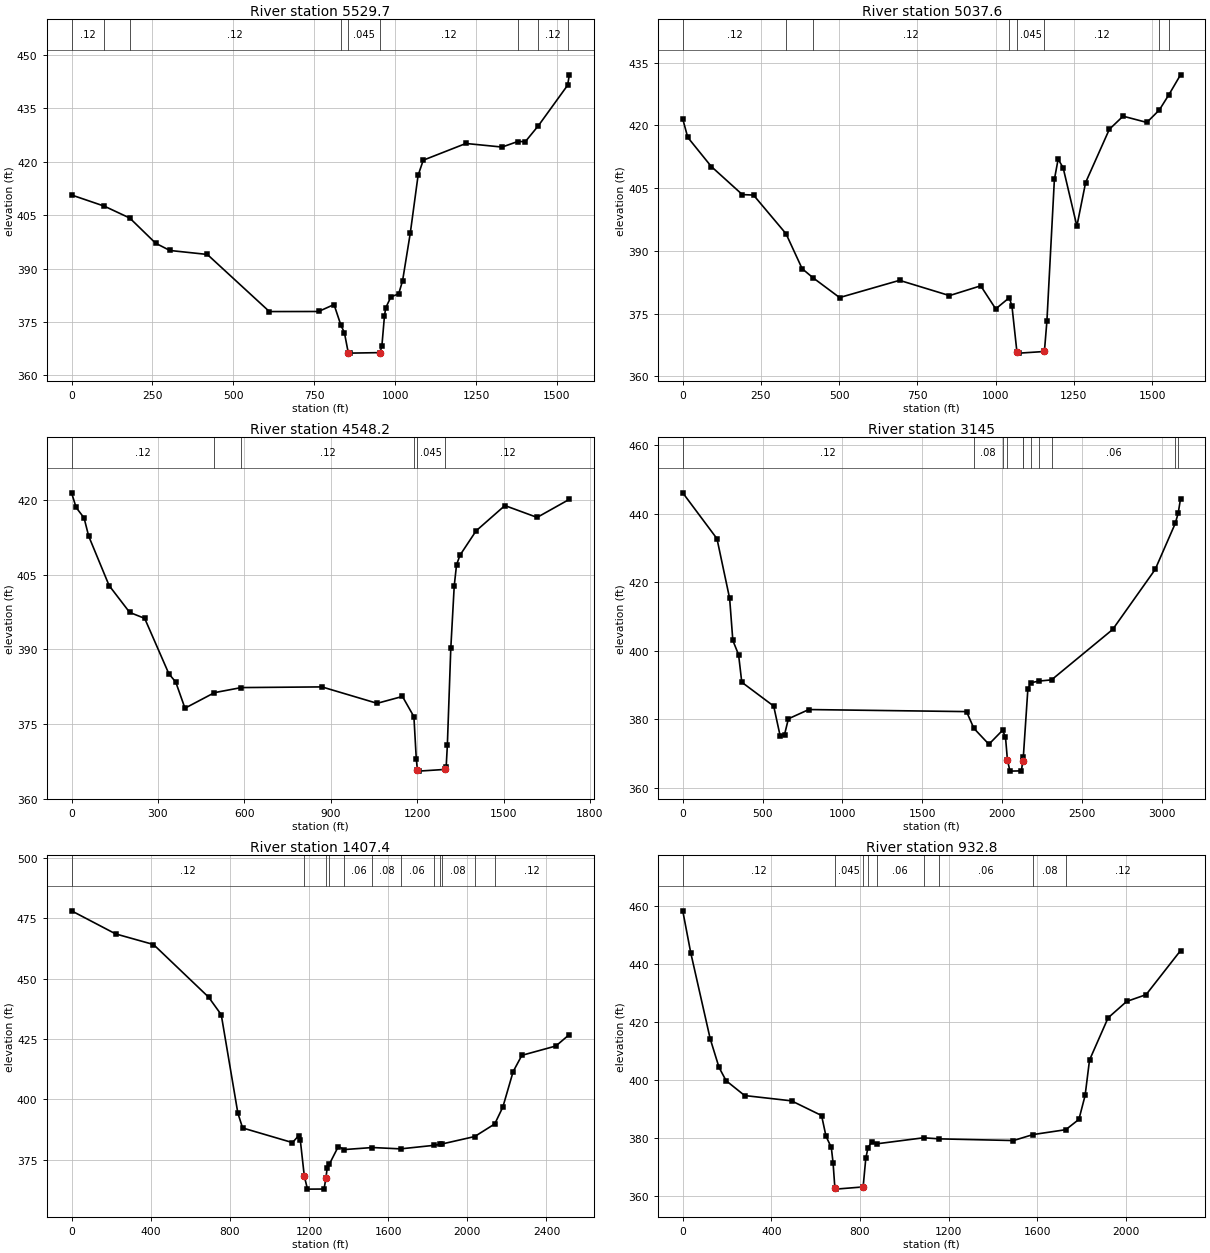
Type RM Length L Ch R = 1 ,5529.7  ,490.1,492.2,494.3
XS GIS Cut Line= 3
     2392756.173      402752.454     2392693.639      402664.402
     2392381.139      401268.569
#Sta/Elev= 30
       0  410.68  100.82407.5595  179.87404.2022   259.8  397.13   303.8  395.09
   419.6  393.97   611.4  377.92   763.3  377.94   811.2  379.89  832.66374.0218
   843.2  372.02   855.2  366.33   859.2  366.24  952.58366.3822     959  368.15
     967  376.66     971  378.98     987  382.04    1011   382.9    1023  386.56
  1046.9  399.99  1070.9  416.16  1086.9  420.46  1218.7  425.16  1330.6  424.15
 1379.08425.7112  1402.5  425.68 1442.85430.1659 1533.08441.5172  1538.4  444.45
#Mann= 9 ,-1 , 0
       0     .12       0  100.82     .06       0  179.87     .12       0
  832.66     .04       0   855.2    .045       0  952.58     .12       0
 1379.08    .016       0 1442.85     .12       0 1533.08     .08       0
Bank Sta=855.2,952.58
XS Rating Curve= 0 ,0
Exp/Cntr=0.3,0.1

Type RM Length L Ch R = 1 ,5037.6  ,475.7,489.4,503.1
XS GIS Cut Line= 3
     2393016.556      402792.875     2393113.778      402549.819
     2392905.445      401237.319
#Sta/Elev= 30
       0  421.56    15.9  417.16    91.2  410.18   190.4  403.46   226.1  403.35
  330.07394.0896   381.5  385.74  415.37383.6175   501.2  378.83   692.8  382.95
   852.4   379.3   952.2  381.64  1000.1  376.12 1043.49378.7995    1052   376.8
  1067.9  365.81  1075.9  365.54  1155.7  365.93  1163.7  373.19  1187.6  407.08
  1199.6  411.94  1215.6  409.88  1259.5  395.93  1287.4  406.35  1363.2  419.08
  1407.1  422.22    1483  420.72 1522.96423.7003 1553.93427.4034  1590.7  432.11
#Mann= 8 ,-1 , 0
       0     .12       0  330.07     .06       0  415.37     .12       0
 1043.49     .04       0  1067.9    .045       0  1155.7     .12       0
 1522.96    .016       0 1553.93     .12       0
Bank Sta=1067.9,1155.7
XS Rating Curve= 0 ,0
Exp/Cntr=0.3,0.1

Type RM Length L Ch R = 1 ,4548.2  ,1374.3,1403.2,1432.4
XS GIS Cut Line= 3
     2393127.667      402772.041     2393266.556      402688.708
     2393544.334      401147.041
#Sta/Elev= 30
       0  421.46    15.8  418.52    43.5  416.41    59.3  412.78   130.4  402.82
   201.9  397.42   253.9  396.23   337.8   385.1   361.8  383.42   393.8  378.17
  496.31381.2968  589.25 382.313   869.3  382.45  1061.1  379.15    1149  380.53
 1188.75376.4694    1197  368.04    1201  365.72    1205  365.52 1298.24365.8681
  1300.9  366.44  1304.9  370.68  1316.9  390.24  1328.8  402.75  1336.8  406.98
  1348.8  408.92  1404.8  413.82  1504.7   418.9  1616.6  416.52  1728.5  420.15
#Mann= 6 ,-1 , 0
       0     .12       0  496.31     .06       0  589.25     .12       0
 1188.75     .04       0    1201    .045       0 1298.24     .12       0
Bank Sta=1201,1298.24
XS Rating Curve= 0 ,0
Exp/Cntr=0.3,0.1

Type RM Length L Ch R = 1 ,3145    ,1707.3,1737.5,1767.4
XS GIS Cut Line= 4
       2393023.5       402910.93     2393287.389      402765.097
     2395183.223      401501.208        2395336.      400987.319
#Sta/Elev= 30
       0  446.14   214.2  432.75   293.6  415.29   313.5  403.05   349.5  398.87
   369.5  390.84   569.3  383.87   609.3  375.26   637.3  375.57   661.3  380.16
   789.2  382.86  1776.5  382.26 1822.55377.3703  1916.4  372.72 2002.08376.8101
  2020.4  374.82  2032.4  368.18  2048.4  364.88  2120.3  364.96  2128.3  367.92
 2132.03369.0204  2160.3  388.74 2177.99390.6857 2232.76391.1845  2308.6 391.527
  2691.2  406.24  2957.3  423.76 3083.18437.2118 3101.93440.2952  3116.1  444.42
#Mann= 11 ,-1 , 0
       0     .12       0 1822.55     .08       0 2002.08     .12       0
  2032.4    .045       0  2128.3     .04       0 2132.03     .12       0
 2177.99     .06       0 2232.76     .12       0  2308.6     .06       0
 3083.18     .12       0 3101.93    .016       0
Bank Sta=2032.4,2128.3
XS Rating Curve= 0 ,0
Exp/Cntr=0.3,0.1

Type RM Length L Ch R = 1 ,1407.4  ,479.9,474.6,469.2
XS GIS Cut Line= 3
     2392598.756      403270.799     2393197.112      402862.319
     2394947.112      403244.263
#Sta/Elev= 30
       0  478.12   222.9  468.55     414  464.16   692.6  442.34   756.5  435.06
   840.4   394.3   864.4  388.12  1116.3  382.05  1148.3  384.95  1156.3  382.92
  1176.3  368.14  1192.3  362.76  1276.2   362.8 1285.75 367.544  1292.2  371.72
 1302.75373.0959  1348.2  380.42 1379.13379.1642 1520.59 380.002 1662.66379.4469
  1830.3380.9001 1862.46381.3158    1871381.4544 2037.35384.5554 2138.79 389.789
  2179.8  396.81  2231.8  411.49  2275.8  418.22  2447.7  422.09  2515.7  426.83
#Mann= 12 ,-1 , 0
       0     .12       0  1176.3    .045       0 1285.75     .04       0
 1302.75     .12       0 1379.13     .06       0 1520.59     .08       0
 1662.66     .06       0  1830.3     .08       0 1862.46     .06       0
    1871     .08       0 2037.35     .06       0 2138.79     .12       0
#XS Ineff= 2 , 0
       0                    1800       0
Permanent Ineff=
       F       F
Bank Sta=1176.3,1285.75
XS Rating Curve= 0 ,0
Exp/Cntr=0.3,0.1

Type RM Length L Ch R = 1 ,932.8   ,268.1,266.8,265.5
XS GIS Cut Line= 3
     2392692.346      403314.718     2394655.445      403459.541
     2394933.223      403487.319
#Sta/Elev= 30
       0   458.5    35.9  444.06   123.8  414.29   163.7  404.37   195.6  399.77
   279.5  394.62   491.1  392.79   626.9  387.71   646.8  380.56   670.8  376.66
   678.8  371.32   686.8  362.72   690.8  362.26   814.5  363.02   826.5  372.94
  836.61  376.62   854.4  378.69  877.12377.9412  1087.2 380.013 1159.21379.6402
  1493.3  379.06 1581.76381.1314 1729.51 382.817  1788.8  386.38  1816.7  394.64
  1836.7   406.9  1920.5  421.49  2004.3  427.16  2092.1  429.51  2247.6  444.74
#Mann= 9 ,-1 , 0
       0     .12       0   686.8    .045       0   814.5     .04       0
  836.61     .12       0  877.12     .06       0  1087.2     .08       0
 1159.21     .06       0 1581.76     .08       0 1729.51     .12       0
#XS Ineff= 2 , 0
       0                    1280       0
Permanent Ineff=
       F       F
Bank Sta=686.8,814.5
XS Rating Curve= 0 ,0
Exp/Cntr=0.3,0.1

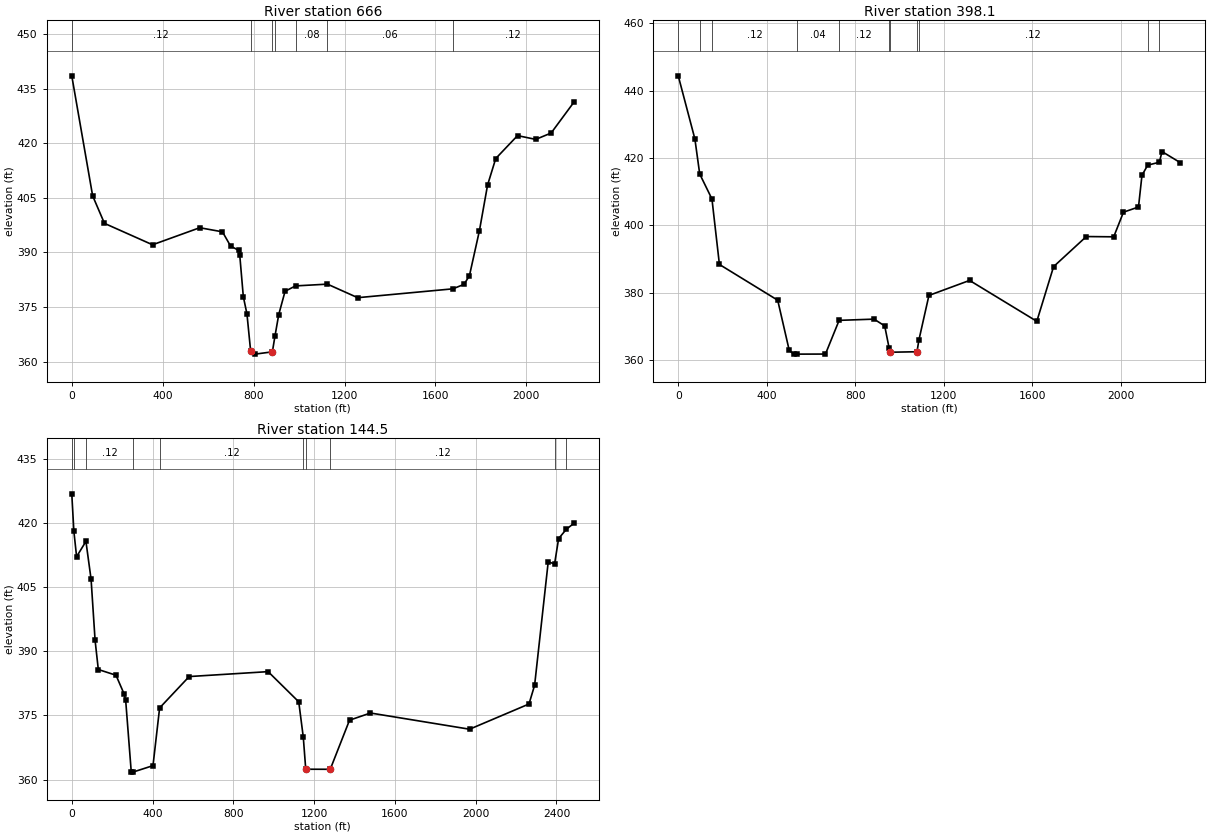
Type RM Length L Ch R = 1 ,666     ,269.1,268,266.8
XS GIS Cut Line= 3
     2392554.799      403611.677     2393812.482      403633.897
     2394763.289      403650.695
#Sta/Elev= 30
       0  438.56    91.8  405.57   143.8  397.99   355.4   392.1     563  396.79
   662.9  395.66   698.8  391.73   734.8  390.56   738.8   389.4   754.7  377.84
   770.7  373.08   786.7     363   806.6  362.03   882.5  362.66  894.15367.0663
   910.5   372.9   938.4  379.32  984.44380.7896 1124.75381.2756  1257.9  377.55
 1676.41379.9834  1725.4  381.21  1749.3  383.56  1793.3  395.94  1829.2  408.52
  1865.2  415.82  1961.1  422.12    2041  421.08  2108.9  422.83  2208.8  431.29
#Mann= 7 ,-1 , 0
       0     .12       0   786.7    .045       0   882.5     .04       0
  894.15     .12       0  984.44     .08       0 1124.75     .06       0
 1676.41     .12       0
#XS Ineff= 2 , 0
       0                    1074       0
Permanent Ineff=
       F       F
Bank Sta=786.7,882.5
XS Rating Curve= 0 ,0
Exp/Cntr=0.3,0.1

Type RM Length L Ch R = 1 ,398.1   ,257.3,253.5,249.8
XS GIS Cut Line= 4
       2392440.2      403790.648     2392627.692      403901.154
     2394488.778      403876.208     2394599.889       403723.43
#Sta/Elev= 30
       0  444.44    75.2  425.68   96.98415.2752   152.3 407.831     186  388.39
   449.3  377.76   501.2  362.91   521.2  361.74  538.33361.7424     665  361.76
  726.66371.7744   884.6  372.14   932.6  370.12  952.93363.4167   956.5   362.3
 1078.57362.4488 1086.78365.8524  1132.3  379.18    1316  383.64  1619.6  371.49
  1695.4  387.74  1843.2  396.68    1967   396.6    2011  403.92  2078.9  405.46
  2094.6  414.87 2120.41417.8889 2173.18418.7649  2185.2  421.93  2267.8  418.64
#Mann= 11 ,-1 , 0
       0     .12       0   96.98     .08       0   152.3     .12       0
  538.33     .04       0  726.66     .12       0  952.93     .04       0
   956.5    .045       0 1078.57     .04       0 1086.78     .12       0
 2120.41     .08       0 2173.18     .12       0
#XS Ineff= 2 , 0
       0     850            1320       0
Permanent Ineff=
       F       F
Bank Sta=956.5,1078.57
XS Rating Curve= 0 ,0
Exp/Cntr=0.3,0.1

Type RM Length L Ch R = 1 ,144.5   ,154.2,144.5,134.8
XS GIS Cut Line= 4
     2392367.284      403908.704     2392905.445      404202.597
     2394371.544       404028.98     2394690.167      403792.875
#Sta/Elev= 30
       0  426.85   10.38418.0725    23.9  412.15   70.15415.7257    95.6  406.87
   115.5  392.55   131.4  385.75     219  384.41   258.8  380.07   266.8  378.62
   294.6  361.74  302.46  361.74   402.2  363.26  434.96376.7588   581.3   384.1
   972.3  385.25  1123.9  378.19 1146.41369.9102 1158.54362.4213 1279.87362.4028
  1375.3  373.89    1479  375.57  1969.8  371.78    2264  377.68  2291.8  382.06
  2359.2  410.94 2390.67410.4481  2410.7  416.38 2448.52418.5338  2486.1  419.95
#Mann= 10 ,-1 , 0
       0     .12       0   10.38     .08       0   70.15     .12       0
  302.46     .04       0  434.96     .12       0 1146.41     .04       0
 1158.54    .045       0 1279.87     .12       0 2390.67     .08       0
 2448.52     .12       0
#XS Ineff= 2 , 0
       0     940                       0
Permanent Ineff=
       F       F
Bank Sta=1158.54,1279.87
XS Rating Curve= 0 ,0
Exp/Cntr=0.3,0.1

Chan Stop Cuts=-1
Use User Specified Reach Order=0
Composite Channel Slope=5